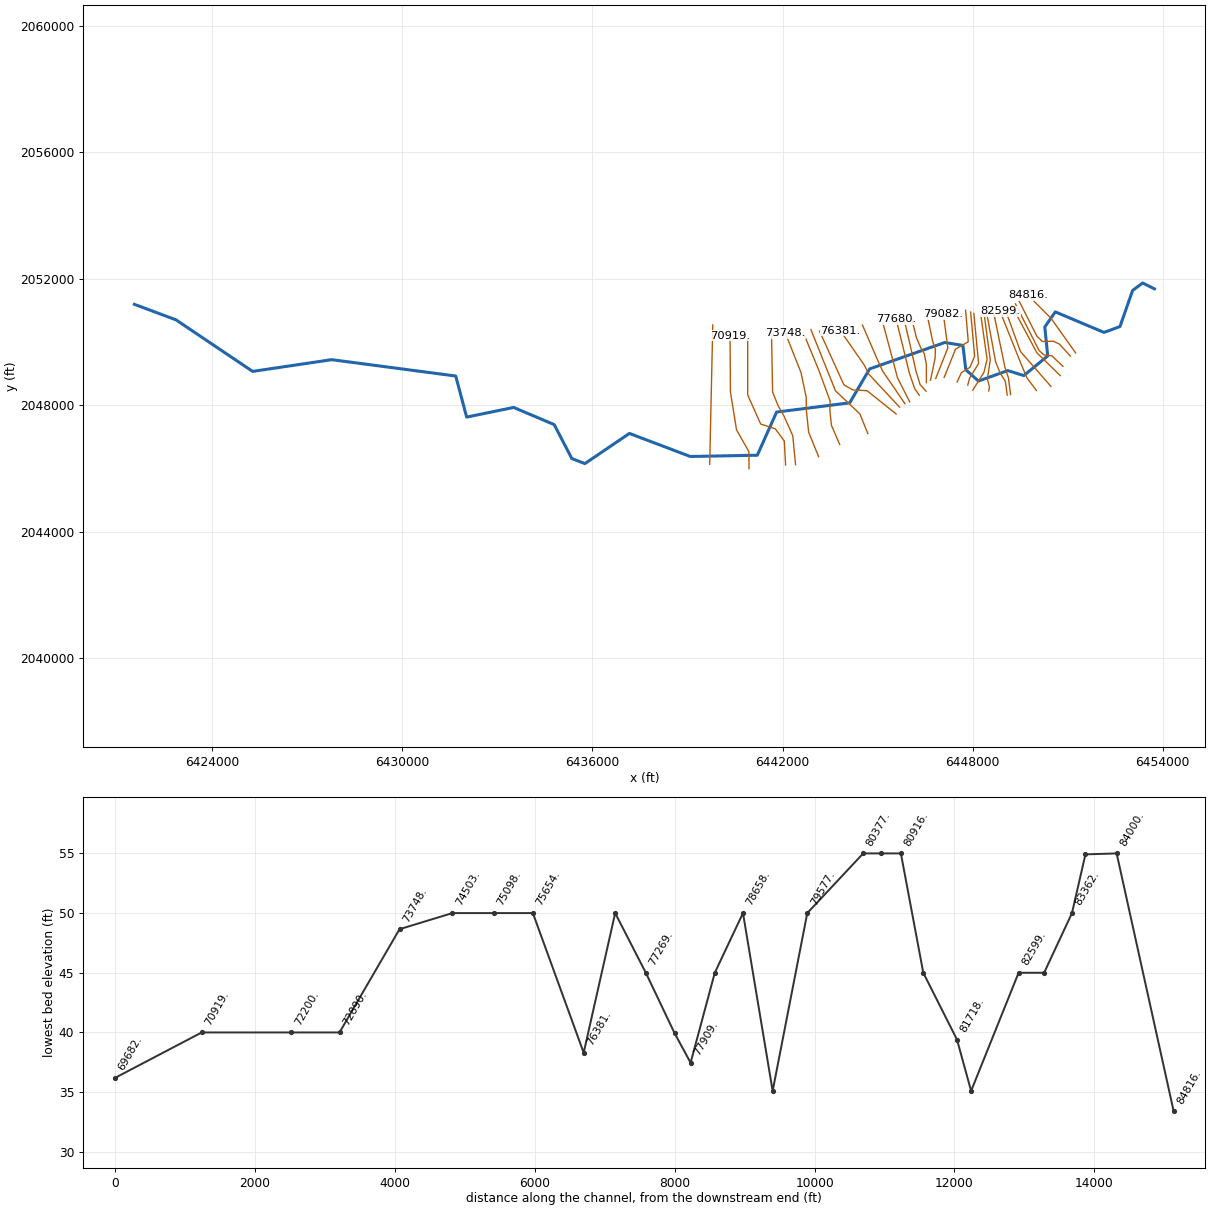
--- Baxter.prj (project) ---

Proj Title=Baxter River GIS Example
Current Plan=p01
Default Exp/Contr=0.3,0.1
English Units
Geom File=g02
Geom File=g01
Flow File=f01
Unsteady File=u01
Plan File=p01
Plan File=p02
Y Axis Title=Elevation
X Axis Title(PF)=Main Channel Distance
X Axis Title(XS)=Station
BEGIN DESCRIPTION:
Example GIS Application
END DESCRIPTION:
DSS File=dss
DSS Export Rating Curves= 0
DSS Export Rating Curve Sorted= 0
DSS Export Volume Flow Curves= 0
DXF OffsetX= 0
DXF OffsetY= 0
DXF ScaleX= 1
DXF ScaleY= 10

--- Baxter.p01 (plan) ---

Plan Title=Steady Flows
Program Version=3.13
Short Identifier=Steady Flow
Simulation Date=01jan2005,0100,04jan2005,2400
Geom File=g02
Flow File=f01
Subcritical Flow
K Sum by GR= 0
Std Step Tol= 0.01
Critical Tol= 0.01
Num of Std Step Trials= 20
Max Error Tol= 0.3
Flow Tol Ratio= 0.001
Split Flow NTrial= 30
Split Flow Tol= 0.02
Split Flow Ratio= 0.02
Log Output Level= 0
Friction Slope Method= 1
Unsteady Friction Slope Method= 2
Unsteady Bridges Friction Slope Method= 1
Parabolic Critical Depth
Global Vel Dist= 0 , 0 , 0
Global Log Level= 0
CheckData=True
Encroach Param=-1 ,0,0, 0
Computation Interval=10MIN
Output Interval=1HOUR
Run HTab= 1
Run UNet= 1
Run PostProcess= 1
UNET Theta= 1
UNET Theta Warmup= 1
UNET ZTol= 0.02
UNET ZSATol= 0.05
UNET MxIter= 20
UNET MaxInSteps= 0
UNET DtIC= 0
UNET DtMin= 0
UNET MaxCRTS= 20
UNET WFStab= 2
UNET SFStab= 1
UNET WFX= 1
UNET SFX= 1
UNET DSS MLevel= 4
UNET DZMax Abort= 100
UNET Convert EG Bridges=-1
UNET Use Existing IB Tables=-1
UNET Froude Reduction=False
UNET Froude Limit= 1
UNET Froude Power= 10
Instantaneous Interval=1HOUR
DSS File=dss
Write IC File= 0
Echo Input=False
Echo Output=False
Write Detailed= 0
Detailed Automatic Start=False, 10

--- Baxter.p02 (plan) ---

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Plan Title=Unsteady Flow
Program Version=4.10
Short Identifier=UnsteadyFlow
Geom File=g02
Flow File=u01
Run WQNet= 0
UNET Time Slicing=0,0, 5
UNET Junction Losses=0
Write IC File at Sim End=0
Echo Parameters=False
WQ AD Non Conservative
WQ ULTIMATE=-1
WQ Max Comp Step=1HOUR
WQ Output Interval=15MIN
WQ Output Selected Increments= 0
WQ Output face flow=0
WQ Output face velocity=0
WQ Output face area=0
WQ Output face dispersion=0
WQ Output cell volume=0
WQ Output cell surface area=0
WQ Output cell continuity=0
WQ Output cumulative cell continuity=0
WQ Output face conc=0
WQ Output face dconc_dx=0
WQ Output face courant=0
WQ Output face peclet=0
WQ Output face adv mass=0
WQ Output face disp mass=0
WQ Output cell mass=0
WQ Output cell source sink temp=0
WQ Output cell source sink nsm=0
WQ Output MaxMinRange=-1
WQ Daily Max Min Mean=-1
WQ Daily Range=0
WQ Daily Time=0
WQ Create Restart=0
WQ Fixed Restart=0
WQ System Summary=0
WQ Use Fixed Temperature=0
Sorting and Armoring Iterations= 10
XS Update Threshold= 0.02
Hydraulics Update Threshold= 0.02
Energy Slope Method= 1
Volume Change Method= 0
XS Weighting Method= 0
Number of US Weighted Cross Sections= 1
Number of DS Weighted Cross Sections= 1
Upstream XS Weight=0.25
Main XS Weight=0.5
Downstream XS Weight=0.25
Number of DS XS's Weighted with US Boundary= 1
Upstream Boundary Weight= 1
Weight of XSs Associated with US Boundary= 0
Number of US XS's Weighted with DS Boundary= 1
Downstream Boundary Weight= 0.5
Weight of XSs Associated with DS Boundary= 0.5
Sediment Output Level= 4
Mass or Volume Output= 0
Output Increment Type= 1
Profile and TS Output Increment= 10
XS Output Flag= 0
XS Output Increment= 10
Disregard all LS=0
Disregard all Conn=0
Disregard all Breaches=0
Disregard all Pumps=0

--- Baxter.f01 (steady flow) ---

Flow Title=Steady Flows
Program Version=3.13
Number of Profiles= 3
Profile Names=Big,Bigger,Biggest
River Rch & RM=Baxter River,Upper Reach     ,84816.
   31500   67500  149400
River Rch & RM=Baxter River,Lower Reach     ,47694.
   32000   70000  154000
River Rch & RM=Tule Creek,Tributary       ,10982.
     500    2500    4600
Boundary for River Rch & Prof#=Baxter River,Upper Reach     , 1
Up Type= 0
Dn Type= 0
Boundary for River Rch & Prof#=Baxter River,Upper Reach     , 2
Up Type= 0
Dn Type= 0
Boundary for River Rch & Prof#=Baxter River,Upper Reach     , 3
Up Type= 0
Dn Type= 0
Boundary for River Rch & Prof#=Baxter River,Lower Reach     , 1
Up Type= 0
Dn Type= 3
Dn Slope=0.001
Boundary for River Rch & Prof#=Baxter River,Lower Reach     , 2
Up Type= 0
Dn Type= 3
Dn Slope=0.001
Boundary for River Rch & Prof#=Baxter River,Lower Reach     , 3
Up Type= 0
Dn Type= 3
Dn Slope=0.001
Boundary for River Rch & Prof#=Tule Creek,Tributary       , 1
Up Type= 0
Dn Type= 0
Boundary for River Rch & Prof#=Tule Creek,Tributary       , 2
Up Type= 0
Dn Type= 0
Boundary for River Rch & Prof#=Tule Creek,Tributary       , 3
Up Type= 0
Dn Type= 0
DSS Import GetInterval= 0
DSS Import GetPeak= 0
DSS Import FillOption= 0
Storage Area Elev=Northside       , 3
      65      65      65
Storage Area Elev=Southside       , 3
      65      65      65

--- Baxter.u01 (unsteady flow) ---

Flow Title=Flood Event
Program Version=4.10
Use Restart= 0
Initial Flow Loc=Baxter River    ,Upper Reach     ,84816.  ,2000
Initial Flow Loc=Baxter River    ,Lower Reach     ,47694.  ,4000
Initial Flow Loc=Tule Creek      ,Tributary       ,10982.  ,2000
Initial Storage Elev=Northside       ,63.34
Initial Storage Elev=Southside       ,68.1
Boundary Location=Baxter River    ,Upper Reach     ,84816.  ,        ,                ,                ,
Interval=1HOUR
Flow Hydrograph= 100
    2000 2583.51 4324.85 7196.5411153.3116132.7422056.3228830.6336348.8244492.33
53132.7462133.78 71353.5 80646.589866.2298867.26107507.7115651.2123169.4129943.7
135867.3140846.7144803.5147675.2149416.5  150000149416.5147675.2144803.5140846.7
135867.3129943.7123169.4115651.2107507.798867.2689866.22 80646.576810.87 73162.3
69691.6766390.3163249.9660262.7757421.2654718.3352147.2349701.5247375.0945162.12
43057.08 41054.739149.9837338.16 35614.733975.2932415.8430932.4429521.3928179.15
26902.3825687.8824532.6123433.6822388.3521393.9920448.1419548.4118692.5717878.46
17104.0616367.4215666.7215000.1814366.1613763.0513189.3612643.6512124.5511630.77
11161.0810714.2810289.28 9885.01 9500.45 9134.65 8786.69  8455.7 8140.85 7841.36
 7556.47 7285.48  7027.7  6782.5    6000    6000    6000    6000    5500    5000
Use DSS=False
CWMS InputPosition= 0
Use Fixed Start Time=False
Is Critical Boundary=False
Boundary Location=Baxter River    ,Lower Reach     ,1192.   ,        ,                ,                ,
Friction Slope=0.001
Boundary Location=Tule Creek      ,Tributary       ,10982.  ,        ,                ,                ,
Interval=1HOUR
Flow Hydrograph= 100
 2012.33 2049.25 2110.52 2195.77 2304.48 2435.97 2589.44 2763.93 2958.38 3171.57
 3402.21 3648.86 3910.01 4184.04 4469.27 4763.93 5066.22 5374.26 5686.16    6000
 6313.84 6625.74 6933.78 7236.07 7530.73 7815.96 8089.99 8351.14 8597.79 8828.43
 9041.62 9236.07 9410.56 9564.03 9695.52 9804.23 9889.48 9950.75 9987.67   10000
 9987.67 9950.75 9889.48 9804.23 9695.52 9564.03 9410.56 9236.07 9041.62 8828.43
 8597.79 8351.14 8089.99 7815.96 7530.73 7236.07 6933.78 6625.74 6313.84 6103.45
 5903.32 5712.95 5531.87 5359.62 5195.77 5039.91 4891.65 4750.62 4616.47 4488.87
 4367.48 4252.02 4142.19 4037.71 3938.33  3843.8 3753.88 3668.34 3586.97 3509.57
 3435.95 3365.92  3299.3 3235.94 3175.66 3118.32 3063.78  3011.9 2962.55  2915.6
 2870.95 2828.47 2788.07 2749.63 2713.07  2678.3 2645.22 2613.75 2583.81 2555.34
Use DSS=False
CWMS InputPosition= 0
Use Fixed Start Time=False
Is Critical Boundary=False

--- Baxter.g02 (geometry) ---

Geom Title=Imported GIS Data +Bridges
Program Version=4.10

Junct Name=2
Junct Desc=, 0 , 0 ,-1 ,0
Up River,Reach=Baxter River    ,Upper Reach
Up River,Reach=Tule Creek      ,Tributary
Dn River,Reach=Baxter River    ,Lower Reach
Junc L&A=514.47,0
Junc L&A=1595.1,0

River Reach=Baxter River    ,Upper Reach
Reach XY= 30
 6453739.9899796 2051684.7799805 6453368.7399981 2051870.4000012
 6453050.5300221 2051631.7400223 6452652.7600141 2050491.4700039
  6452148.909995 2050305.8399957 6450610.8700161 2050955.5300195
 6450279.3900156 2050478.2100144 6450372.2000023 2049563.3299978
 6449616.4400024 2048940.1600005 6449112.6000182 2049099.2699823
 6448184.4600121 2048767.7899819 6447786.6900041 2049125.7900087
 6447693.8800174 2049894.8099982 6447123.7399908 2049987.6199849
 6444750.3799799 2049152.3000003 6444120.5699766 2048078.3199895
 6441813.5000206 2047786.6200051 6441203.5900129 2046420.9400099
 6439088.7700013 2046381.1699814 6437166.2100164 2047110.4100023
 6435760.7599927 2046155.7600046 6435349.7299952 2046314.8699863
 6434792.8500054 2047388.8499971 6433513.3499784 2047932.4699973
 6432028.3400175 2047627.5200109  6431683.610015  2048926.900011
 6427765.5700192 2049443.9999847 6425272.8700076 2049072.7500032
 6422850.0600126 2050705.5899968 6421540.4499851 2051194.1899983

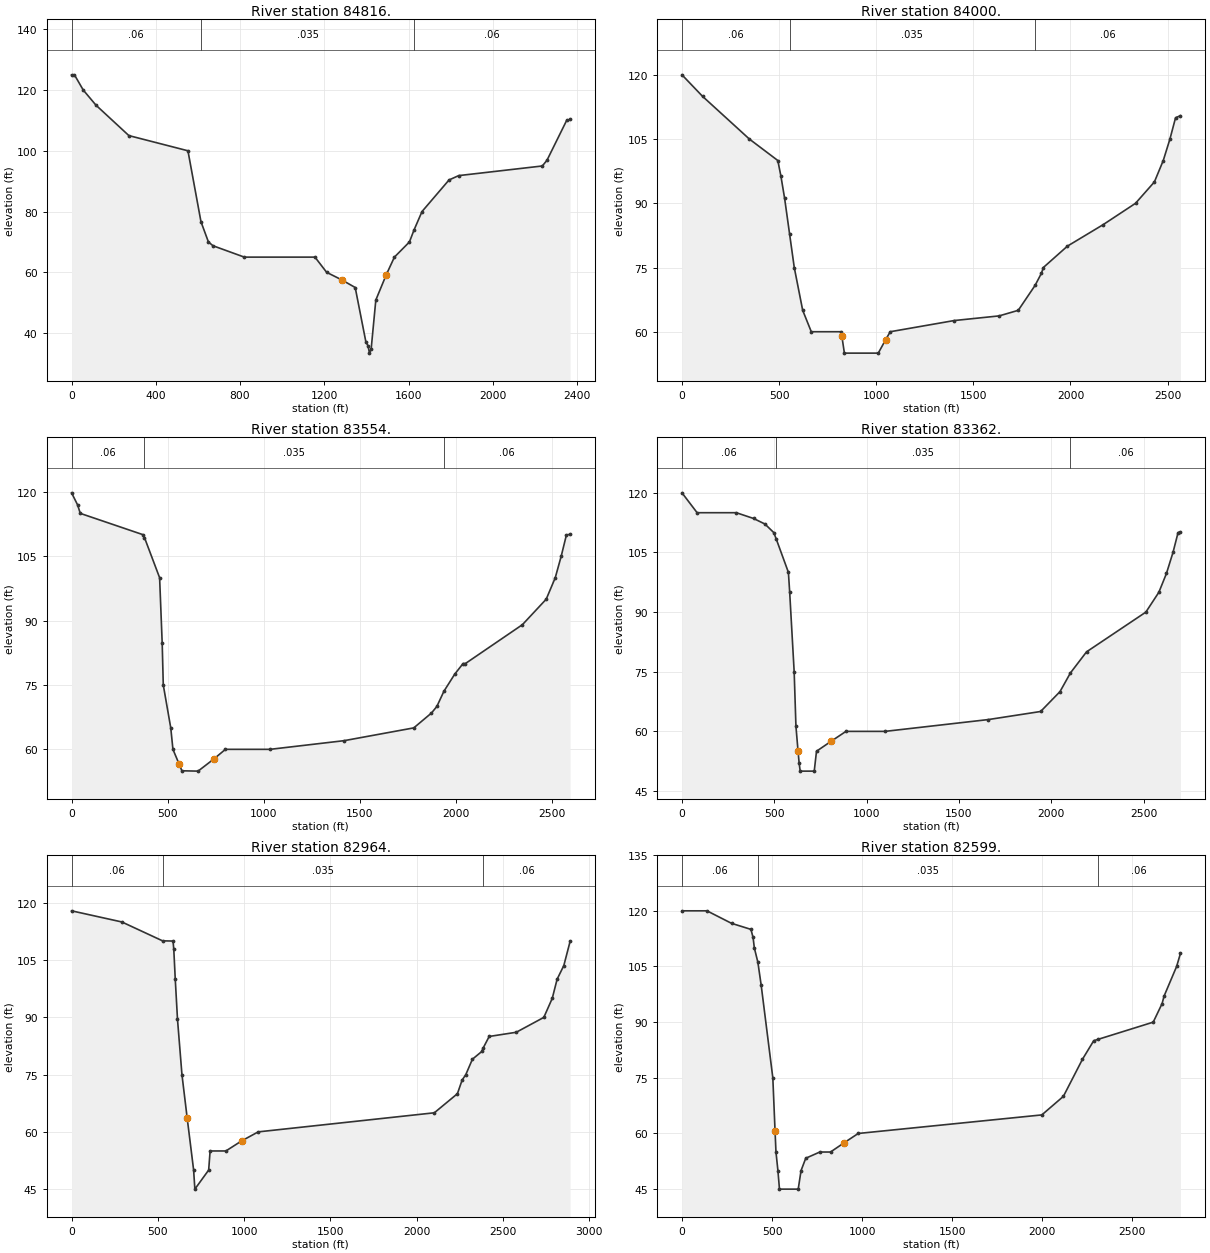
Type RM Length L Ch R = 1 ,84816.  ,343.45,815.24,627.65
XS GIS Cut Line= 3
 6451252.6104362 2049658.4807595  6450473.975481 2050754.3373982
 6449753.0171611 2051480.1020886
#Sta/Elev= 30
       0     125   13.58     125   55.26     120     116     115  272.01     105
  552.51     100  614.42   76.65  649.72      70  671.54   68.74  820.19      65
 1155.78      65 1211.11      60 1282.42   57.53 1346.84      55 1397.53    37.1
  1407.9    35.8 1414.52    33.4 1422.67    34.8 1444.74   50.88 1494.65   59.25
 1533.01      65 1604.47      70 1625.67   73.85 1664.08      80 1792.43    90.4
 1838.32   91.83 2235.35      95 2257.44   96.87 2351.04     110  2367.3  110.31
#Mann= 3 ,-1 , 0
       0     .06       0  614.42    .035       0 1625.67     .06       0
Bank Sta=1282.42,1494.65
XS Rating Curve= 0 ,0
Exp/Cntr=0.3,0.1

Type RM Length L Ch R = 1 ,84000.  ,455.68,446.09,151.22
XS GIS Cut Line= 6
 6451085.8127514 2049558.9672916 6450742.6558566 2049935.6028732
 6450550.1532417  2050027.669333 6450206.9963942 2050019.2996849
 6450031.2330754  2050186.693261 6449462.0948789 2051308.2303579
#Sta/Elev= 30
       0  120.02  105.73     115  347.08  105.01  493.38     100  509.52    96.3
  528.35   91.17  554.05   82.81  578.07      75  621.45      65  665.66      60
  819.62      60  823.03   58.98  836.19      55 1010.56      55  1048.5   58.13
 1072.21      60 1401.33   62.61 1633.01    63.7 1731.28      65 1817.88   70.82
 1850.78   73.67 1860.48      75 1984.53      80 2167.85      85 2334.97      90
 2432.27      95 2477.86     100 2512.09     105 2541.24     110 2566.57  110.47
#Mann= 3 ,-1 , 0
       0     .06       0  554.05    .035       0 1817.88     .06       0
Bank Sta=823.03,1048.5
XS Rating Curve= 0 ,0
Exp/Cntr=0.3,0.1

Type RM Length L Ch R = 1 ,83554.  ,237.02,192.39,113.07
XS GIS Cut Line= 5
  6450851.461707 2049232.5497401 6450499.9351642 2049567.3369396
 6450257.2144718 2049592.4459784 6450098.1905437  2049734.730563
 6449353.2890285 2051207.7942028
#Sta/Elev= 30
       0  119.79   31.16  116.98   45.27     115  373.71     110  379.25  109.35
  457.95     100  471.39   84.69  477.01      75  515.96      65  527.23      60
  558.46   56.67  573.81      55  658.07   54.92  739.01   57.71  800.42      60
 1032.95      60 1417.84   62.02 1780.26      65 1872.06   68.45 1900.44      70
 1936.99   73.53 1993.11   77.51 2036.74      80 2049.02      80 2345.54   89.06
 2469.33      95 2516.32     100  2547.2     105 2574.57     110 2593.54  110.09
#Mann= 3 ,-1 , 0
       0     .06       0  379.25    .035       0 1936.99     .06       0
Bank Sta=558.46,739.01
XS Rating Curve= 0 ,0
Exp/Cntr=0.3,0.1

Type RM Length L Ch R = 1 ,83362.  ,399.14,398.4,400
XS GIS Cut Line= 3
 6450767.7649427 2048939.6109702 6450031.2330754 2049659.4034467
  6449244.483178 2051132.4670865
#Sta/Elev= 30
       0     120   81.88     115  294.26     115  387.53  113.55  449.01  112.16
  497.14     110  511.03  108.31  576.33     100   583.1   95.13  607.54      75
   617.2   61.24  628.61      55  634.29   52.11  640.13      50  716.26      50
  728.51      55  807.44    57.5  888.13      60 1100.11      60 1659.22   62.97
 1942.38      65  2047.3      70 2103.62   74.69 2190.95      80 2512.34      90
 2582.84      95 2623.74   99.71  2659.2     105 2686.72     110 2699.84  110.18
#Mann= 3 ,-1 , 0
       0     .06       0  511.03    .035       0 2103.62     .06       0
Bank Sta=628.61,807.44
XS Rating Curve= 0 ,0
Exp/Cntr=0.3,0.1

Type RM Length L Ch R = 1 ,82964.  ,397.22,364.75,139.76
XS GIS Cut Line= 3
 6450474.8261254 2048596.4540753 6449512.3129565 2049701.2518289
 6449026.8715244 2051040.4006267
#Sta/Elev= 30
       0  117.92  291.48     115  527.02  110.06  588.12     110  592.41  107.82
  600.95     100  613.91    89.5  639.73      75  669.93   63.66  707.41      50
  714.56      45  794.65      50  802.97      55  894.51      55  985.77   57.64
 1081.78      60  2102.7      65 2236.43      70 2263.97   73.59 2285.11      75
 2323.45   79.04 2377.87   81.07  2385.3   81.93 2420.67      85 2577.61    86.1
 2737.49      90 2786.39      95 2814.45     100 2853.31  103.58 2889.69   109.9
#Mann= 3 ,-1 , 0
       0     .06       0  527.02    .035       0  2385.3     .06       0
Bank Sta=669.93,985.77
XS Rating Curve= 0 ,0
Exp/Cntr=0.3,0.1

Type RM Length L Ch R = 1 ,82599.  ,622.27,679.05,407.5
XS GIS Cut Line= 5
  6450014.493732 2048470.9088815 6449780.1426877 2048780.5870421
 6449713.1852667 2048872.6535492 6449520.6826045 2049332.9859426
 6448867.8475963 2050973.4431584
#Sta/Elev= 30
       0     120  138.53     120  274.98  116.63  382.64     115  394.53  112.82
  401.58     110  421.14  106.15  439.41     100  504.14      75  516.55   60.62
   521.6      55  532.42      50  541.03      45  645.11      45  660.83      50
  686.82   53.32  764.93      55  824.34      55  901.95   57.56  978.12      60
 1997.17      65 2116.78      70 2222.72      80 2285.19      85 2307.05   85.33
 2615.41      90 2664.64      95 2675.77   97.04  2745.2     105 2766.74  108.55
#Mann= 3 ,-1 , 0
       0     .06       0  421.14    .035       0 2307.05     .06       0
Bank Sta=516.55,901.95
XS Rating Curve= 0 ,0
Exp/Cntr=0.3,0.1

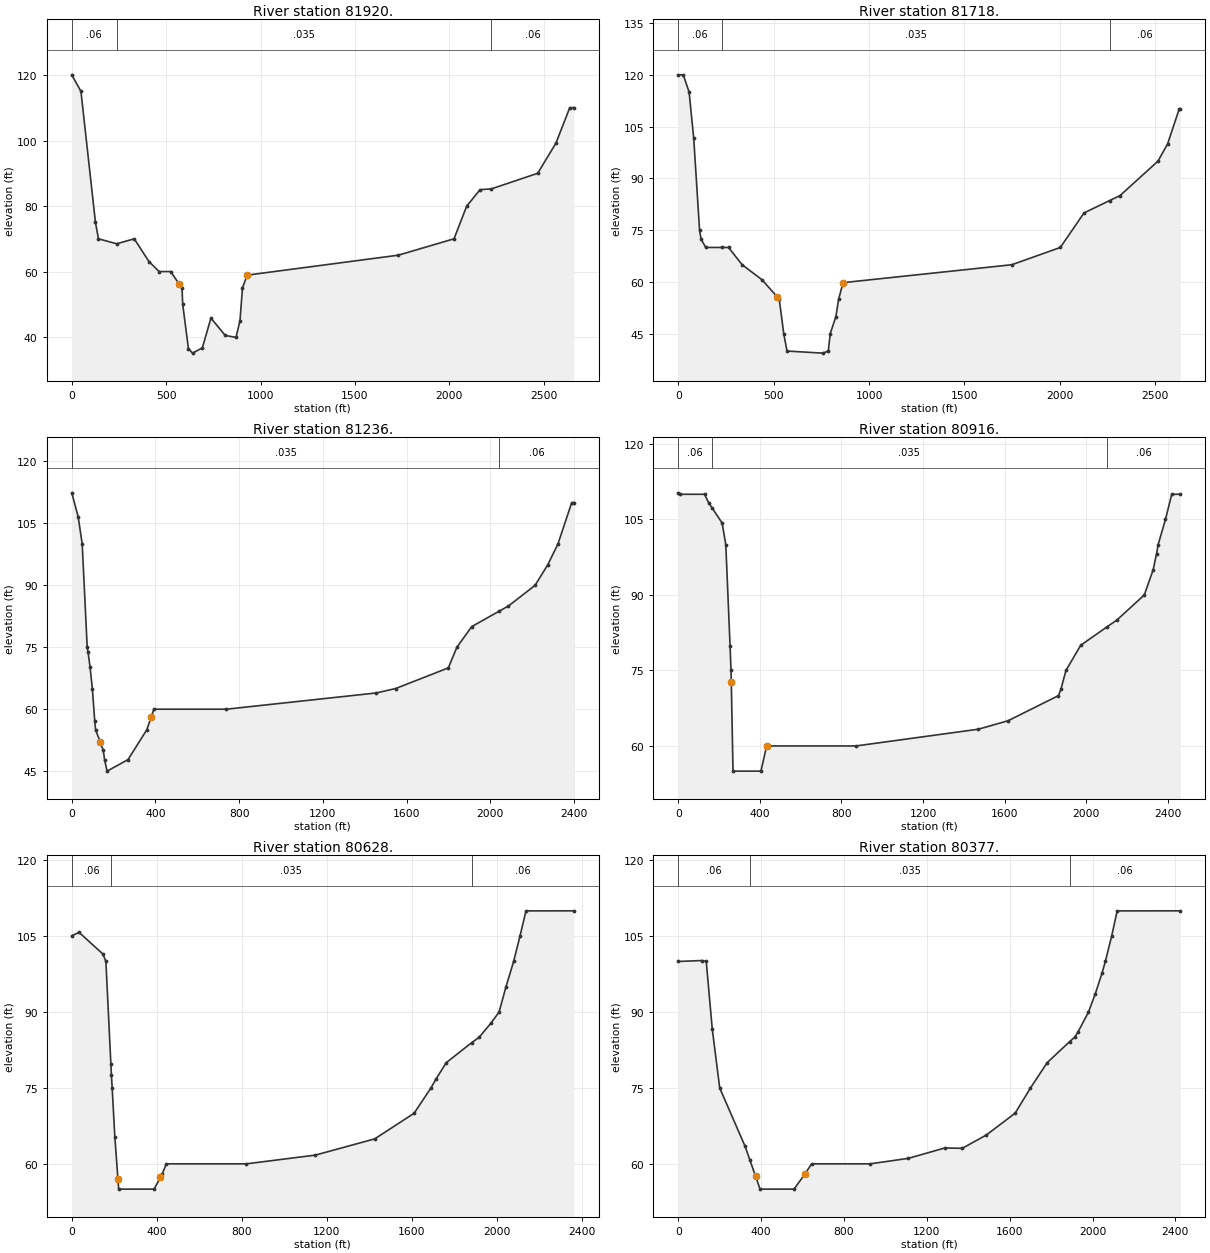
Type RM Length L Ch R = 1 ,81920.  ,111.46,201.87,246.87
XS GIS Cut Line= 4
 6449199.0808431 2048337.9254362 6449132.9930003 2048860.6202276
 6449018.8412631 2049209.0833903 6448664.3700545 2050939.3833486
#Sta/Elev= 30
       0  120.06   48.63     115  125.47      75   141.4      70  238.11   68.48
  330.88      70  409.28   63.04  463.08      60  524.31      60  569.99   56.09
  583.97      55  587.72      50  618.05    36.5  639.65    35.1  691.62    36.7
  737.27    45.8  812.88    40.5  870.18    39.9  891.07      45  904.39      55
  928.89   58.91 1729.83      65 2024.92      70 2092.42      80  2163.1      85
 2222.53   85.24 2468.37      90 2565.24   99.24 2637.94     110 2659.78  110.07
#Mann= 3 ,-1 , 0
       0     .06       0  238.11    .035       0 2222.53     .06       0
Bank Sta=569.99,928.89
XS Rating Curve= 0 ,0
Exp/Cntr=0.3,0.1

Type RM Length L Ch R = 1 ,81718.  ,541.42,481.91,140.1
XS GIS Cut Line= 5
 6449093.8289453 2048320.2546488 6449035.2411724 2048755.4780034
 6448867.8475963 2049023.3077819  6448725.563059 2049383.2040201
 6448457.7332805 2050847.8979646
#Sta/Elev= 30
       0     120   26.46     120   56.93     115   81.01  101.74   111.8      75
  119.89   72.39  144.32      70   228.9      70  263.46      70  335.06      65
  439.15   60.64  518.74   55.69  529.43      55  552.95      45  570.02      40
  757.67    39.4  786.41      40  796.25      45  826.34      50  840.37      55
  863.79   59.81 1747.77      65 2002.27      70 2126.29      80 2259.93   83.57
 2314.41      85 2513.95      95 2564.42     100 2624.52     110 2630.97  110.02
#Mann= 3 ,-1 , 0
       0     .06       0   228.9    .035       0 2259.93     .06       0
Bank Sta=518.74,863.79
XS Rating Curve= 0 ,0
Exp/Cntr=0.3,0.1

Type RM Length L Ch R = 1 ,81236.  ,440.39,320.31,102.46
XS GIS Cut Line= 5
 6448507.9513581  2048454.169538 6448533.0603969 2048579.7147319
 6448466.1029759 2048830.8051197 6448558.1694356 2049433.4220977
 6448374.0364688 2050822.7889258
#Sta/Elev= 30
       0   112.4   30.82  106.55   49.91     100   73.73      75   77.76   73.88
    87.2   70.23   98.31      65  109.88   57.08  113.92      55  135.91   52.08
  150.43      50  157.35   47.62  168.72      45  268.63   47.78  358.38      55
  378.83      58  392.19      60  738.89      60 1454.62   63.93  1547.2      65
 1799.24      70 1840.13      75 1911.06      80 2043.25   83.77 2086.67      85
 2213.84      90 2274.71      95  2322.9     100 2388.64     110 2399.02  110.04
#Mann= 2 ,-1 , 0
       0    .035       0 2043.25     .06       0
Bank Sta=135.91,378.83
XS Rating Curve= 0 ,0
Exp/Cntr=0.3,0.1

Type RM Length L Ch R = 1 ,80916.  ,268.79,287.24,282.69
XS GIS Cut Line= 4
 6448005.7705825 2048479.2785768 6448357.2971254 2049040.0471253
 6448457.7332805 2049458.5311365 6448265.2306657 2050814.4192304
#Sta/Elev= 30
       0  110.29    8.47     110  129.04     110  149.46  108.28  164.82  107.37
  215.07  104.31  233.22     100   254.2    79.8   258.8      75  260.09   72.68
  268.63      55  405.54      55  433.32      60  437.01      60  871.29      60
 1471.76   63.33 1616.64      65  1864.3      70 1876.33   71.27 1900.96      75
 1973.22      80 2100.85   83.62 2150.22      85 2285.17      90 2328.56      95
 2344.98   98.14 2352.99     100 2388.83     105 2419.68     110 2461.69  110.01
#Mann= 3 ,-1 , 0
       0     .06       0  164.82    .035       0 2100.85     .06       0
Bank Sta=260.09,437.01
XS Rating Curve= 0 ,0
Exp/Cntr=0.3,0.1

Type RM Length L Ch R = 1 ,80628.  ,325.53,251.41,128.32
XS GIS Cut Line= 4
 6447846.7466545 2048638.3025049 6447905.3344274 2048855.9141585
 6448189.9035494 2049324.6162472 6448039.2493167 2050906.4857375
#Sta/Elev= 30
       0  105.08   34.41  105.75  146.67  101.46  160.56     100  184.02   79.75
  186.53   77.58  190.12      75  202.62   65.37  217.24   56.98   220.7      55
   387.4      55  417.29   57.33  425.24   57.95  444.96      60  821.95      60
  1145.8   61.72  1425.5   64.93    1611      70 1690.33      75 1712.83   76.68
 1762.35      80 1882.66   83.98  1916.9      85 1974.02   87.89 2010.84      90
 2043.37      95 2079.35     100 2109.24     105 2137.45     110 2362.71  110.01
#Mann= 3 ,-1 , 0
       0     .06       0  184.02    .035       0 1882.66     .06       0
Bank Sta=217.24,417.29
XS Rating Curve= 0 ,0
Exp/Cntr=0.3,0.1

Type RM Length L Ch R = 1 ,80377.  ,516.77,799.69,219.65
XS GIS Cut Line= 5
  6447511.959455   2048738.73866 6447645.8743443 2049031.6774299
 6447913.7040755 2049199.0710533 6448064.3583555 2049550.5975962
 6447938.8131616 2050948.3341197
#Sta/Elev= 30
       0     100  114.55  100.19  135.22     100  164.27   86.65   200.2      75
   322.8   63.45  346.07   60.73  373.35   57.54  395.05      55  559.03      55
  611.93      58   643.9      60     927      60 1110.39   61.08  1286.4   63.13
 1371.31   63.07 1487.32    65.7  1626.2      70 1700.51      75 1781.03      80
 1889.74   84.17 1913.08      85 1929.27   86.02 1980.52      90 2013.71   93.66
 2045.56   97.66 2061.88     100 2092.26     105 2118.93     110 2423.75  110.01
#Mann= 3 ,-1 , 0
       0     .06       0  346.07    .035       0 1889.74     .06       0
Bank Sta=373.35,611.93
XS Rating Curve= 0 ,0
Exp/Cntr=0.3,0.1

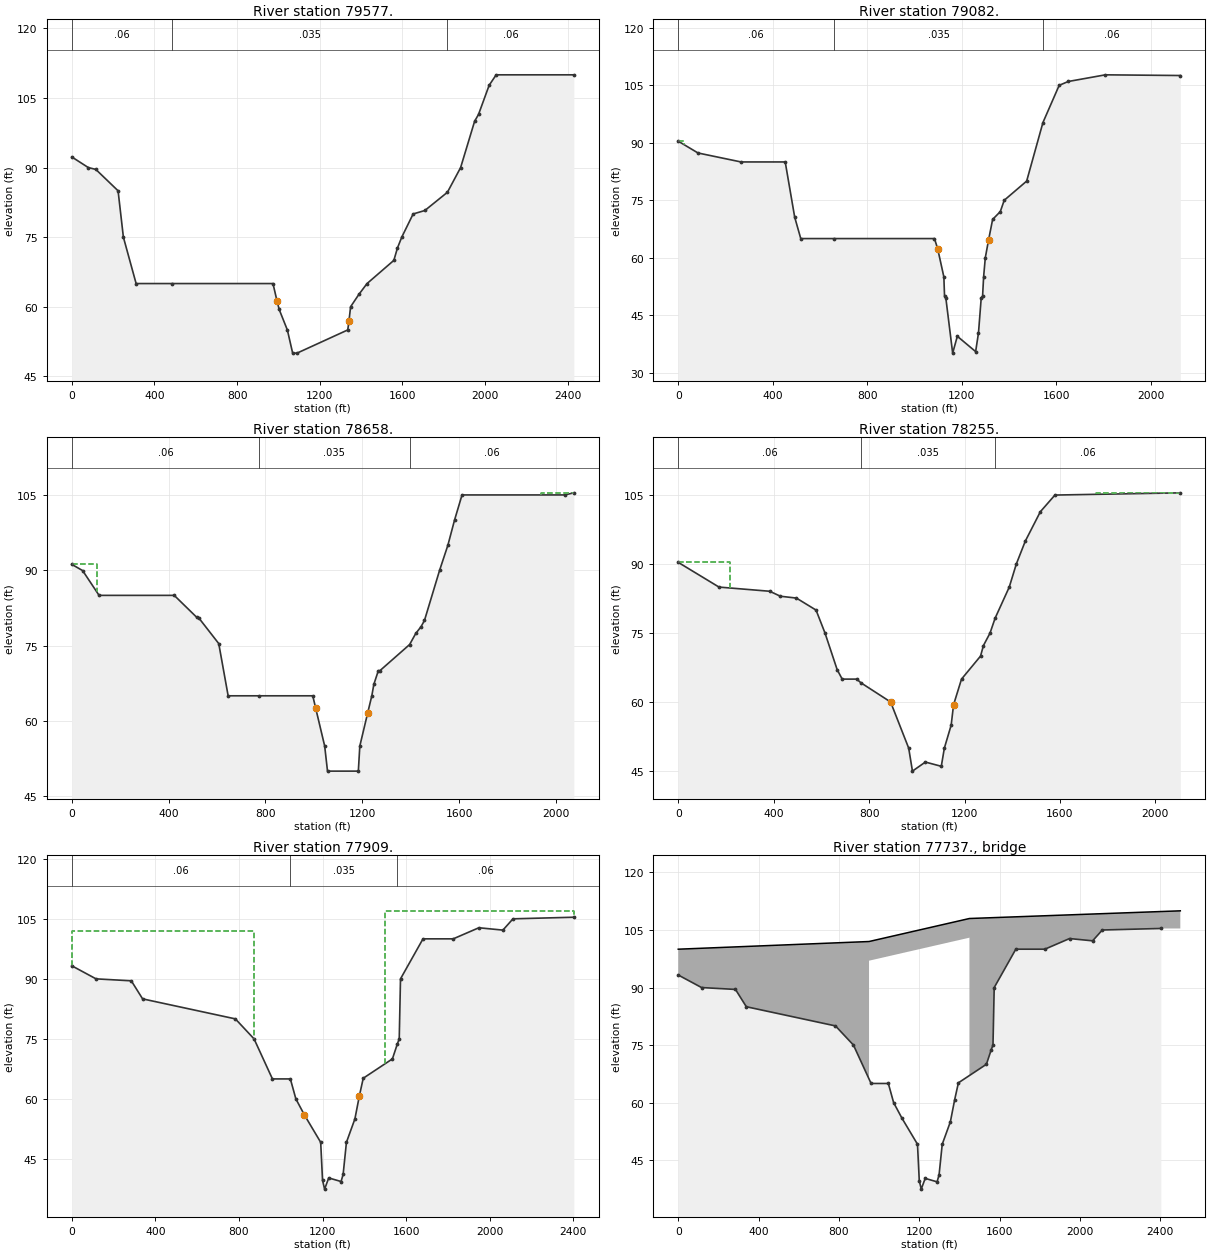
Type RM Length L Ch R = 1 ,79577.  ,278.49,494.98,712.96
XS GIS Cut Line= 4
 6447101.8451392 2048881.0231973 6447461.7413775 2049776.5789452
 6447863.4859979 2050010.9299896 6447779.7892335 2051006.9218926
#Sta/Elev= 30
       0    92.3   80.32      90  116.36   89.61  224.09      85  249.79      75
  311.41      65  484.96      65  973.72      65  992.95   61.31 1003.71   59.42
 1043.49   54.97 1068.99      50 1090.19      50 1335.59      55 1341.32   56.85
  1349.4      60 1389.59   62.67 1428.98      65 1558.74      70 1575.98   72.65
 1596.95      75 1651.93      80 1708.71   80.75 1817.95   84.68 1881.78      90
 1949.64     100 1968.45  101.46 2019.82  107.74 2053.84     110 2429.77     110
#Mann= 3 ,-1 , 0
       0     .06       0  484.96    .035       0 1817.95     .06       0
Bank Sta=992.95,1341.32
XS Rating Curve= 0 ,0
Exp/Cntr=0.3,0.1

Type RM Length L Ch R = 1 ,79082.  ,294.13,424.18,452.06
XS GIS Cut Line= 3
 6446836.2047607 2048847.3157912 6447219.0206851 2049818.4273274
 6447076.7361005 2050889.7463467
#Sta/Elev= 30
       0   90.42    83.7   87.34  265.65      85   452.7      85  492.79   70.59
  518.45      65  658.96      65 1084.34      65 1098.19   62.25    1124      55
 1126.88      50 1132.35    49.5 1161.25    35.1    1181    39.5 1258.46    35.5
 1270.54   40.37 1282.19   49.57 1287.89      50 1292.24      55 1299.38      60
 1313.51   64.73 1330.37      70 1362.85   72.04 1379.47      75 1474.37      80
 1543.29   95.29 1611.99     105 1650.42     106 1807.43  107.74 2124.57  107.56
#Mann= 3 ,-1 , 0
       0     .06       0  658.96    .035       0 1543.29     .06       0
#XS Ineff= 1 ,-1
       0   23.6290.41933
Permanent Ineff=
       F
Bank Sta=1098.19,1313.51
XS Rating Curve= 0 ,0
Exp/Cntr=0.3,0.1

Type RM Length L Ch R = 1 ,78658.  ,320.74,403.16,436.63
XS GIS Cut Line= 5
 6446671.2085714 2048795.2117264 6446817.2760647 2049492.0098233
 6446825.6457127 2049768.2092498  6446733.579253 2050052.7783717
 6446574.5553249 2050822.7889258
#Sta/Elev= 30
       0   91.18    44.9   89.93  112.79      85  423.17      85  516.52   80.61
  526.33    80.4  607.02    75.4  645.84      65   774.2      65  995.29      65
 1007.46   62.53 1044.53      55 1056.22      50 1183.56      50 1189.66      55
 1221.87   61.53 1239.19      65 1247.62   67.28 1266.11      70 1272.52      70
 1395.38   75.21 1420.73   77.42 1442.52   78.76 1456.64      80  1519.2      90
 1553.49      95 1580.94     100  1611.8     105 2035.27     105 2073.62  105.42
#Mann= 3 ,-1 , 0
       0     .06       0   774.2    .035       0 1395.38     .06       0
#XS Ineff= 2 ,-1
       0  102.5791.18344 1937.05 2073.62105.4164
Permanent Ineff=
       F       F
Bank Sta=1007.46,1221.87
XS Rating Curve= 0 ,0
Exp/Cntr=0.3,0.1

Type RM Length L Ch R = 1 ,78255.  ,371.53,345.87,293.02
XS GIS Cut Line= 6
 6446540.9484569 2048717.0556293 6446541.0765908 2049299.5072084
 6446474.1191698 2049634.2944079 6446356.9436713 2049835.1667181
  6446223.028782 2050153.2145268 6446080.7441974 2050739.0921141
#Sta/Elev= 30
       0   90.37  170.83      85  383.49   84.09  428.19   83.01  495.25   82.61
  577.63      80  615.27      75  666.07   67.06  687.19      65  748.15      65
  765.38   64.21  890.03   60.03  965.94      50  981.69      45 1035.82   46.97
 1102.62   46.05 1115.43      50 1144.02      55 1154.02   59.42 1187.34      65
 1267.06      70 1279.22   72.29 1306.82      75 1328.17   78.24 1387.46      85
 1416.97      90  1454.8      95 1517.79  101.38 1578.91     105 2104.42  105.48
#Mann= 3 ,-1 , 0
       0     .06       0  765.38    .035       0 1328.17     .06       0
#XS Ineff= 2 ,-1
       0  217.28 90.3664 1749.17 2104.42105.4847
Permanent Ineff=
       F       F
Bank Sta=890.03,1154.02
XS Rating Curve= 0 ,0
Exp/Cntr=0.3,0.1

Type RM Length L Ch R = 1 ,77909.  ,223.16,229.2,233.35
XS GIS Cut Line= 6
 6446531.4068593 2048445.6703834 6446341.9149889 2048655.0393395
 6446207.5434658 2049102.9444007 6446140.3577043 2049409.0128963
 6446028.3814508 2049909.1735866  6445838.023505 2050713.9830753
#Sta/Elev= 30
       0   93.27   116.2      90  284.95   89.51  339.02      85  782.96      80
  872.49      75   960.3      65 1046.17      65 1072.56      60 1113.82   55.96
 1191.33   49.16  1200.2   39.66 1210.06   37.46 1229.77   40.26 1288.92   39.36
 1298.77   41.16 1314.55   49.16 1355.03      55 1376.69   60.82 1395.01   65.17
 1534.57      70 1558.66    73.8 1567.25      75 1573.32      90 1680.99     100
 1825.76     100  1948.4  102.77  2063.4  102.18 2111.57     105 2402.93   105.4
#Mann= 3 ,-1 , 0
       0     .06       0 1046.17    .035       0 1558.66     .06       0
#XS Ineff= 2 ,-1
       0  872.45     102 1498.38 2402.93     107
Permanent Ineff=
       F       F
Bank Sta=1113.82,1376.69
XS Rating Curve= 0 ,0
Exp/Cntr=0.3,0.1

Type RM Length L Ch R = 3 ,77737.  ,,,
Node Name=County Road
Bridge Culvert--1,0,-1,-1, 0
Deck Dist Width WeirC Skew NumUp NumDn MinLoCord MaxHiCord MaxSubmerge Is_Ogee
140,20,2.6,0, 6, 6, , , 0.95, 0, 0,0,,
       0     950     950    1450    1450    2500
     100     102     102     108     108     110
                      97     103
       0    1000    1000    1500    1500    2500
     100     102     102     108     108     110
                      97     103
BR Coef=-1 , 0 , 0 ,, 0 ,,,0.8,-1,,0,
WSPro=,,,, 1 ,,,, 0 ,,,, 0 ,,,,-1 ,-1 ,-1 , 0 , 0 , 0 , 0 , 0
BC Design=,, 0 ,, 0 ,,,,,,
BC HTab HWMax=120
BC HTab MaxFlow=160000
BC Use User HTab Curves=0
BC User HTab FreeFlow(D)= 0

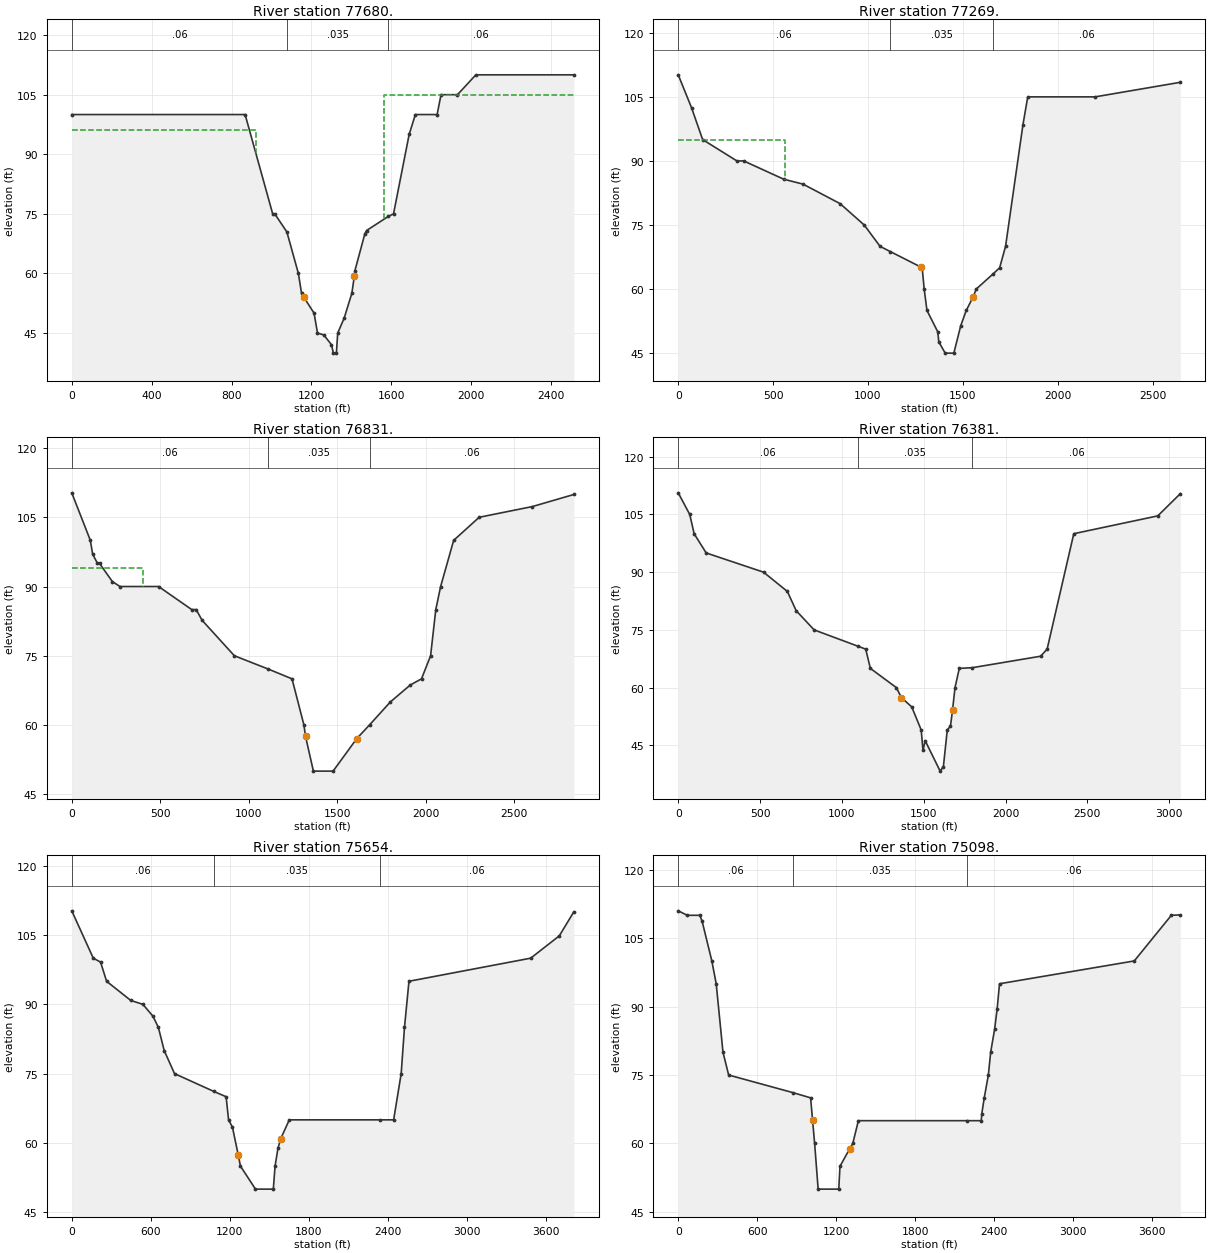
Type RM Length L Ch R = 1 ,77680.  ,408.31,410.92,414.55
XS GIS Cut Line= 5
 6446319.8612835 2048318.7430758 6446173.8418345 2048523.3930405
 6446005.9861812 2049013.3634169 6445796.9638067 2049871.8481846
 6445587.3130695 2050715.9878716
#Sta/Elev= 30
       0     100  867.88     100 1005.91      75 1016.29      75 1076.95   70.45
 1134.55      60 1150.43      55 1161.22   54.07 1213.08      50 1230.27      45
 1262.02   44.51 1300.26   42.05 1309.84   39.94 1324.93      40 1331.52      45
 1363.94   48.76 1402.25      55 1414.54   59.25 1417.52   60.68 1467.46      70
 1476.16   70.81 1585.57   74.38 1610.91      75 1689.22      95 1720.29     100
 1829.22     100 1848.79     105 1931.11     105  2023.1     110 2513.74     110
#Mann= 3 ,-1 , 0
       0     .06       0 1076.95    .035       0 1585.57     .06       0
#XS Ineff= 2 ,-1
       0  923.89      96 1565.59 2513.74     105
Permanent Ineff=
       F       F
Bank Sta=1161.22,1414.54
XS Rating Curve= 0 ,0
Exp/Cntr=0.3,0.1

Type RM Length L Ch R = 1 ,77269.  ,369.89,438.25,476.48
XS GIS Cut Line= 4
 6446013.7867765 2048111.0126432 6445628.7814994 2048872.6535492
  6445386.060807 2049793.3182886 6445168.4491061 2050605.1772722
#Sta/Elev= 30
       0  110.16   70.28  102.43  128.63      95  309.24      90   345.1      90
  556.11   85.72  657.66   84.57  853.12      80  980.13      75 1063.76      70
 1117.42   68.78 1281.96   65.08 1285.71      65 1296.19      60 1310.84      55
 1367.65      50 1373.26   47.64 1406.93      45 1452.49      45 1488.87   51.42
 1518.02      55 1554.06   58.16 1570.52      60  1661.1   63.62 1693.99      65
 1725.11      70 1816.77   98.49 1841.94     105 2196.92     105 2646.06  108.41
#Mann= 3 ,-1 , 0
       0     .06       0 1117.42    .035       0  1661.1     .06       0
#XS Ineff= 1 ,-1
       0   562.3      95
Permanent Ineff=
       F
Bank Sta=1281.96,1554.06
XS Rating Curve= 0 ,0
Exp/Cntr=0.3,0.1

Type RM Length L Ch R = 1 ,76831.  ,368.31,450.26,475.75
XS GIS Cut Line= 5
 6445863.1325438 2048052.4249176 6445402.8001504 2048730.3689646
  6445160.079458 2049081.8955075 6444967.5767959  2049508.749214
 6444523.9837459 2050538.2198039
#Sta/Elev= 30
       0   110.3  104.89     100  117.81   97.03  145.26      95   156.9      95
   229.7   91.05  272.69      90  490.42      90   677.7      85  702.71      85
  736.24   82.68  918.41      75 1108.13   72.14 1244.02      70 1311.25      60
 1320.31   57.52 1364.81      50 1476.01      50 1609.42   57.03  1683.7   60.09
 1799.68      65 1912.33   68.67 1975.43      70 2026.73      75 2056.09      85
 2083.41      90 2157.02     100 2301.11     105  2602.1  107.33 2835.87  109.94
#Mann= 3 ,-1 , 0
       0     .06       0 1108.13    .035       0  1683.7     .06       0
#XS Ineff= 1 ,-1
       0   401.2      94
Permanent Ineff=
       F
Bank Sta=1320.31,1609.42
XS Rating Curve= 0 ,0
Exp/Cntr=0.3,0.1

Type RM Length L Ch R = 1 ,76381.  ,406.22,726.54,924.94
XS GIS Cut Line= 5
 6445696.4249835 2047941.3983319 6444717.1232435 2048992.7959133
 6444590.9555565 2049257.1472846 6444542.8916622 2049329.2431261
 6443827.9413409  2050356.608713
#Sta/Elev= 30
       0  110.62   70.32     105   97.15     100  170.71      95   521.4      90
  666.67      85  720.62      80  830.46      75  1095.7    70.8  1145.6      70
 1174.11      65 1333.04      60 1363.52    57.4 1426.81      55 1484.67      49
 1495.53    43.7 1509.22    46.2 1600.39    38.3 1620.35    39.5 1643.98      49
 1663.59      50 1676.12   54.15 1691.28      60  1717.5      65 1797.02   65.18
  2214.4   68.16 2254.17      70 2417.06     100 2930.34  104.63 3068.04   110.4
#Mann= 3 ,-1 , 0
       0     .06       0  1095.7    .035       0 1797.02     .06       0
Bank Sta=1363.52,1676.12
XS Rating Curve= 0 ,0
Exp/Cntr=0.3,0.1

Type RM Length L Ch R = 1 ,75654.  ,702.34,556.08,316.91
XS GIS Cut Line= 5
 6445586.9331172 2047726.0074135 6444666.2683305 2048462.5392334
 6444222.6752806 2048487.6482722 6443938.1061587 2048646.6721529
  6443168.095652  2050345.717189
#Sta/Elev= 30
       0  110.25  163.41     100  218.79   99.15  264.58      95  448.24   90.85
  540.65      90  617.45   87.41  658.12      85  702.24      80  780.86      75
 1077.93   71.17 1172.71      70 1191.44      65 1220.93    63.4 1264.11   57.49
 1281.32      55 1395.81      50 1531.39      50 1544.69      55 1566.41    58.8
 1586.98   60.88 1652.69      65 2345.48      65 2445.57      65 2502.81      75
 2527.91      85 2562.02      95 3486.77     100  3704.1  104.83 3814.71  110.03
#Mann= 3 ,-1 , 0
       0     .06       0 1077.93    .035       0 2345.48     .06       0
Bank Sta=1264.11,1586.98
XS Rating Curve= 0 ,0
Exp/Cntr=0.3,0.1

Type RM Length L Ch R = 1 ,75098.  ,801.59,595.15,292.73
XS GIS Cut Line= 4
 6444693.0913437 2047106.2882748 6444440.7559223 2047731.1188535
 6443671.7337081 2048458.0851247 6442896.7034953 2050392.6566574
#Sta/Elev= 30
       0  110.98   69.08     110  163.78     110  181.12  108.75  255.36     100
  288.61      95  340.07      80  383.23      75  871.16   71.15 1006.11      70
 1020.87   65.16 1036.75      60 1063.44      50 1220.02      50 1229.41      55
 1303.79   58.88 1326.67      60 1369.29      65 2195.15      65 2303.14      65
 2307.06   66.48 2325.85      70 2357.21      75 2374.71      80 2404.58      85
 2424.08   89.53 2442.06      95  3466.2     100 3747.95     110 3816.14  110.09
#Mann= 3 ,-1 , 0
       0     .06       0  871.16    .035       0 2195.15     .06       0
Bank Sta=1020.87,1303.79
XS Rating Curve= 0 ,0
Exp/Cntr=0.3,0.1

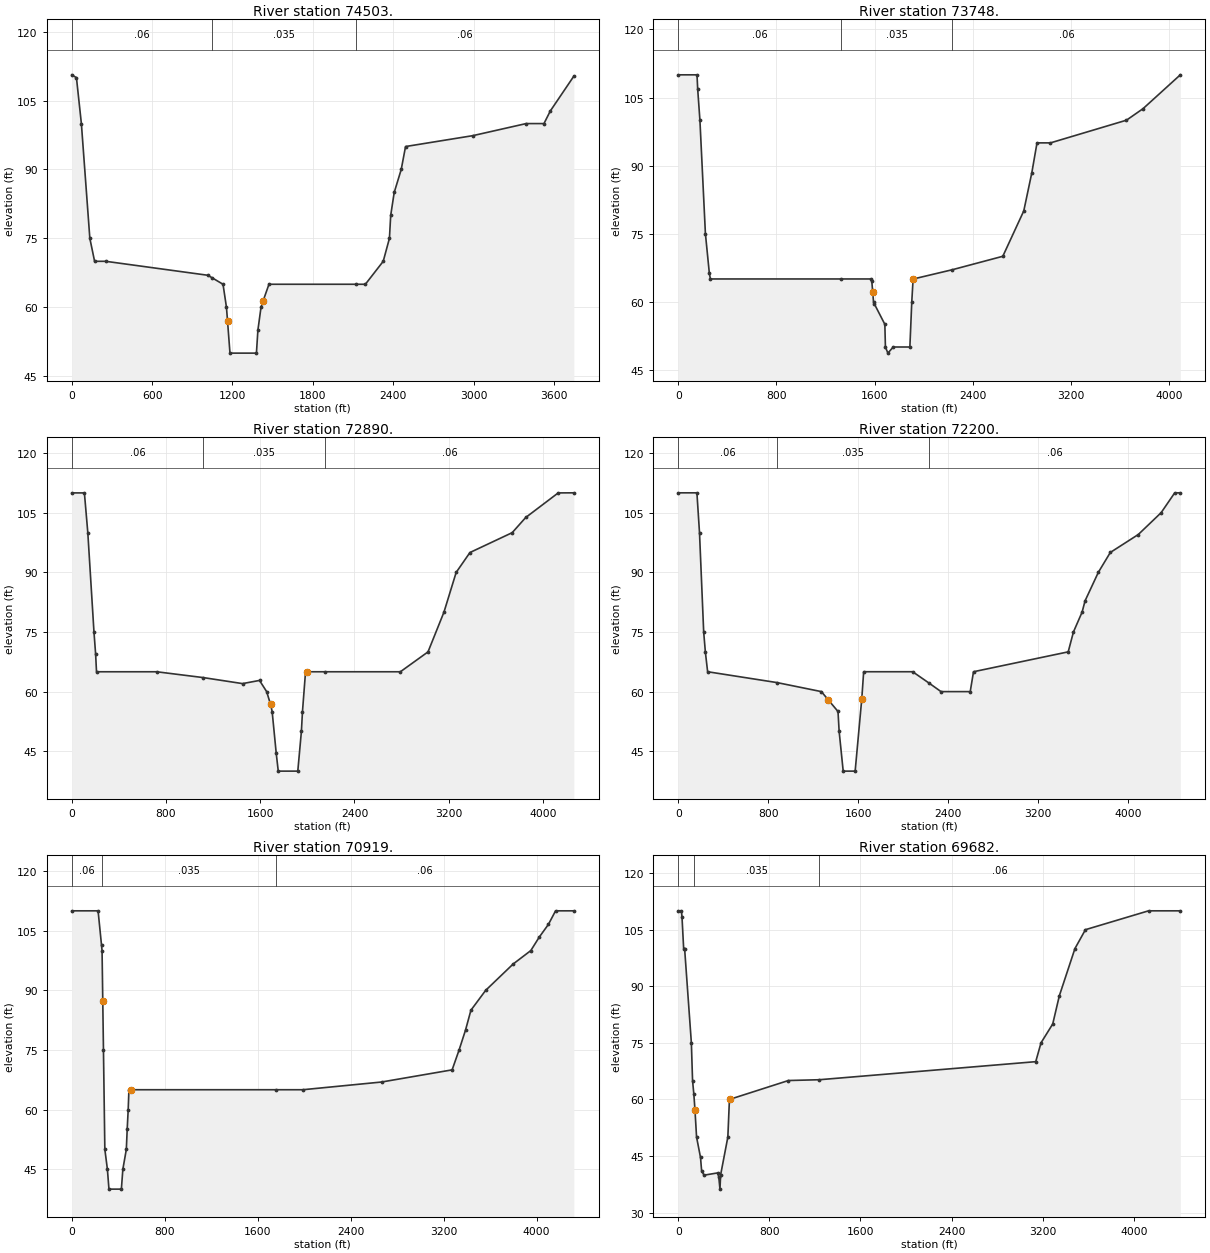
Type RM Length L Ch R = 1 ,74503.  ,743,755.24,661.95
XS GIS Cut Line= 6
 6443804.1913167 2046763.4941973 6443544.7312336 2047366.1111753
 6443494.5131561 2047834.8132167 6443502.8828514  2048136.121682
 6443142.9866132 2049115.3742416  6442657.545181 2050295.4991115
#Sta/Elev= 30
       0  110.62   34.94     110   71.73     100  134.92      75  170.45      70
  253.67      70 1015.89   66.96 1047.74   66.41 1129.35      65 1154.95      60
 1162.81   57.09 1181.29      50 1378.78      50 1389.74      55 1413.09      60
 1427.95   61.31  1472.4      65 2120.74      65 2192.33      65 2325.47      70
 2371.89      75 2381.34      80 2407.53      85 2459.91      90 2492.21      95
 2994.44   97.37 3392.48     100 3525.73     100 3572.98  102.74 3748.81  110.33
#Mann= 3 ,-1 , 0
       0     .06       0 1047.74    .035       0 2120.74     .06       0
Bank Sta=1162.81,1427.95
XS Rating Curve= 0 ,0
Exp/Cntr=0.3,0.1

Type RM Length L Ch R = 1 ,73748.  ,627.58,857.96,978.44
XS GIS Cut Line= 6
 6443140.0269424  2046373.314005 6442824.9387571 2047148.4994743
 6442749.6116408 2047868.2919508 6442749.6116408 2048244.9275325
 6442582.2180647 2049040.0471253 6442088.4069372 2050287.1294161
#Sta/Elev= 30
       0     110  152.91     110  158.55  106.84  176.66     100  221.38      75
  253.57   66.22  262.15      65 1326.93      65  1573.9      65 1577.15   64.53
 1584.31    62.2 1591.06      60  1597.2   59.54 1683.51      55 1688.16      50
 1708.25   48.65 1751.92      50 1887.42      50 1903.01      60 1913.76      65
 1916.01      65 2233.86   67.04 2644.76      70 2815.45      80 2880.94    88.4
 2923.35      95  3033.2      95 3652.25     100 3786.87  102.53 4090.98     110
#Mann= 3 ,-1 , 0
       0     .06       0 1326.93    .035       0 2233.86     .06       0
Bank Sta=1584.31,1916.01
XS Rating Curve= 0 ,0
Exp/Cntr=0.3,0.1

Type RM Length L Ch R = 1 ,72890.  ,381.6,689.77,765.41
XS GIS Cut Line= 6
 6442412.3854003 2046120.8723181 6442322.7579816 2047039.6936238
 6442054.9282031 2047642.3106018 6441854.0558928 2048002.2068401
 6441686.6623168 2048420.6908039 6441653.1835826 2050236.9113385
#Sta/Elev= 30
       0     110  107.22     110  136.15     100  188.47      75  202.35   69.51
  210.04      65  720.61      65 1117.46   63.53 1449.64   62.02 1593.74   62.82
 1654.41      60 1687.43   56.79 1701.02      55 1735.24   44.59 1752.87      40
 1918.72      40 1949.28      50 1958.44      55 1984.45      65 1993.74      65
 2151.03      65  2789.5      65 3024.01      70 3159.41      80 3263.12      90
 3380.03      95 3738.81     100  3853.7  103.82 4129.23     110 4262.05  110.02
#Mann= 3 ,-1 , 0
       0     .06       0 1117.46    .035       0 2151.03     .06       0
Bank Sta=1687.43,1993.74
XS Rating Curve= 0 ,0
Exp/Cntr=0.3,0.1

Type RM Length L Ch R = 1 ,72200.  ,1355.27,1280.43,700.89
XS GIS Cut Line= 6
 6442097.0854888 2046110.3623085 6442054.9282031 2046872.3000478
 6441770.3591285 2047257.3053248 6441310.0267351 2047407.9595574
 6440899.9124193 2048328.6243442 6440899.9124193 2050061.1480671
#Sta/Elev= 30
       0     110  166.13     110  189.17     100  226.38      75  241.51   69.91
  261.47      65  879.03   62.27 1273.71      60 1333.92   57.95 1421.38      55
 1431.42      50 1467.54      40  1573.9      40 1633.05   58.25 1649.63      65
 2085.48      65  2232.5   62.12 2337.79      60 2597.66      60 2626.83      65
 3469.34      70 3515.83      75 3592.92      80 3619.52   82.85 3737.34      90
 3843.94      95  4092.6   99.51 4295.84     105 4416.96     110 4466.62     110
#Mann= 3 ,-1 , 0
       0     .06       0  879.03    .035       0  2232.5     .06       0
Bank Sta=1333.92,1633.05
XS Rating Curve= 0 ,0
Exp/Cntr=0.3,0.1

Type RM Length L Ch R = 1 ,70919.  ,1242.43,1237.3,794.15
XS GIS Cut Line= 5
 6440941.7608015 2045993.4836906 6440939.6020742 2046531.0236493
 6440548.3858291 2047223.8265906 6440355.8832143 2048420.6908039
 6440343.3286949 2050195.0629564
#Sta/Elev= 30
       0     110   226.4     110     256  101.35  260.59     100   266.7   87.35
  272.68      75  284.57      50  306.53      45  319.95      40  426.82      40
  439.55      45   469.5      50  476.79      55   485.5      60   491.8      65
  512.41      65 1759.38      65 1988.03      65 2665.31   66.94 3272.63      70
 3332.51      75 3387.76      80 3434.35      85  3561.2      90 3797.51   96.62
 3949.46     100 4022.04  103.38 4101.08  106.59 4162.66     110 4319.84     110
#Mann= 3 ,-1 , 0
       0     .06       0     256    .035       0 1759.38     .06       0
Bank Sta=266.7,512.41
XS Rating Curve= 0 ,0
Exp/Cntr=0.3,0.1

Type RM Length L Ch R = 1 ,69682.  ,919.69,907.93,730.11
XS GIS Cut Line= 2
   6439700.45495 2046132.9945808 6439798.0847028 2050541.3542801
#Sta/Elev= 30
       0     110   27.99     110   33.09  108.34   47.55     100   56.02     100
  115.28      75  125.73      65  137.06    61.4  146.72   57.31  160.98      50
  195.64    44.6   205.2    41.1   226.4    39.9  346.43    40.5  356.11    39.4
  366.44    36.2  372.38      40  435.69      50  449.67      60  451.53      60
  967.64      65 1239.22   65.21 3139.72      70 3186.18      75 3289.02      80
 3346.89   87.46  3484.1     100 3576.18     105 4130.34     110 4409.44     110
#Mann= 3 ,-1 , 0
       0     .06       0  137.06    .035       0 1239.22     .06       0
Bank Sta=146.72,451.53
XS Rating Curve= 0 ,0
Exp/Cntr=0.3,0.1