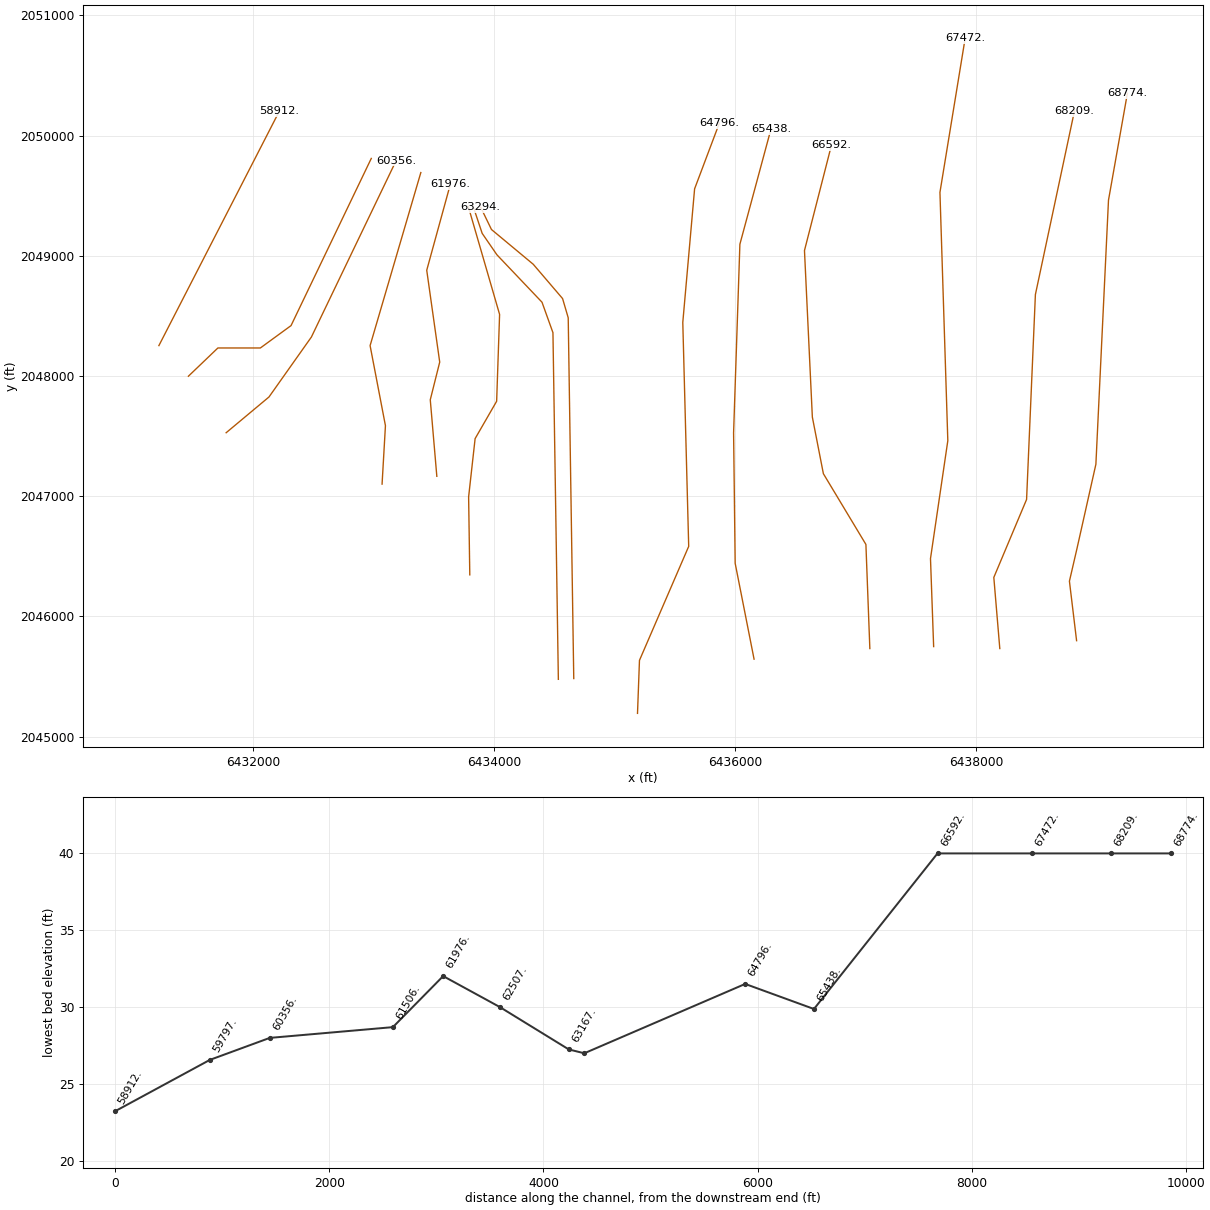
HEC-RAS study Baxter.prj: Baxter River GIS Example

--- Baxter.g02 (geometry) --- (continued)

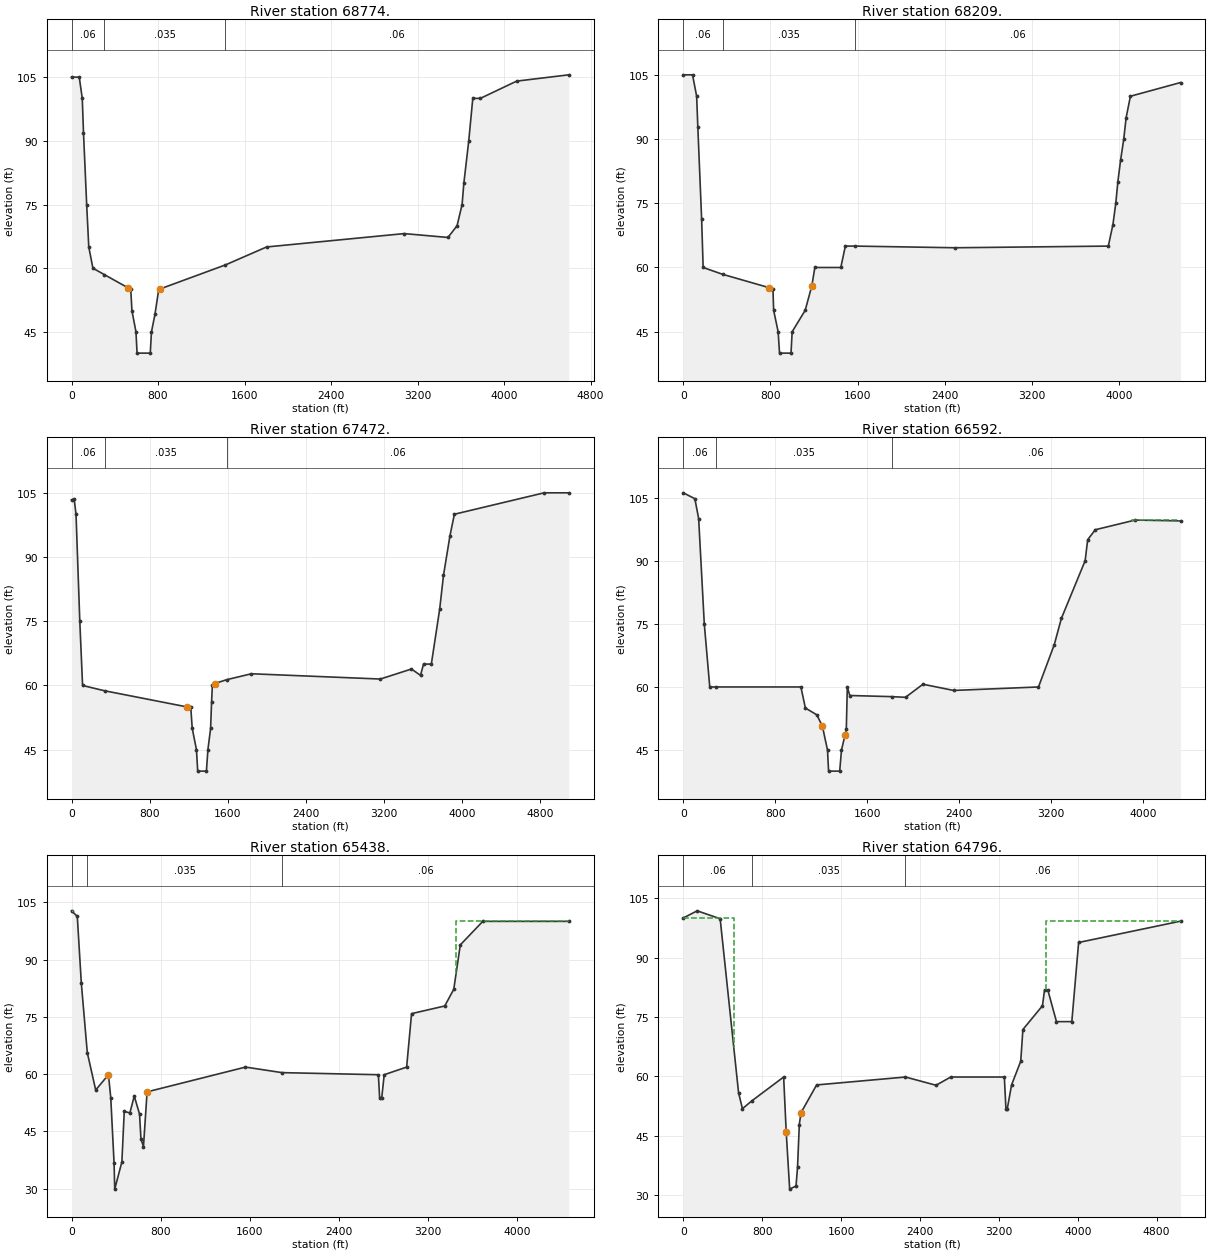
Type RM Length L Ch R = 1 ,68774.  ,628.2,565.13,569.31
XS GIS Cut Line= 6
  6438833.516942 2045797.7116494  6438774.013724 2046292.6997439
 6438836.7863209 2046564.7142991 6438993.7178369 2047265.6750202
 6439098.3388161 2049462.7159605 6439255.2703321  2050351.994425
#Sta/Elev= 30
       0     105   71.38     105   99.34     100  110.64   91.94  140.05      75
  159.52      65  197.91      60  302.31   58.51  517.75   55.45   547.8      55
  558.65      50  596.08      45  606.06      40   728.3      40  739.29      45
  771.36    49.1  806.64      55  814.09   55.07 1423.92   60.78 1803.84      65
 3076.82   68.15 3481.45   67.24 3565.58      70  3612.2      75 3628.32      80
 3673.75      90 3711.14     100 3781.48     100 4117.08  104.06 4598.58  105.54
#Mann= 3 ,-1 , 0
       0     .06       0  302.31    .035       0 1423.92     .06       0
Bank Sta=517.75,814.09
XS Rating Curve= 0 ,0
Exp/Cntr=0.3,0.1

Type RM Length L Ch R = 1 ,68209.  ,565.52,737.02,720.25
XS GIS Cut Line= 5
 6438195.9826936  2045732.323502 6438146.2877546 2046324.0860187
 6438418.3023571 2046972.7362029 6438491.5370141  2048678.058475
 6438815.8621062 2050205.5250637
#Sta/Elev= 30
       0     105   84.56     105  122.31     100  133.16   92.79  167.93   71.38
  181.96      60  360.73   58.41  789.09   55.28     823      55  829.26      50
  870.65      45   883.3      40  988.78      40  999.33      45 1119.03      50
 1180.18   55.74 1207.51      60    1446      60 1487.69      65 1578.91      65
 2494.92   64.61  3902.4      65 3944.46      70 3970.97      75 3989.87      80
 4014.71      85 4044.07      90 4065.91      95 4105.27     100 4565.63   103.2
#Mann= 3 ,-1 , 0
       0     .06       0  360.73    .035       0 1578.91     .06       0
Bank Sta=789.09,1180.18
XS Rating Curve= 0 ,0
Exp/Cntr=0.3,0.1

Type RM Length L Ch R = 1 ,67472.  ,534.71,879.77,1109.7
XS GIS Cut Line= 5
 6437646.7224822 2045748.6705388 6437620.5672137 2046481.0175347
 6437764.4211192 2047461.8393679 6437699.0329718 2049528.1040606
 6437908.2749773 2050809.7113152
#Sta/Elev= 30
       0  103.38   27.01  103.55   46.07     100   84.65      75  113.16      60
  338.23   58.77 1181.41      55 1220.25      55 1235.57      50 1279.08      45
 1291.53      40 1380.76      40 1396.07      45 1423.83      50 1433.46   56.06
  1441.8      60 1463.68   60.44 1588.71   61.36 1841.15   62.74 3161.65   61.51
 3479.73   63.85 3572.55   62.37 3603.36      65 3683.28      65 3768.72   77.82
 3807.64   85.71  3874.2      95 3919.15     100 4837.47     105    5090     105
#Mann= 3 ,-1 , 0
       0     .06       0  338.23    .035       0 1588.71     .06       0
Bank Sta=1181.41,1463.68
XS Rating Curve= 0 ,0
Exp/Cntr=0.3,0.1

Type RM Length L Ch R = 1 ,66592.  ,1087.81,1153.74,728.98
XS GIS Cut Line= 6
 6437117.0786866  2045732.323502 6437084.3846129 2046598.7161244
 6436731.2887492 2047187.2092621 6436639.7453806 2047658.0037629
 6436574.3572332 2049044.2319493 6436798.3247924 2049920.6601026
#Sta/Elev= 30
       0  106.13  100.33  104.73  133.36     100  182.27      75  229.92      60
  285.34      60 1022.66      60 1061.63      55  1162.1   53.36 1210.17   50.61
 1254.26      45 1263.53      40 1360.22      40 1375.82      45 1407.05   48.63
 1417.82      50 1426.41      60  1447.9   57.97 1812.97    57.7 1932.81   57.54
 2084.37   60.65 2351.79   59.17 3089.54      60 3226.19      70  3288.6   76.29
 3495.37      90 3517.51      95 3583.77   97.36 3930.59   99.66 4325.28   99.46
#Mann= 3 ,-1 , 0
       0     .06       0  285.34    .035       0 1812.97     .06       0
#XS Ineff= 1 ,-1
 3905.43 4315.0799.58437
Permanent Ineff=
       F
Bank Sta=1210.17,1407.05
XS Rating Curve= 0 ,0
Exp/Cntr=0.3,0.1

Type RM Length L Ch R = 1 ,65438.  ,808.34,642.22,403.41
XS GIS Cut Line= 5
 6436155.8732693 2045644.0495124 6435998.9417533 2046441.7846557
 6435985.8641427 2047527.2275153 6436038.1746323 2049096.5424862
 6436296.2783515 2050055.3554868
#Sta/Elev= 30
       0  102.76   51.73  101.31   87.81   83.84  141.41   65.64  216.78   55.84
  331.36   59.84     352   53.84  381.76    36.7   387.7   29.88  451.71      37
   473.1   50.24  523.51   49.84   562.9   54.24  610.25   49.55  622.89   43.04
  645.53      41  678.02   55.35 1561.04   61.84  1888.2   60.39 2753.52   59.84
  2764.5   53.84 2783.72   53.84 2805.65   59.84 3006.99   61.84 3051.23   75.84
 3348.82   77.84 3429.95   82.22  3488.6   93.84 3690.07     100 4461.68     100
#Mann= 3 ,-1 , 0
       0     .06       0  141.41    .035       0  1888.2     .06       0
#XS Ineff= 2 ,-1
 3450.41 4461.68     100       0   14.98102.7593
Permanent Ineff=
       F       F
Bank Sta=331.36,678.02
XS Rating Curve= 0 ,0
Exp/Cntr=0.3,0.1

Type RM Length L Ch R = 1 ,64796.  ,1335.46,1502.43,997.04
XS GIS Cut Line= 6
 6435188.1290467 2045192.8714748 6435204.4760363 2045634.2413281
 6435613.1518158 2046582.3690875 6435564.1107526 2048445.9306273
 6435662.1929264 2049557.5287554 6435867.7021031 2050104.3356308
#Sta/Elev= 30
       0  100.04  140.64  101.84  373.46   99.84  560.32   55.84  599.44   51.84
  695.74   53.84 1017.35   59.84 1043.37   45.89 1078.27   31.51 1142.83    32.3
 1157.99      37 1176.17   47.84  1193.1   50.82 1351.52   57.84 2252.87   59.84
 2562.58   57.76 2711.64   59.84 3255.17   59.84 3271.39   51.84 3285.29   51.84
 3328.41   57.84 3421.66   63.84 3443.28   71.84 3641.58   77.84 3663.05   81.84
 3696.08   81.84 3783.79   73.84 3939.56   73.84 4008.51   93.84 5042.14   99.23
#Mann= 3 ,-1 , 0
       0     .06       0  695.74    .035       0 2252.87     .06       0
#XS Ineff= 2 ,-1
       0  511.96100.0435 3681.43 5042.1499.22931
Permanent Ineff=
       F       F
Bank Sta=1043.37,1193.1
XS Rating Curve= 0 ,0
Exp/Cntr=0.3,0.1

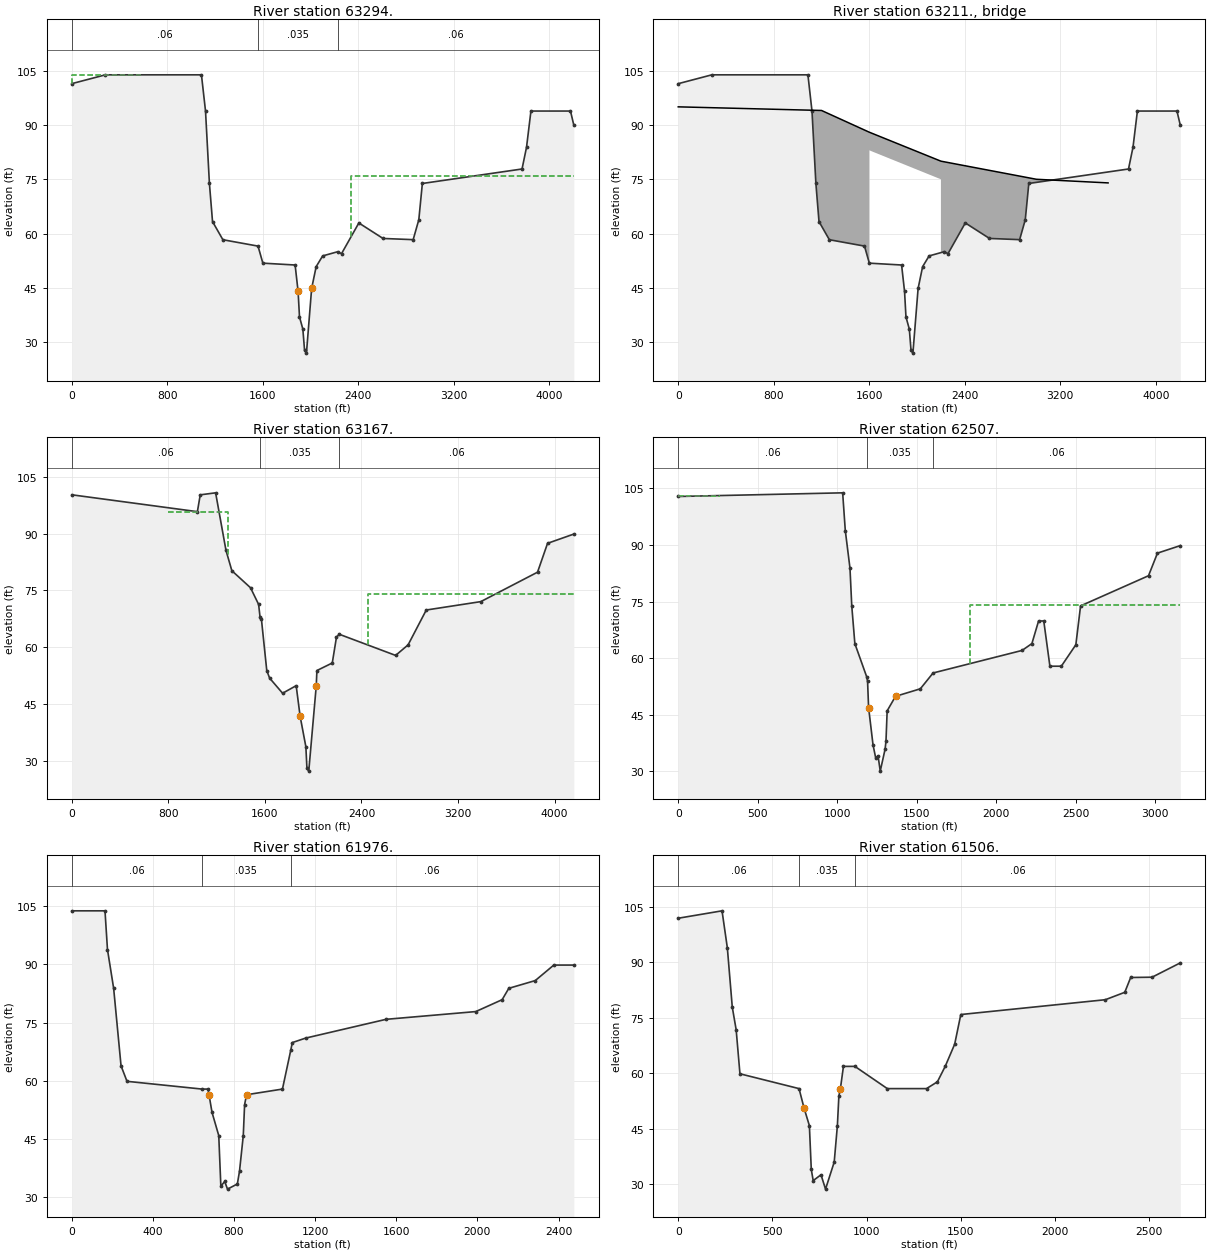
Type RM Length L Ch R = 1 ,63294.  ,172.95,144.74,140.71
XS GIS Cut Line= 6
 6434658.9310454 2045482.6597695 6434612.8921591 2048484.6236115
 6434566.0549328  2048644.421313 6434322.6433492 2048929.7315952
 6433975.6552647  2049219.010289 6433885.7071562 2049405.3313777
#Sta/Elev= 30
       0   101.4  281.47  103.84 1086.07  103.84 1120.13   93.84 1152.78   73.84
 1178.82   63.32 1265.55   58.31 1559.86   56.55 1600.43   51.84  1870.6   51.33
 1895.35   44.05  1907.2      37  1935.3   33.63 1949.65   27.76 1965.43      27
 2008.85   44.85  2046.8   50.88 2101.13   53.84 2228.25   55.01 2259.03   54.45
  2404.3   62.94 2606.77   58.66 2859.26   58.33 2906.53   63.84 2936.13   73.84
 3770.96   77.84 3808.58   83.84 3845.47   93.84 4176.74   93.84 4204.85   89.92
#Mann= 3 ,-1 , 0
       0     .06       0 1559.86    .035       0 2228.25     .06       0
#XS Ineff= 2 ,-1
       0  578.52  103.84 2337.68 4204.85      76
Permanent Ineff=
       F       F
Bank Sta=1895.35,2008.85
XS Rating Curve= 0 ,0
Exp/Cntr=0.3,0.1

Type RM Length L Ch R = 3 ,63211.  ,,,
Node Name=Airport Road
Bridge Culvert--1,0,-1,-1, 0
Deck Dist Width WeirC Skew NumUp NumDn MinLoCord MaxHiCord MaxSubmerge Is_Ogee
60,20,2.6,0, 8, 8, , , 0.95, 0, 0,0,,
       0    1200    1600    1600    2200    2200    3000    3600
      95      94      88      88      80      80      75      74
                              83      75
       0    1200    1600    1600    2200    2200    3000    3600
      95      94      88      88      80      80      75      74
                              83      75
BR Coef=-1 , 0 , 0 ,, 0 ,,,0.8,-1,,0,
WSPro=,,,, 1 ,,,, 0 ,,,, 0 ,,,,-1 ,-1 ,-1 , 0 , 0 , 0 , 0 , 0
BC Design=,, 0 ,, 0 ,,,,,,
BC HTab HWMax=105
BC HTab MaxFlow=160000
BC Use User HTab Curves=0
BC User HTab FreeFlow(D)= 0

Type RM Length L Ch R = 1 ,63167.  ,716.46,642.18,564.83
XS GIS Cut Line= 6
  6434531.034095 2045476.2022372  6434486.156082 2048360.6426263
  6434395.236674 2048614.1148752 6434020.9971537 2049008.5339473
 6433898.5568995  2049186.885978 6433821.4585343  2049418.181121
#Sta/Elev= 30
       0   100.3 1040.58   95.84 1064.27  100.29 1191.62  100.82  1277.5    85.6
 1326.15   80.23 1480.64   75.73 1547.72   71.33 1560.02   67.87 1571.08   67.41
  1615.3   53.84 1638.92   51.84 1746.44   47.84 1858.93   49.84 1891.68   41.74
 1939.21    33.7    1948      28 1963.15   27.25 2024.95   49.68  2030.7   53.84
    2158   55.84 2192.77   62.68 2215.94   63.43 2682.68   57.84 2786.04   60.63
  2936.6   69.84 3388.29   72.06 3858.26   79.84 3941.25   87.47 4159.06   89.92
#Mann= 3 ,-1 , 0
       0     .06       0 1560.02    .035       0 2215.94     .06       0
#XS Ineff= 2 ,-1
  799.35 1293.04   95.84 2451.36 4159.06      74
Permanent Ineff=
       F       F
Bank Sta=1891.68,2024.95
XS Rating Curve= 0 ,0
Exp/Cntr=0.3,0.1

Type RM Length L Ch R = 1 ,62507.  ,394.8,530.9,564.51
XS GIS Cut Line= 6
  6433795.743238 2046345.3534543 6433786.0461947 2046994.0967451
 6433839.9243484 2047479.0001284  6434018.701867 2047790.0240028
 6434043.1919153 2048512.4810681 6433782.9093517 2049411.7562494
#Sta/Elev= 30
       0  102.87 1033.73  103.84 1050.23   93.84 1079.75   83.84 1090.92   73.84
 1110.36   63.84 1184.76   55.03 1190.34   53.84 1196.72   46.88 1224.53      37
 1241.44    33.5 1256.19   34.07    1270      30 1300.76   35.88 1306.09      38
 1313.48      46 1365.98   49.84 1522.02   51.84 1602.11   56.04  2161.4   62.02
 2223.45   63.84 2265.42   69.84 2298.06   69.84 2336.64   57.84 2408.44   57.84
 2499.72   63.53  2529.5   73.84 2956.54   81.84 3012.86   87.84 3156.51   89.84
#Mann= 3 ,-1 , 0
       0     .06       0 1184.76    .035       0 1602.11     .06       0
#XS Ineff= 2 ,-1
       0  263.44 103.031 1834.19 3156.51      74
Permanent Ineff=
       F       F
Bank Sta=1196.72,1365.98
XS Rating Curve= 0 ,0
Exp/Cntr=0.3,0.1

Type RM Length L Ch R = 1 ,61976.  ,394.49,469.55,582.71
XS GIS Cut Line= 5
 6433522.0861832  2047165.499819 6433467.6752821 2047802.2690506
 6433546.0434842 2048115.7419535 6433438.2871768 2048879.8321247
 6433634.2077529 2049594.9421518
#Sta/Elev= 30
       0  103.84  163.81  103.84  176.03   93.84  206.48   83.84  242.93   63.84
  272.31   59.84     642   57.84  671.79   57.84  676.94   56.31  691.39   51.84
  724.66   45.84  735.01   32.76  753.92      34  767.84   32.02  816.39   33.35
     827   36.67  845.58   45.84  852.11   53.84  861.75   56.38  1038.7   57.84
 1079.53   67.84 1087.33   69.84 1152.64   70.99 1549.46   75.84 1991.83   77.84
 2121.84   80.91 2154.65   83.84 2285.05   85.84  2376.5   89.84 2475.32   89.84
#Mann= 3 ,-1 , 0
       0     .06       0     642    .035       0 1079.53     .06       0
#XS Ineff= 1 ,-1
 1341.06 2475.32      70
Permanent Ineff=
       F
Bank Sta=676.94,861.75
XS Rating Curve= 0 ,0
Exp/Cntr=0.3,0.1

Type RM Length L Ch R = 1 ,61506.  ,1271.35,1150.01,496.74
XS GIS Cut Line= 4
 6433067.5283831 2047100.5391948 6433095.4262159 2047586.7564358
 6432968.0778698 2048252.8863189 6433389.3070801 2049692.9024399
#Sta/Elev= 30
       0  101.84  232.54  103.84  260.74   93.84  286.89   77.85  307.54   71.73
  327.62   59.84  641.33   55.84  668.15   50.56  696.26   45.84  706.38      34
  716.51      31  757.94   32.58  782.02    28.7  828.05      36  844.94   45.84
  852.86   53.84  861.01   55.85  877.12   61.84   937.9   61.84 1110.03   55.84
 1318.09   55.84 1375.85   57.67 1417.34   61.84 1467.69   67.84 1500.18   75.84
 2267.45   79.84 2370.73   81.84 2402.03   85.84 2515.67   85.92 2665.57   89.79
#Mann= 3 ,-1 , 0
       0     .06       0  641.33    .035       0   937.9     .06       0
Bank Sta=668.15,861.01
XS Rating Curve= 0 ,0
Exp/Cntr=0.3,0.1

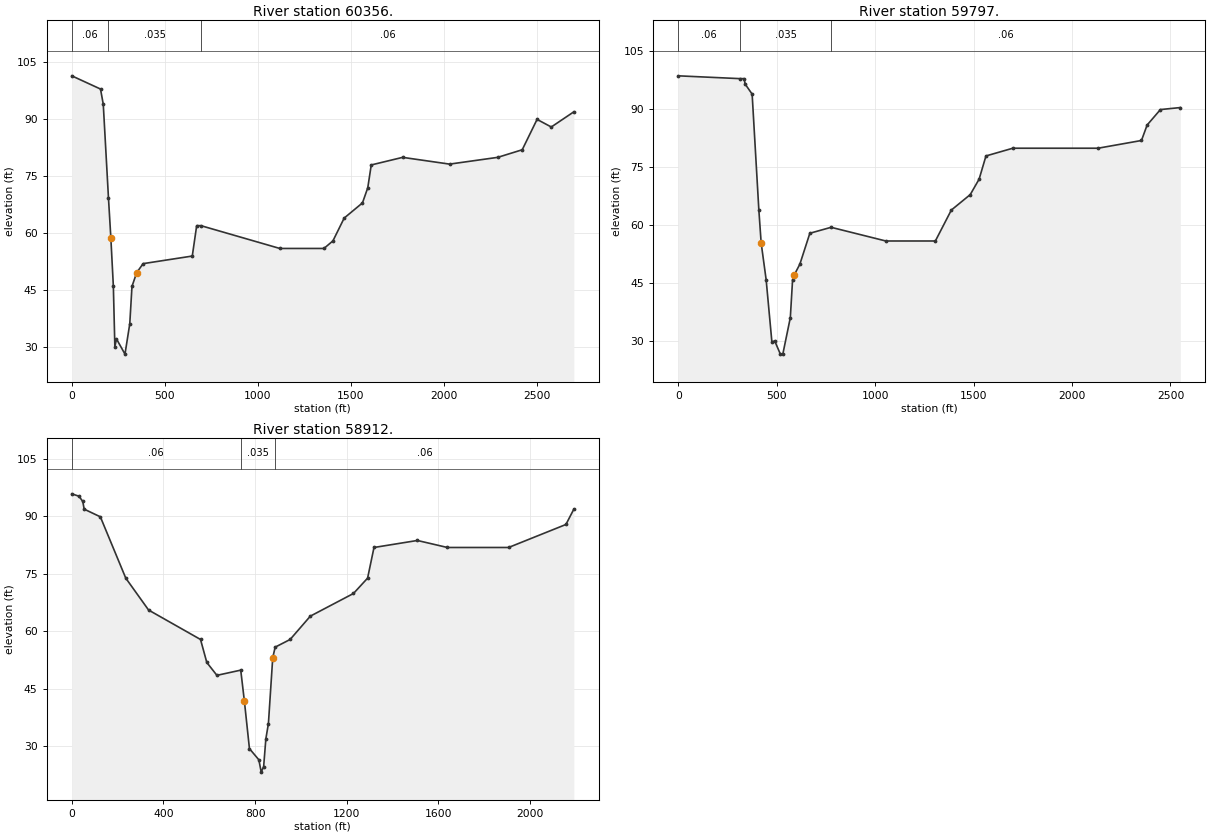
Type RM Length L Ch R = 1 ,60356.  ,617.68,559.05,204.03
XS GIS Cut Line= 4
  6431772.962469 2047527.9802724 6432128.6324184 2047825.5568555
 6432480.6628347 2048324.2666553 6433183.5904846  2049790.862728
#Sta/Elev= 30
       0  101.32  154.56   97.84  169.41   93.84  197.31   69.22  210.11   58.71
  223.72   45.84  231.77      30  240.57      32  286.21      28     312      36
  323.83   45.84  349.44   49.49  383.85   51.84  648.22   53.84  671.83   61.84
  694.88   61.84 1118.95   55.84 1356.37   55.84 1404.76   57.84  1465.2   63.84
 1563.58   67.84 1592.15   71.84 1610.82   77.84 1779.58   79.84 2032.14   78.06
 2291.02   79.84 2422.88   81.84 2502.71   89.84 2579.22   87.84 2700.53   91.84
#Mann= 3 ,-1 , 0
       0     .06       0  197.31    .035       0  694.88     .06       0
Bank Sta=210.11,349.44
XS Rating Curve= 0 ,0
Exp/Cntr=0.3,0.1

Type RM Length L Ch R = 1 ,59797.  ,527.79,884.89,991.41
XS GIS Cut Line= 5
 6431459.4895661 2047998.1896267 6431704.3902389 2048233.2942802
 6432057.0472665 2048233.2942802  6432311.744006 2048419.4187897
 6432977.8738891 2049810.4547666
#Sta/Elev= 30
       0   98.57  314.06   97.84  334.39   97.84  340.01   96.42  375.32   93.84
  409.45   63.84  421.13   55.34  446.43   45.84  475.71   29.67  489.74      30
  517.98   26.66  531.13   26.57  569.25      36  580.74   45.84  589.99   47.14
   617.7   49.84  668.43   57.84  776.35   59.38 1054.44   55.84 1305.89   55.84
 1386.96   63.84 1483.06   67.84  1528.1   71.84 1562.85   77.84  1699.1   79.84
 2131.86   79.84 2352.69   81.84 2381.35   85.84 2448.86   89.84 2549.91   90.36
#Mann= 3 ,-1 , 0
       0     .06       0  314.06    .035       0  776.35     .06       0
Bank Sta=421.13,589.99
XS Rating Curve= 0 ,0
Exp/Cntr=0.3,0.1

Type RM Length L Ch R = 1 ,58912.  ,352.75,487.76,567.47
XS GIS Cut Line= 2
 6431214.5888459 2048252.8863189 6432213.7837179 2050202.2958716
#Sta/Elev= 30
       0   95.84   31.64   95.21   48.03   93.84   54.17   91.84  124.72   89.84
  235.63   73.84  335.17   65.52  561.75   57.84  589.17   51.84  633.27   48.48
  737.23   49.84  753.25   41.69   775.2   29.36  816.18   26.45  826.68   23.23
  837.19   24.69  846.82   31.93  857.97   35.89  876.78   53.06  887.47   55.84
  952.72   57.84 1040.92   63.93 1229.09   69.84 1290.67   73.84 1318.62   81.84
 1507.85   83.67 1638.83   81.84 1905.78   81.84 2155.96   87.84 2190.57   91.84
#Mann= 3 ,-1 , 0
       0     .06       0  737.23    .035       0  887.47     .06       0
Bank Sta=753.25,876.78
XS Rating Curve= 0 ,0
Exp/Cntr=0.3,0.1