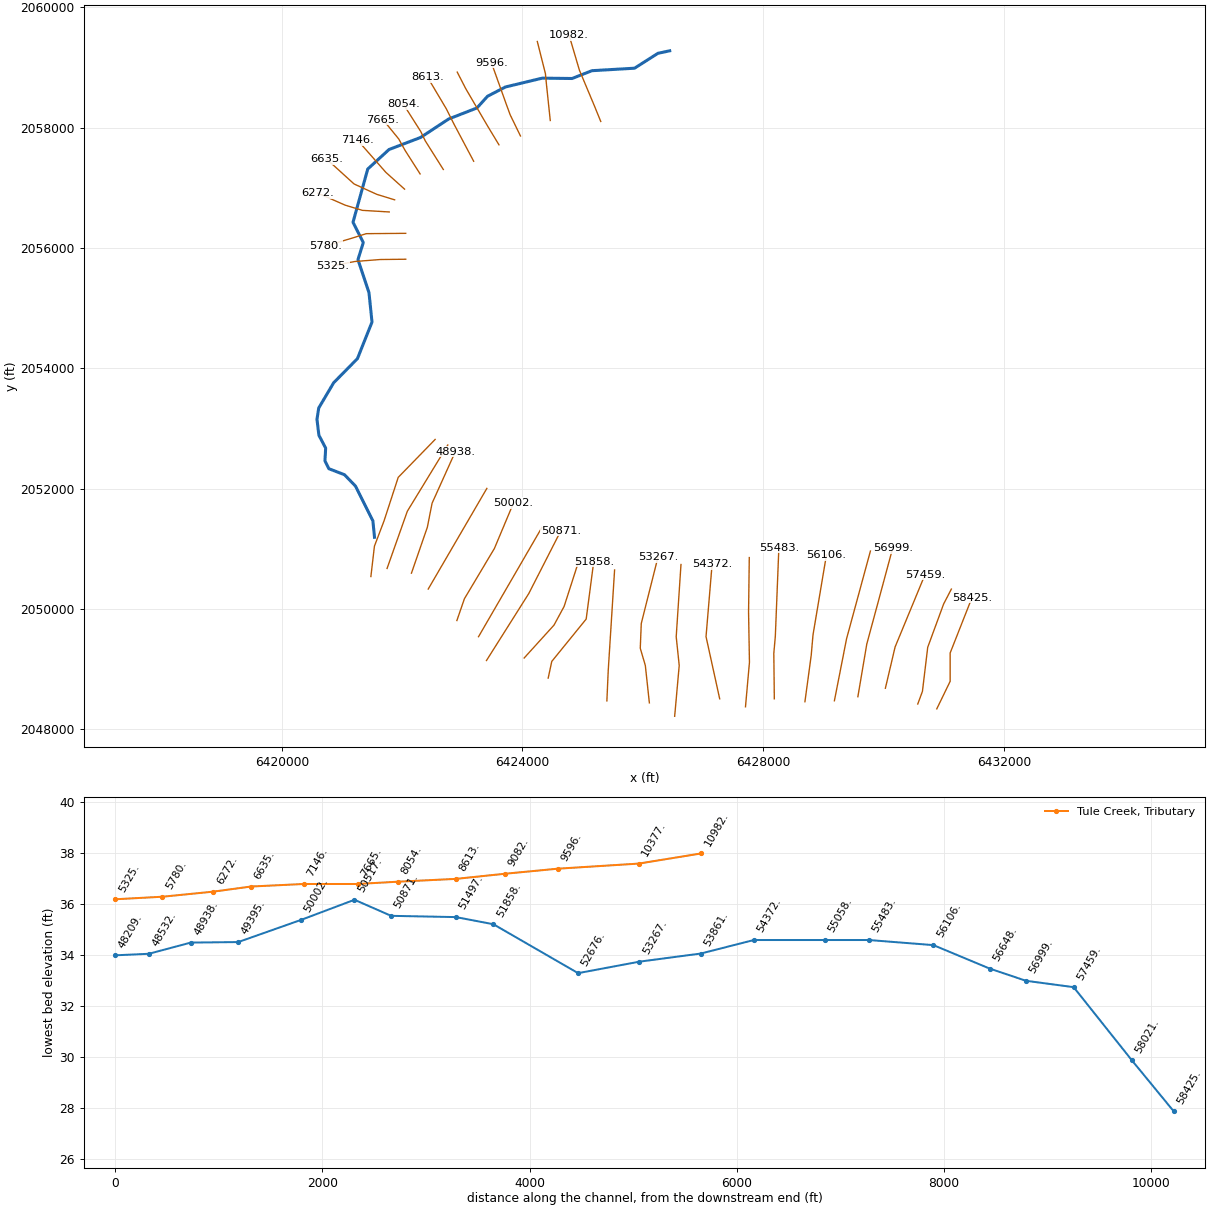
HEC-RAS study Baxter.prj: Baxter River GIS Example

--- Baxter.g02 (geometry) --- (continued)

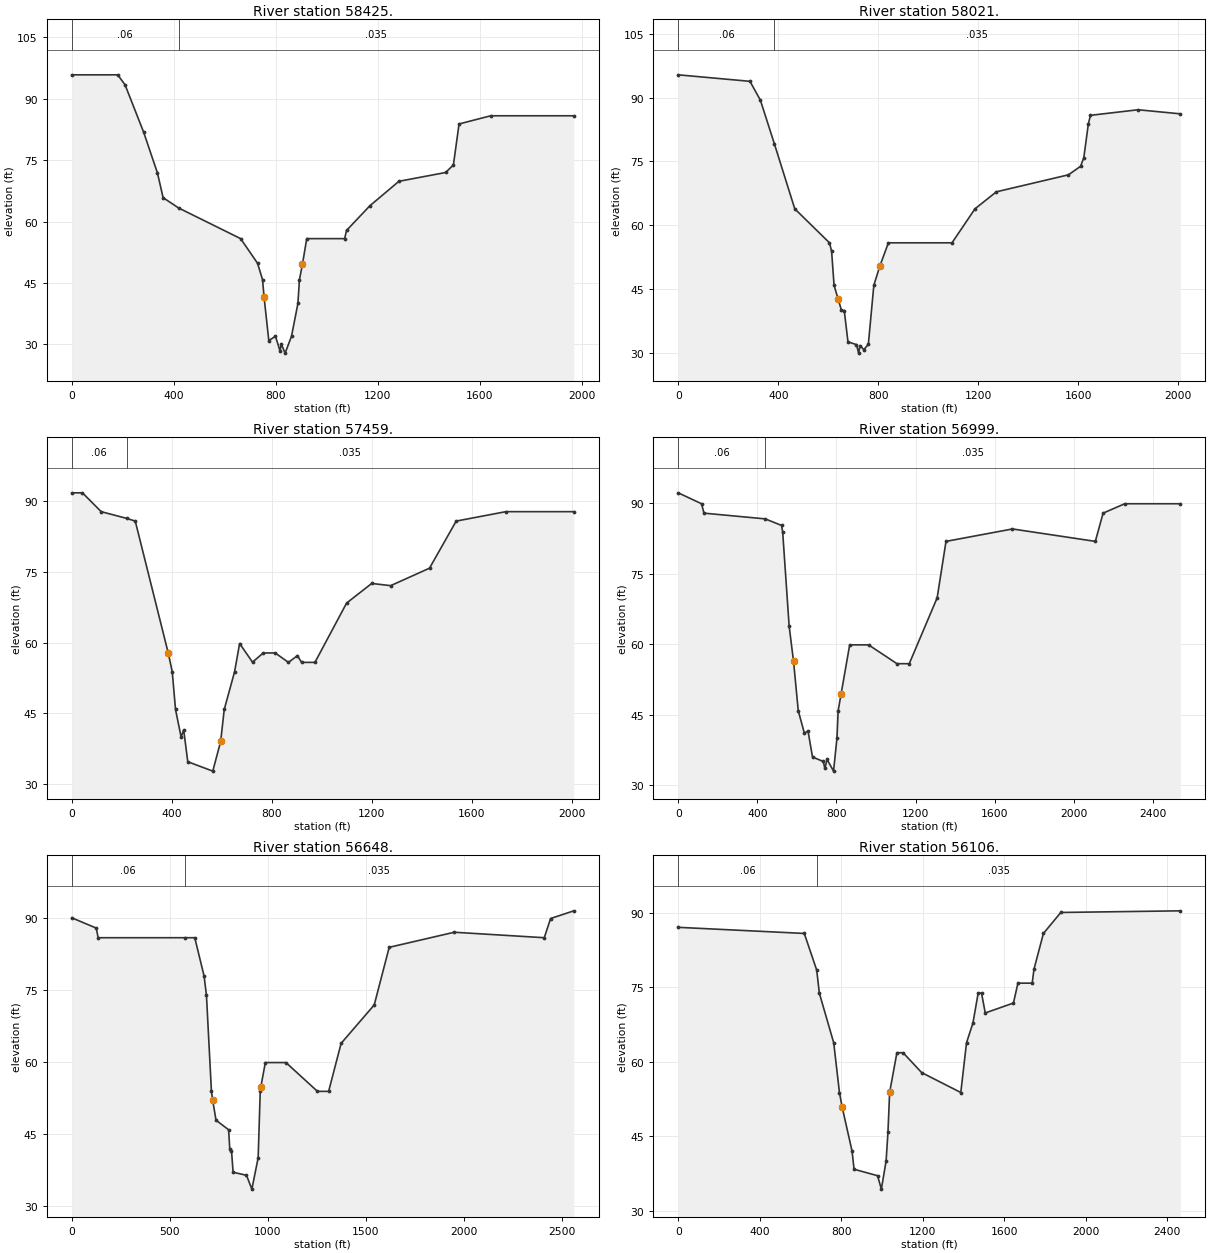
Type RM Length L Ch R = 1 ,58425.  ,441.7,403.69,386.57
XS GIS Cut Line= 4
 6430885.8606241 2048342.2654694 6431107.8318126 2048799.6605337
 6431107.8318126 2049270.5084276 6431471.0573077  2050192.025042
#Sta/Elev= 30
       0   95.84  180.18   95.84  209.07    93.4  281.95   81.84  336.27   71.84
  358.34   65.84  419.35   63.32  662.45   55.84  728.69   49.84  748.38   45.84
  754.36   41.64  772.99   30.95  799.19      32  816.85   28.44  821.98   30.08
  837.09   27.88  862.08      32  887.22      40  893.23   45.84  904.94   49.54
   921.8   55.84 1070.59   55.84 1078.01   57.84 1169.13   63.84 1283.51   69.84
 1466.82   71.99 1497.26   73.84 1519.44   83.84 1643.57   85.84 1969.78   85.84
#Mann= 2 ,-1 , 0
       0     .06       0  419.35    .035       0
Bank Sta=754.36,904.94
XS Rating Curve= 0 ,0
Exp/Cntr=0.3,0.1

Type RM Length L Ch R = 1 ,58021.  ,581.56,561.67,525.46
XS GIS Cut Line= 5
 6430569.7199136 2048422.9822092 6430647.1710139 2048632.2932755
 6430735.1786535 2049365.6900038 6430999.2014303 2050084.4187843
 6431128.0109857 2050333.2794433
#Sta/Elev= 30
       0   95.37  286.88   93.84  328.65   89.38  384.76   79.08  465.98   63.84
  604.81   55.84  613.37   53.84  623.11   45.84  639.46   42.59  652.59      40
  663.92   39.88  678.75   32.54  712.84   31.88  721.37   29.88  726.76   31.64
   742.6   30.68  760.29      32  782.19   45.84  805.81    50.3  840.43   55.84
 1094.79   55.84 1186.69   63.84 1272.21   67.84 1560.37   71.84 1608.86   73.84
 1621.76   75.84 1640.04   83.84 1648.53   85.84 1839.01   87.15 2007.75   86.19
#Mann= 2 ,-1 , 0
       0     .06       0  384.76    .035       0
Bank Sta=639.46,805.81
XS Rating Curve= 0 ,0
Exp/Cntr=0.3,0.1

Type RM Length L Ch R = 1 ,57459.  ,448.27,460.04,476.86
XS GIS Cut Line= 3
 6430031.6080147 2048685.3117913 6430193.0415891 2049371.4044352
 6430690.7950945 2050575.4297576
#Sta/Elev= 30
       0   91.84   42.61   91.84  117.75   87.84  219.53   86.41  253.81   85.84
  385.87    57.8   401.8   53.84  414.88   45.84  437.24      40  447.55    41.5
  463.86   34.75  563.85   32.75  595.38   39.05   609.7   45.84  651.05   53.84
  671.21   59.84  722.72   55.89  765.75   57.84  813.51   57.84  866.43   55.84
  902.41   57.27  918.85   55.84  972.33   55.84  1099.1   68.44 1199.57    72.6
 1275.18   72.13  1430.5   75.84 1537.21   85.84 1735.71   87.84 2007.69   87.84
#Mann= 2 ,-1 , 0
       0     .06       0  219.53    .035       0
Bank Sta=385.87,595.38
XS Rating Curve= 0 ,0
Exp/Cntr=0.3,0.1

Type RM Length L Ch R = 1 ,56999.  ,356.17,351.22,350.04
XS GIS Cut Line= 3
  6429574.212903   2048544.05739 6429722.1936953 2049418.4892199
 6430152.6831955 2051012.6456962
#Sta/Elev= 30
       0   92.16  117.73   89.84  130.22   87.84  440.07   86.62  522.27   85.23
  527.97   83.84  560.63   63.84  582.94   56.32  606.77   45.84   637.4    41.1
  656.14    41.5   678.8      36  733.24   35.05   741.4   33.57  752.17    35.5
  785.16      33  802.36      40  808.48   45.84  822.89   49.31  866.74   59.84
  962.29   59.84 1105.69   55.84 1167.87   55.84 1308.92   69.84 1353.67   81.84
 1689.62   84.48 2108.58   81.84 2147.78   87.84 2257.19   89.84 2538.12   89.84
#Mann= 2 ,-1 , 0
       0     .06       0  440.07    .035       0
Bank Sta=582.94,822.89
XS Rating Curve= 0 ,0
Exp/Cntr=0.3,0.1

Type RM Length L Ch R = 1 ,56648.  ,522.44,542.07,563.75
XS GIS Cut Line= 3
 6429184.0817964 2048476.7934323 6429385.8737644 2049505.9323981
 6429782.7312621 2050965.5609115
#Sta/Elev= 30
       0   89.99   125.1   87.84  134.44   85.84  576.06   85.84  627.48   85.84
  675.12   77.84  687.12   73.84  712.53   53.84  718.93      52  735.79   47.84
  800.15   45.84  806.04   41.87  814.84    41.5  823.13      37  891.33   36.36
  918.78   33.48  950.85      40  961.44   53.84  964.46   54.76  987.51   59.84
 1092.56   59.84 1253.54   53.84 1310.42   53.84 1374.04   63.84 1543.04   71.84
 1619.37   83.84 1951.18   86.98 2410.53   85.84 2442.68   89.84 2561.35   91.44
#Mann= 2 ,-1 , 0
       0     .06       0  576.06    .035       0
Bank Sta=718.93,964.46
XS Rating Curve= 0 ,0
Exp/Cntr=0.3,0.1

Type RM Length L Ch R = 1 ,56106.  ,617.86,622.85,632.88
XS GIS Cut Line= 4
 6428694.3159041 2048460.8182062 6428799.0112454 2049233.6785681
  6428828.347141  2049571.041084  6429051.655807 2050899.1377053
#Sta/Elev= 30
       0   87.07  618.97   85.84  680.03   78.45  692.74   73.84  763.45   63.84
  791.55   53.84  804.58   50.96  853.73      42   863.3    38.4  978.63    37.1
  997.44    34.4 1020.76    40.1 1029.79   45.84 1038.03   53.87 1073.71   61.84
 1104.26   61.84 1195.37   57.84 1387.46   53.84 1415.45   63.84 1447.15   67.84
 1472.72   73.84  1489.3   73.84 1507.49   69.84 1646.03   71.84 1667.86   75.84
 1737.95   75.84 1746.94   78.67 1793.12   85.84 1878.53   90.06 2465.29   90.39
#Mann= 2 ,-1 , 0
       0     .06       0  680.03    .035       0
Bank Sta=804.58,1038.03
XS Rating Curve= 0 ,0
Exp/Cntr=0.3,0.1

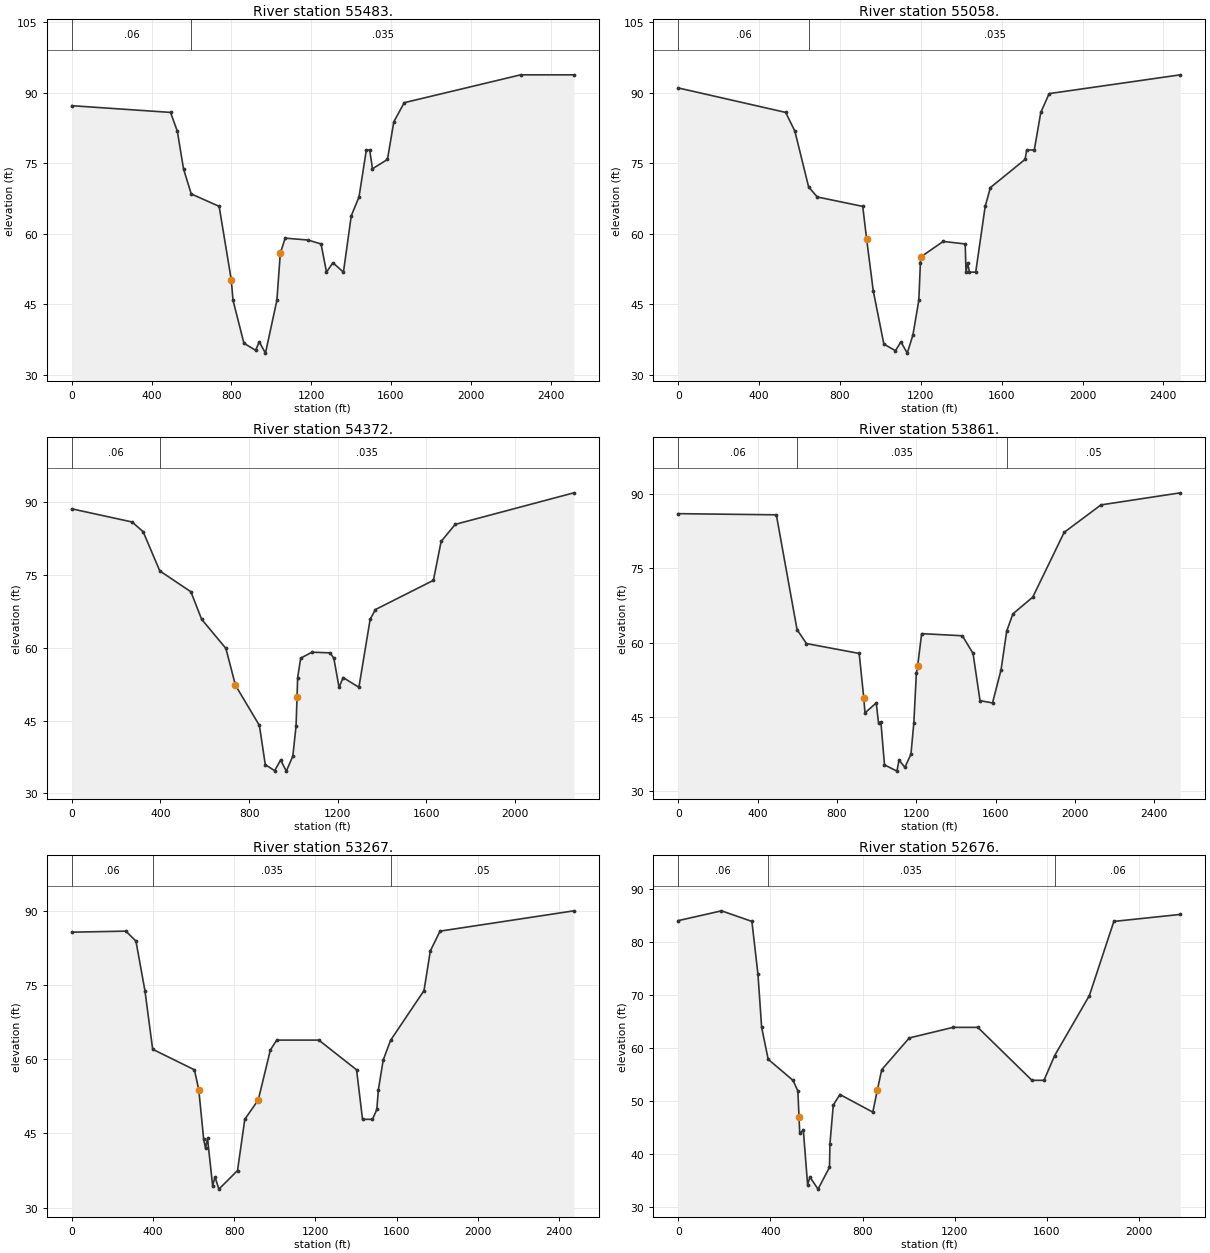
Type RM Length L Ch R = 1 ,55483.  ,407.38,425.15,445.81
XS GIS Cut Line= 4
 6428185.6320133 2048509.1642128 6428177.2240245 2049265.8840574
  6428202.447991 2049551.7560081 6428261.3040073 2051023.1556585
#Sta/Elev= 30
       0   87.27  494.97   85.84  529.07   81.84  560.01   73.84  598.71   68.49
  738.65   65.84  799.25   50.23  808.22   45.84  862.81   36.71  921.46    35.2
  939.41      37  970.78    34.6 1028.01   45.84  1045.2   55.84 1069.46   59.08
  1184.1   58.67 1249.41   57.84 1276.65   51.84 1308.76   53.84 1361.57   51.84
 1400.79   63.84 1439.62   67.84 1476.34   77.84 1493.15   77.84 1507.18   73.84
 1582.19   75.83 1613.99   83.84 1666.29   87.91 2249.73   93.84 2516.33   93.84
#Mann= 2 ,-1 , 0
       0     .06       0  598.71    .035       0
Bank Sta=799.25,1045.2
XS Rating Curve= 0 ,0
Exp/Cntr=0.3,0.1

Type RM Length L Ch R = 1 ,55058.  ,629.67,685.71,707.67
XS GIS Cut Line= 4
 6427706.3761307 2048376.7382235 6427772.2558447 2049116.3351276
 6427757.5878969 2049952.4073959 6427769.4360941 2050857.0977139
#Sta/Elev= 30
       0   91.05  531.51   85.84  577.05   81.84  644.92   69.98  687.67   67.84
  912.63   65.84  931.52      59  964.66   47.86 1017.19   36.52 1074.43   35.12
 1101.38      37 1132.86    34.6 1161.01    38.5 1190.01   45.84 1197.86   53.84
 1201.91   55.13 1310.51   58.38 1419.55   57.84 1423.46   51.84 1431.69   53.84
 1440.35   51.84 1471.48   51.84  1518.3   65.84 1544.11   69.84 1715.57   75.84
 1723.74   77.84 1761.21   77.84 1793.37   85.84 1834.66   89.84 2483.49   93.84
#Mann= 2 ,-1 , 0
       0     .06       0  644.92    .035       0
Bank Sta=931.52,1201.91
XS Rating Curve= 0 ,0
Exp/Cntr=0.3,0.1

Type RM Length L Ch R = 1 ,54372.  ,546.44,511.64,507.83
XS GIS Cut Line= 3
 6427277.5682283 2048509.1642128 6427050.5522465  2049543.347972
 6427151.4482542 2050745.6917439
#Sta/Elev= 30
       0   88.55   272.5   85.84  322.13   83.84  397.18   75.78  537.56   71.49
  585.86   65.84   695.4   59.84  738.57   52.25  846.59      44   873.1   35.94
  915.26   34.69  942.39   36.88  968.06    34.6   997.4   37.68 1011.91   43.84
 1016.43   49.84 1019.17   53.84  1032.9   57.84 1084.48   59.07 1165.01   58.92
  1182.3   57.84 1205.99   51.84 1224.45   53.84 1295.57   51.84 1346.32   65.84
 1370.43   67.84 1631.64   73.84 1666.55   81.84  1730.1   85.35 2265.38   91.84
#Mann= 2 ,-1 , 0
       0     .06       0  397.18    .035       0
Bank Sta=738.57,1016.43
XS Rating Curve= 0 ,0
Exp/Cntr=0.3,0.1

Type RM Length L Ch R = 1 ,53861.  ,555.89,594.15,591.83
XS GIS Cut Line= 4
 6426529.2563725 2048219.0882677 6426604.9283665 2049064.0920894
 6426554.8172644 2049541.7052357 6426634.3563273 2050741.4877495
#Sta/Elev= 30
       0   86.07  494.54   85.84  598.96   62.65  646.41   59.84  912.15   57.84
  935.49    48.8  941.42   45.84  998.17   47.84 1009.56   43.84 1021.54      44
 1039.78   35.34 1102.46   34.07 1113.04   36.31 1142.53   34.83 1173.21    37.5
 1187.73   43.84 1200.46   53.84 1207.03   55.36 1227.04   61.84 1432.39   61.41
 1486.23   57.84 1521.25   48.31 1584.26   47.84 1627.34   54.52  1655.9   62.36
 1687.22   65.84 1787.13   69.21 1945.54    82.3 2131.05   87.84 2531.04   90.28
#Mann= 3 ,-1 , 0
       0     .06       0  598.96    .035       0  1655.9     .05       0
Bank Sta=935.49,1207.03
XS Rating Curve= 0 ,0
Exp/Cntr=0.3,0.1

Type RM Length L Ch R = 1 ,53267.  ,630.25,590.58,504.24
XS GIS Cut Line= 5
 6426108.8564589 2048441.9002077 6426041.5924538 2049064.0920894
 6425957.5124711 2049349.9640401  6425974.328496 2049761.9559649
 6426251.7924106 2050863.4037292
#Sta/Elev= 30
       0   85.63  266.22   85.84  315.92   83.84  360.16   73.84  398.28   61.99
  603.91   57.84   625.4   53.79  649.39   43.84  658.46   42.04   668.3      44
  693.56   34.43  705.05    36.2  724.41   33.75  816.07    37.5  851.85   47.84
  918.12   51.75  977.78   61.84 1009.03   63.84 1216.47   63.84 1402.24   57.84
 1431.57   47.84 1480.59   47.84 1501.93   49.84 1509.62   53.84 1533.58   59.84
 1569.86   63.81 1734.25   73.84 1765.38   81.84 1813.22   85.84 2471.99   89.94
#Mann= 3 ,-1 , 0
       0     .06       0  398.28    .035       0 1569.86     .05       0
Bank Sta=625.4,918.12
XS Rating Curve= 0 ,0
Exp/Cntr=0.3,0.1

Type RM Length L Ch R = 1 ,52676.  ,918.25,817.87,500.81
XS GIS Cut Line= 3
 6425402.5845945 2048475.5322103 6425425.3863237 2048984.3236919
 6425530.8065895 2050651.1017515
#Sta/Elev= 30
       0   83.99  187.78   85.84  319.81   83.84  346.12   73.84  362.02   63.84
  390.52   57.81  498.09   53.84  519.21   51.84  524.33    46.9  527.37   43.84
  543.08    44.4  561.64    34.1  571.55    35.6  606.83    33.3  656.56   37.42
  658.55   41.84     673   49.19  701.91   51.16  844.56   47.84  864.57   52.06
  883.15   55.84  1002.8   61.84 1192.92   63.84 1300.31   63.84 1535.47   53.84
 1587.59   53.84 1633.95   58.51 1784.64   69.84  1890.9   83.84 2179.41   85.16
#Mann= 3 ,-1 , 0
       0     .06       0  390.52    .035       0 1633.95     .06       0
Bank Sta=524.33,864.57
XS Rating Curve= 0 ,0
Exp/Cntr=0.3,0.1

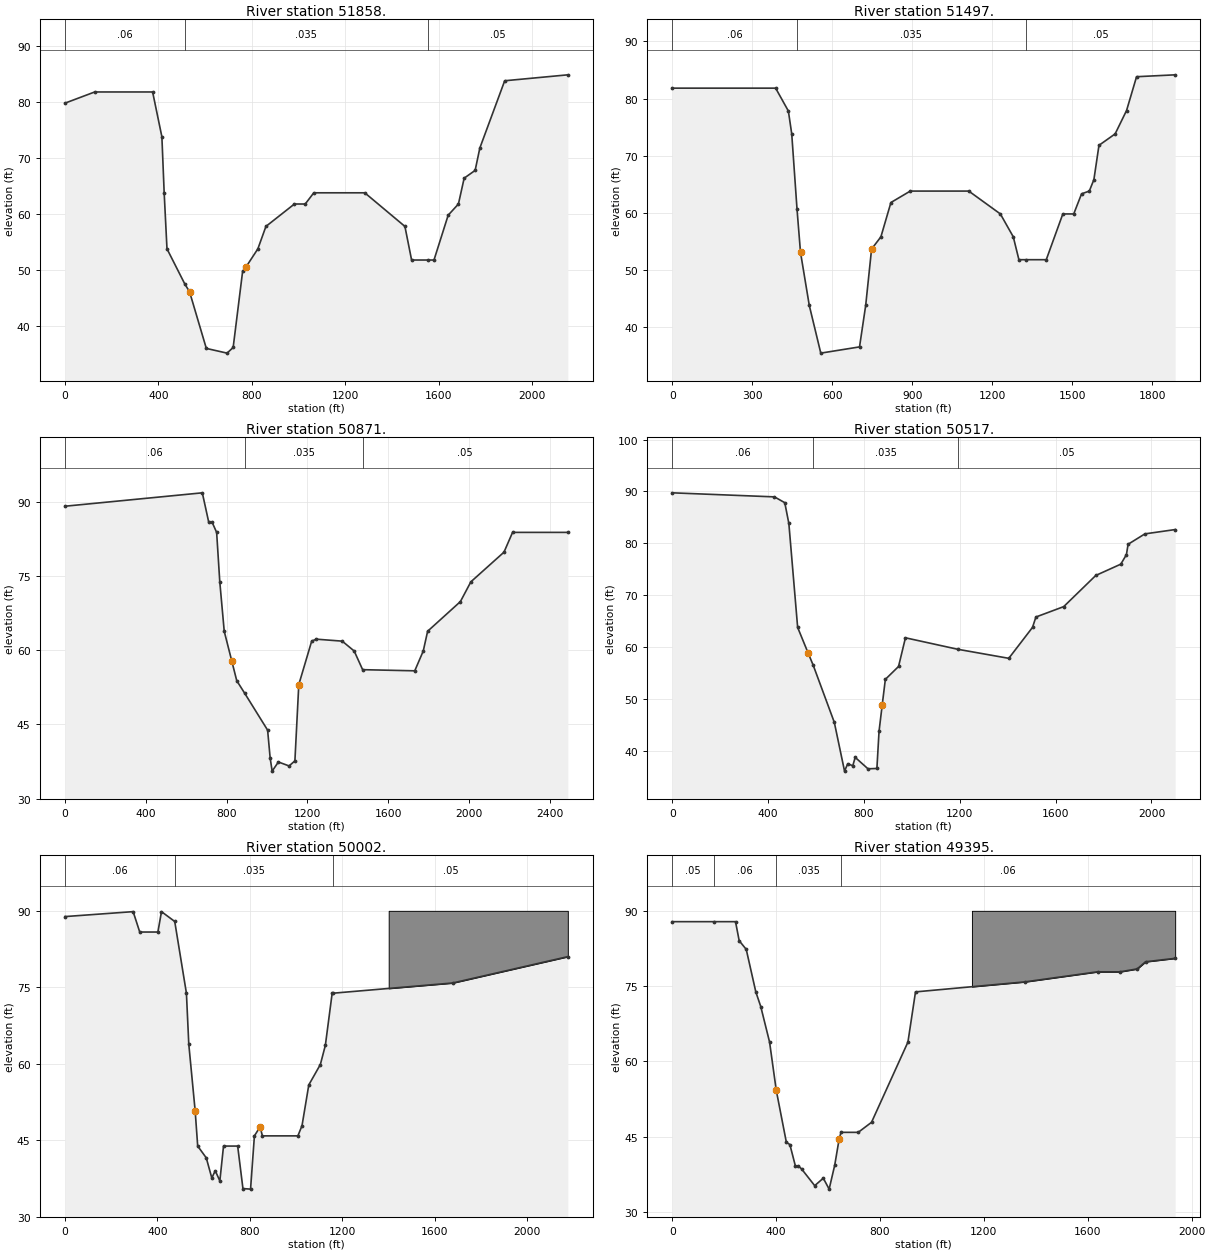
Type RM Length L Ch R = 1 ,51858.  ,369.66,361.37,403.21
XS GIS Cut Line= 4
 6424427.2568044 2048853.8921325 6424486.6384679 2049131.0030281
 6425058.6879595  2049835.063908 6425183.9766489 2050787.7317353
#Sta/Elev= 30
       0   79.84  127.37   81.84  375.14   81.84  414.78   73.84  424.56   63.84
  436.58   53.84  513.59    47.5  532.96    46.2  604.89   36.06  693.67   35.22
  719.72   36.23  760.25   49.84  773.84   50.55  825.44   53.84  859.88   57.84
  981.73   61.84 1028.01   61.84 1064.67   63.84 1282.73   63.84 1454.51   57.84
 1483.07   51.84 1551.55   51.84 1578.89   51.84 1639.56   59.84 1683.44   61.84
 1707.94   66.45 1754.94   67.84 1775.07   71.84 1881.39   83.84 2151.43    84.9
#Mann= 3 ,-1 , 0
       0     .06       0  513.59    .035       0 1551.55     .05       0
Bank Sta=532.96,773.84
XS Rating Curve= 0 ,0
Exp/Cntr=0.3,0.1

Type RM Length L Ch R = 1 ,51497.  ,586.49,625.8,619.09
XS GIS Cut Line= 4
 6424027.8769101 2049188.1100899 6424523.9487703 2049734.6299303
 6424692.1087357 2050045.7258948 6424935.9406951 2050802.4457394
#Sta/Elev= 30
       0   81.84   387.8   81.84  435.52   77.84  448.15   73.84  468.06   60.62
  481.04   53.12  513.99   43.84  557.14    35.5  702.51   36.59  725.62   43.84
  747.71    53.7   782.7   55.84   820.3   61.84  892.88   63.84 1112.35   63.84
 1230.93   59.84 1279.34   55.84 1300.47   51.84 1325.72   51.84 1403.11   51.84
 1465.25   59.84 1506.13   59.84 1535.59   63.36  1564.6   63.84  1581.8   65.84
 1600.86   71.84 1661.48   73.84 1704.37   77.93 1741.88   83.84 1886.76   84.17
#Mann= 3 ,-1 , 0
       0     .06       0  468.06    .035       0 1325.72     .05       0
Bank Sta=481.04,747.71
XS Rating Curve= 0 ,0
Exp/Cntr=0.3,0.1

Type RM Length L Ch R = 1 ,50871.  ,342.18,353.62,362.71
XS GIS Cut Line= 3
 6423401.2113233 2049145.6709759 6424105.2722033 2050260.4340161
 6424637.4567612 2051302.7216413
#Sta/Elev= 30
       0   89.13  679.88   91.84  711.97   85.84  728.91   85.84   750.8   83.84
  766.35   73.84  788.33   63.84  826.02   57.77   850.3   53.84  889.19   51.33
 1003.08   43.84 1015.56   38.24  1025.5   35.55 1056.43    37.4 1109.24    36.6
 1138.11   37.62 1157.38   53.06 1221.15   61.84 1243.95   62.24 1372.38   61.84
  1431.6   59.84 1473.29   56.07 1731.29   55.84 1773.29   59.84 1794.96   63.84
 1957.12   69.84 2008.97   73.84  2172.9   79.84 2215.36   83.84 2488.78   83.84
#Mann= 3 ,-1 , 0
       0     .06       0  889.19    .035       0 1473.29     .05       0
Bank Sta=826.02,1157.38
XS Rating Curve= 0 ,0
Exp/Cntr=0.3,0.1

Type RM Length L Ch R = 1 ,50517.  ,524,515.69,513.12
XS GIS Cut Line= 2
 6423269.1999349 2049541.7052357 6424322.1568496 2051357.3736159
#Sta/Elev= 30
       0   89.74  426.42   88.96  469.49   87.84  486.52   83.84   523.2   63.84
  567.18   58.88  588.22   56.55  676.23   45.57  718.95   36.18  732.39   37.61
  753.34   37.21  763.38   38.83  816.71   36.63  853.97   36.69  862.92   43.84
  876.18   48.92  889.26   53.84  944.34   56.32   973.1   61.84 1191.62   59.63
  1404.4   57.89 1503.43   63.84 1517.71   65.84 1633.72   67.84 1767.57   73.84
 1871.89   76.01 1895.45   77.84 1902.41   79.84 1972.55   81.84  2098.9   82.67
#Mann= 3 ,-1 , 0
       0     .06       0  588.22    .035       0 1191.62     .05       0
Bank Sta=567.18,876.18
XS Rating Curve= 0 ,0
Exp/Cntr=0.3,0.1

Type RM Length L Ch R = 1 ,50002.  ,605.1,606.38,615.94
XS GIS Cut Line= 4
 6422909.6131209 2049810.3019242 6423034.5129591 2050172.4264239
  6423533.222759 2051008.4986923 6423850.0686556 2051763.2566727
#Sta/Elev= 30
       0   88.87  294.99   89.84  323.55   85.84  402.13   85.84  417.61   89.84
   474.9   87.91  525.46   73.84  535.68   63.84  563.29   50.74  574.23   43.84
  611.27   41.53  635.24   37.58  650.17      39  670.08      37  685.94   43.84
  747.11   43.84  769.94    35.5   802.9   35.39  819.51   45.84  844.21   47.62
  854.04   45.84 1007.63   45.84 1025.45   47.84 1054.79   55.84 1104.77   59.84
  1126.4    63.6 1155.89   73.84 1160.79   73.84 1677.44   75.84 2175.14   81.01
#Mann= 3 ,-1 , 0
       0     .06       0   474.9    .035       0 1160.79     .05       0
#Block Obstruct= 1 ,-1
 1400.33 2175.14      90
Bank Sta=563.29,844.21
XS Rating Curve= 0 ,0
Exp/Cntr=0.3,0.1

Type RM Length L Ch R = 1 ,49395.  ,422.01,457.34,543.03
XS GIS Cut Line= 2
 6422433.1276665 2050333.7737079  6423407.787002 2052006.8914848
#Sta/Elev= 30
       0   87.84  159.55   87.84  243.45   87.84  257.58   84.04  284.72   82.32
   321.6   73.84  340.62   70.92  374.56   63.84  400.29   54.23   439.3   43.84
  452.73   43.41  474.15    39.1  484.98   39.17  498.04   38.53  548.37   35.21
  581.44    36.7  603.93   34.52  625.45    39.3  642.76   44.59  649.78   45.84
  715.99   45.84  767.15   47.84  907.36   63.84  936.47   73.84 1358.85   75.84
 1637.32   77.84 1724.07   77.84 1790.05   78.42 1822.24   79.84 1936.31   80.53
#Mann= 4 ,-1 , 0
       0     .05       0  159.55     .06       0  400.29    .035       0
  649.78     .06       0
#Block Obstruct= 1 ,-1
 1153.71 1936.31      90
Bank Sta=400.29,642.76
XS Rating Curve= 0 ,0
Exp/Cntr=0.3,0.1

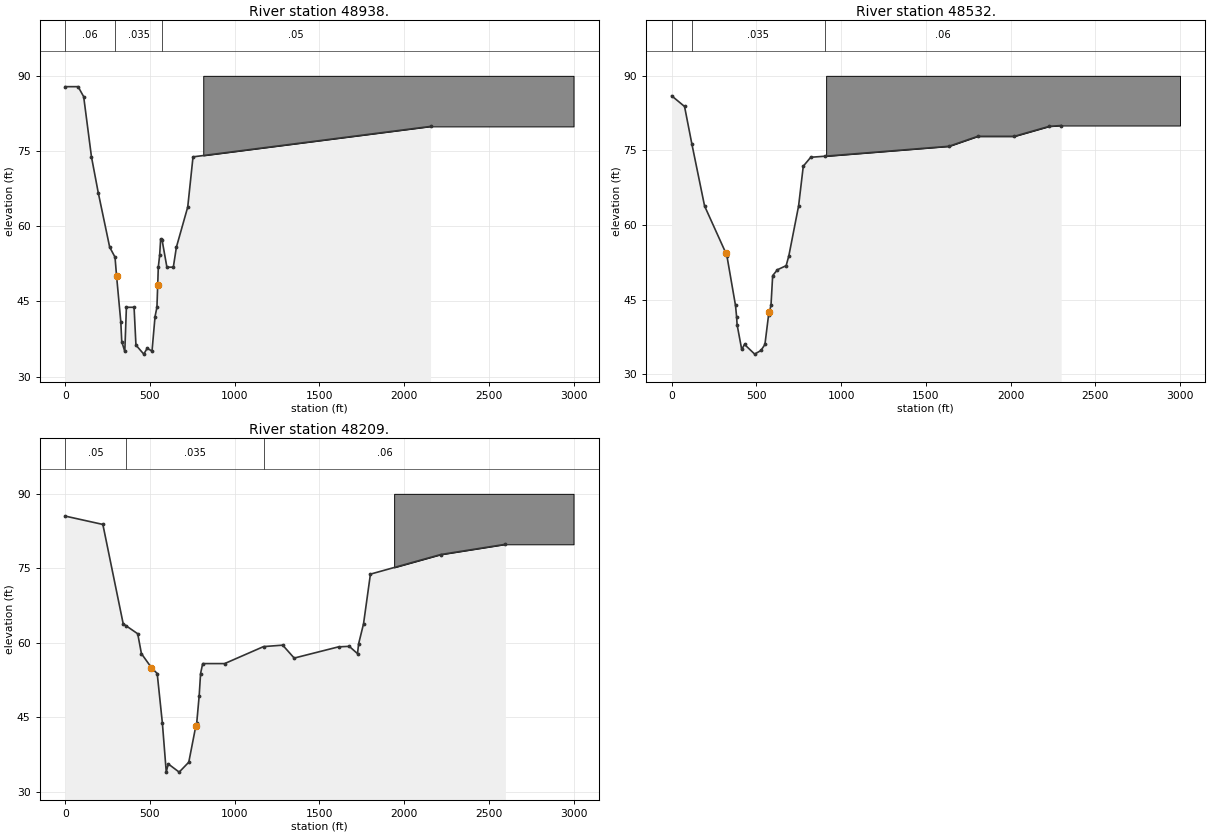
Type RM Length L Ch R = 1 ,48938.  ,408.28,405.47,400.31
XS GIS Cut Line= 4
 6422154.4368946  2050597.796532 6422418.4597187 2051360.5291086
  6422497.621196 2051760.9575046 6422884.3891544 2052618.5733568
#Sta/Elev= 30
       0   87.84   76.05   87.84  108.99   85.84  154.99   73.84  194.81   66.73
  262.43   55.84  293.91   53.84  303.35      50  327.99      41  333.77      37
  351.76   35.03  361.13   43.84  406.41   43.84  417.47    36.3  463.71    34.5
  483.82   35.67  512.31    35.1  530.22      42  541.35   43.84  545.91   48.23
  549.39   51.84  557.32    54.2  563.34   57.49  571.63   57.27  600.19   51.84
   638.1   51.84  656.29   55.84  723.12   63.84   754.3   73.84 2156.11   79.91
#Mann= 3 ,-1 , 0
       0     .06       0  293.91    .035       0  571.63     .05       0
#Block Obstruct= 1 ,-1
  814.71    3000      90
Bank Sta=303.35,545.91
XS Rating Curve= 0 ,0
Exp/Cntr=0.3,0.1

Type RM Length L Ch R = 1 ,48532.  ,306.78,323.87,317.24
XS GIS Cut Line= 3
 6421749.3093876 2050676.3257653 6422085.6293185 2051626.4295417
 6422758.2691804 2052727.8773059
#Sta/Elev= 30
       0   85.98   75.95   83.84  119.31   76.28  194.15   63.84  319.64   54.38
  325.88   53.84  376.73   43.84  383.32   41.51  386.02      40  413.31      35
  429.92   36.01  489.98   34.06  526.88    34.8  550.34      36  572.09   41.99
  576.06   42.52  586.08   43.84  596.03   49.84  624.12   51.02   675.6   51.84
  691.58   53.84  749.02   63.84  776.72   71.84  820.81   73.63   904.6   73.84
 1636.71   75.84 1806.29   77.84 2022.38   77.84 2227.77   79.84 2298.47   80.01
#Mann= 3 ,-1 , 0
       0     .05       0  119.31    .035       0   904.6     .06       0
#Block Obstruct= 1 ,-1
  911.63    3000      90
Bank Sta=319.64,576.06
XS Rating Curve= 0 ,0
Exp/Cntr=0.3,0.1

Type RM Length L Ch R = 1 ,48209.  ,395.02,514.47,823.64
XS GIS Cut Line= 5
 6421480.2534145 2050541.7978024 6421539.1094308 2051046.2776514
 6421698.8614075  2051466.677565 6421934.2853307 2052189.7654544
 6422548.0692235 2052820.3652775
#Sta/Elev= 30
       0   85.52  222.22   83.84  342.28   63.84  360.51   63.42  427.99   61.84
   449.8   57.84  509.02   55.02  542.94   53.84  573.56   43.84  596.37      34
  607.89   35.66  672.58      34   729.3      36  770.69   43.25  776.06   43.84
  790.77   49.41  798.89   53.84  811.41   55.84  940.83   55.84 1170.63   59.26
 1283.61   59.55 1351.42   56.95 1613.09   59.21 1676.57   59.31 1725.03   57.84
 1731.82   59.84 1760.62   63.84  1801.3   73.84 2215.91   77.78 2598.07   79.84
#Mann= 3 ,-1 , 0
       0     .05       0  360.51    .035       0 1170.63     .06       0
#Block Obstruct= 1 ,-1
 1941.34    3000      90
Bank Sta=509.02,770.69
XS Rating Curve= 0 ,0
Exp/Cntr=0.3,0.1

River Reach=Tule Creek      ,Tributary
Reach XY= 30
 6426446.7600056 2059279.8400007 6426252.0299814 2059238.5299987
 6425862.5599927 2058990.6900088  6425154.430021 2058949.3800068
 6424823.9699798 2058819.5600064 6424328.2800126 2058825.4599882
 6423714.5700085 2058677.9300076 6423419.5199875 2058524.4999978
 6423242.4800158  2058329.770021 6422773.3499778 2058146.8300201
 6422307.1600142 2057839.9799882  6421781.969996 2057639.3399946
 6421427.9099803 2057314.7799825 6421183.0100174 2056429.6199793
 6421354.1400199 2056093.2600036 6421265.6300215 2055810.0099935
 6421448.5599875 2055261.2100133 6421498.7199859 2054771.4199805
 6421256.7699903 2054163.6100056 6420861.4000199  2053762.340006
 6420613.5599827 2053343.3700138 6420584.0499916 2053154.5299838
 6420616.5099972 2052888.9800137 6420728.6300049 2052676.5499968
  6420716.829994 2052464.1099923 6420781.7400179 2052334.2800044
 6421041.3900062 2052233.9699952 6421224.3200195 2052045.1300125
 6421513.4700114 2051466.8299814 6421540.4499851 2051194.1899983

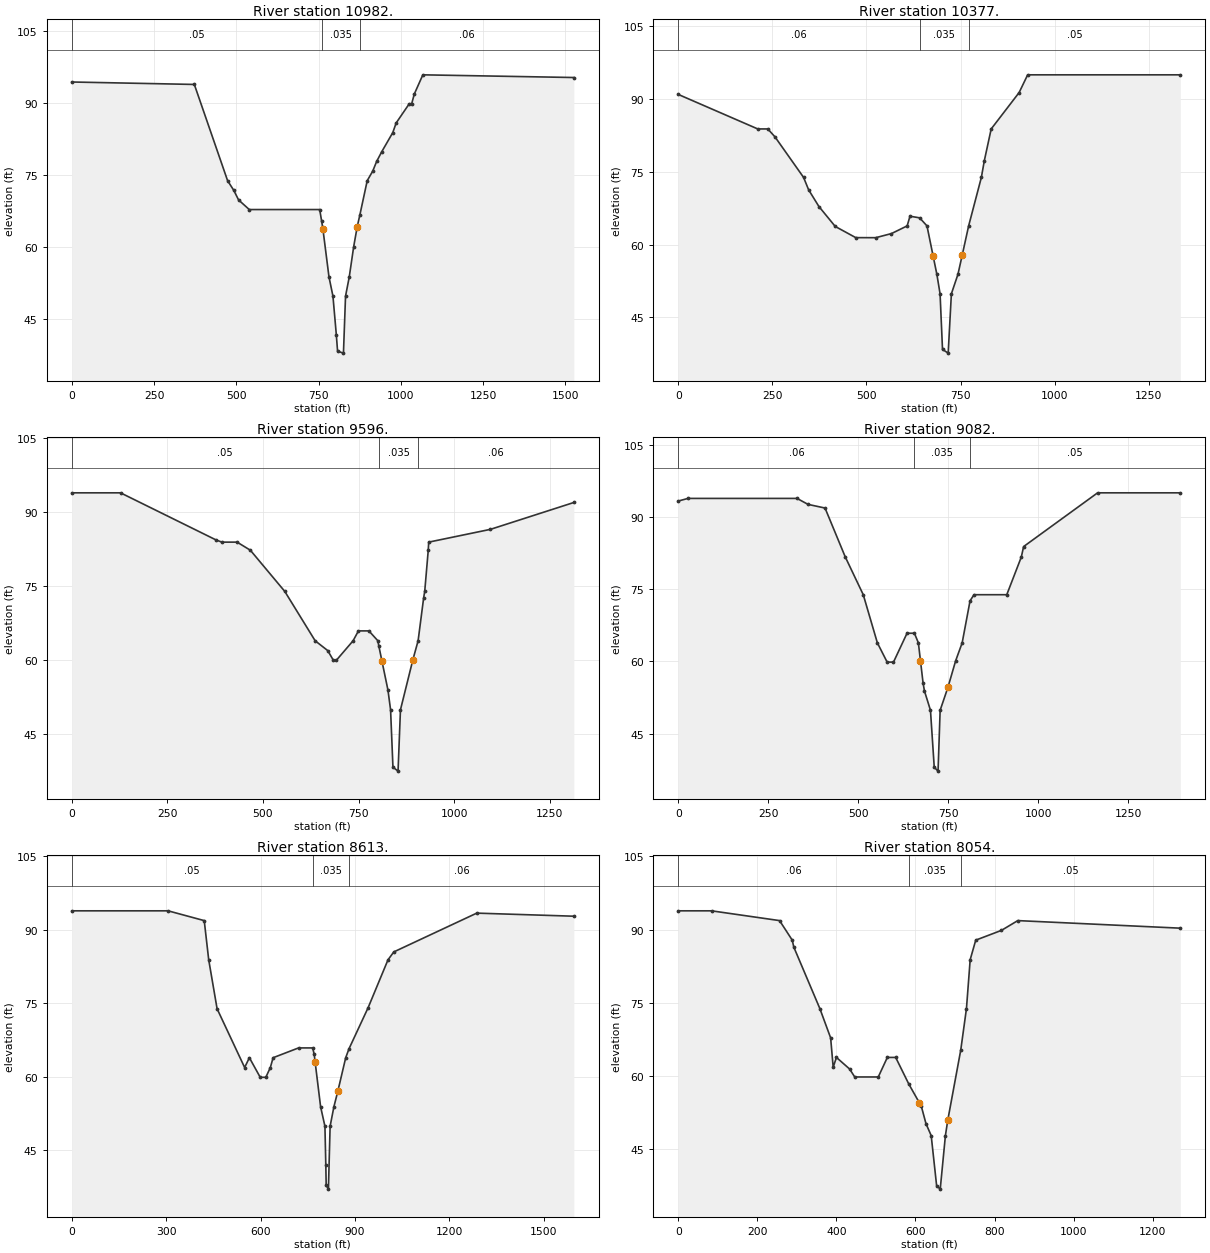
Type RM Length L Ch R = 1 ,10982.  ,636.51,604.91,581.58
XS GIS Cut Line= 4
 6425301.0159667 2058105.2966476 6425193.3936153   2058368.97147
  6424945.250402 2058960.2052628  6424775.600164 2059535.5812185
#Sta/Elev= 30
       0   94.35  372.47   93.84  473.56   73.84  492.26   71.84  506.95   69.84
  539.42   67.84  753.42   67.84  759.13   65.54  763.15   63.84  781.68   53.84
  793.75   49.84  803.99   41.82   807.8    38.4  825.67      38  832.01   49.84
  843.33   53.84   856.7    60.1  867.53   64.29  875.58   66.73  897.89   73.84
  914.71   75.84  926.57   77.84  941.89   79.84  975.64   83.84  985.88   85.84
 1025.79   89.84 1033.07   89.84 1040.95   91.84 1066.96   95.84 1525.85   95.28
#Mann= 3 ,-1 , 0
       0     .05       0  759.13    .035       0  875.58     .06       0
Bank Sta=763.15,867.53
XS Rating Curve= 0 ,0
Exp/Cntr=0.3,0.1

Type RM Length L Ch R = 1 ,10377.  ,742.36,780.89,792.31
XS GIS Cut Line= 4
 6424461.5614271  2058121.440005 6424396.9879973 2058734.8875878
 6424380.8446399 2058901.7022655  6424246.316677 2059434.4330138
#Sta/Elev= 30
       0   90.96  211.25   83.84  237.92   83.84  257.05    82.2  333.03   73.84
  346.43   71.28  373.74   67.84  417.12   63.73  471.65   61.42  524.71   61.41
  566.53   62.26  608.16   63.84  615.71   65.84  641.38    65.5  660.86   63.84
  677.15   57.63  687.15   53.84  695.62   49.84   702.1   38.37  717.18    37.6
  725.67   49.84  743.08   53.84  754.73   57.91  771.51   63.84  805.33   73.84
  813.15   77.27  831.45   83.84   905.7   91.35  928.31      95 1333.88      95
#Mann= 3 ,-1 , 0
       0     .06       0  641.38    .035       0  771.51     .05       0
Bank Sta=677.15,754.73
XS Rating Curve= 0 ,0
Exp/Cntr=0.3,0.1

Type RM Length L Ch R = 1 ,9596.   ,483.01,513.72,529.78
XS GIS Cut Line= 4
 6423966.3303657 2057864.4915736  6423794.302716 2058218.3001497
 6423735.1103896 2058379.7337241 6423482.8704414 2059083.6513232
#Sta/Elev= 30
       0   93.84  127.52   93.84  377.21   84.29  392.57   83.84  432.43   83.84
  467.07    82.2  557.18   73.84  636.52   63.84  669.52   61.84  684.47   59.84
  691.54   59.84  735.79   63.84   749.7   65.84  777.08   65.84  800.53   63.84
  802.99    62.8  811.25   59.71  826.92   53.84  833.79   49.84     840    38.2
  853.34    37.4  859.65   49.84  892.03   59.96   905.8   63.84  920.38   72.59
  923.09   73.84  932.34   82.22  933.52   83.84  1094.8   86.43  1313.1   91.88
#Mann= 3 ,-1 , 0
       0     .05       0  802.99    .035       0   905.8     .06       0
Bank Sta=811.25,892.03
XS Rating Curve= 0 ,0
Exp/Cntr=0.3,0.1

Type RM Length L Ch R = 1 ,9082.   ,471.53,468.89,465.86
XS GIS Cut Line= 4
 6423608.9904155 2057717.3516275 6423419.9516762    2058029.6771
 6423055.4148794 2058653.2268603 6422915.3305816 2058926.0013674
#Sta/Elev= 30
       0   93.29   27.07   93.84  329.83   93.84  360.36    92.6  407.58   91.84
  463.55   81.72  513.71   73.84  552.89   63.84  580.03   59.84  597.67   59.84
  635.25   65.84  655.76   65.84  666.74   63.84  672.61   60.09  679.85   55.47
  683.64   53.84  700.31   49.84  710.79      38  721.36    37.2  727.19   49.84
  748.84   54.61   770.3   60.13  788.34   63.84  810.21   72.57  821.22   73.84
  912.16   73.84  952.53   81.66  958.98   83.84 1164.36      95 1394.01      95
#Mann= 3 ,-1 , 0
       0     .06       0  655.76    .035       0  810.21     .05       0
Bank Sta=672.61,748.84
XS Rating Curve= 0 ,0
Exp/Cntr=0.3,0.1

Type RM Length L Ch R = 1 ,8613.   ,552.42,559.35,555.17
XS GIS Cut Line= 4
 6423188.5905018   2057444.09166  6422852.606881 2058078.3910834
 6422734.2222756 2058315.1602943  6422421.360695 2058841.9213847
#Sta/Elev= 30
       0   93.84  306.03   93.84  420.86   91.84  435.08   83.84   461.7   73.84
  549.23   61.84  564.32   63.84  598.72   59.84  616.56   59.84  630.94   61.84
  639.68   63.84  720.57   65.84  765.34   65.84   770.3   64.52  773.25   62.93
  790.54   53.84  804.33   49.84  807.11   41.96  808.32    37.8  815.39      37
   820.8   49.84   832.9   53.84  845.19   56.96  870.34   63.84  880.96   65.69
  941.66   74.07 1004.73   83.84 1023.23   85.45 1286.68   93.37 1595.17   92.74
#Mann= 3 ,-1 , 0
       0     .05       0  765.34    .035       0  880.96     .06       0
Bank Sta=773.25,845.19
XS Rating Curve= 0 ,0
Exp/Cntr=0.3,0.1

Type RM Length L Ch R = 1 ,8054.   ,372.38,388.69,382.15
XS GIS Cut Line= 4
 6422684.1106055 2057307.4617236 6422384.4495626 2057782.4295461
 6422309.1138787 2057938.4819698 6422021.9807533 2058389.9914893
#Sta/Elev= 30
       0   93.84   84.27   93.84   256.3   91.84  288.39   87.84  292.29   86.42
  358.19   73.84  385.49   67.84  391.92   61.84  400.15   63.84   433.5   61.47
  446.45   59.84  505.98   59.84   528.9   63.84  550.03   63.84  583.23   58.39
  610.18   54.52  614.92   53.84  626.61    50.3  639.86   47.84  653.55   37.61
   662.7   36.89  675.78   47.84  681.74   50.98  714.61   65.35  729.04   73.84
  738.44   83.84   752.5   87.84  817.55   89.84  858.88   91.84 1269.96   90.29
#Mann= 3 ,-1 , 0
       0     .06       0  583.23    .035       0  714.61     .05       0
Bank Sta=610.18,681.74
XS Rating Curve= 0 ,0
Exp/Cntr=0.3,0.1

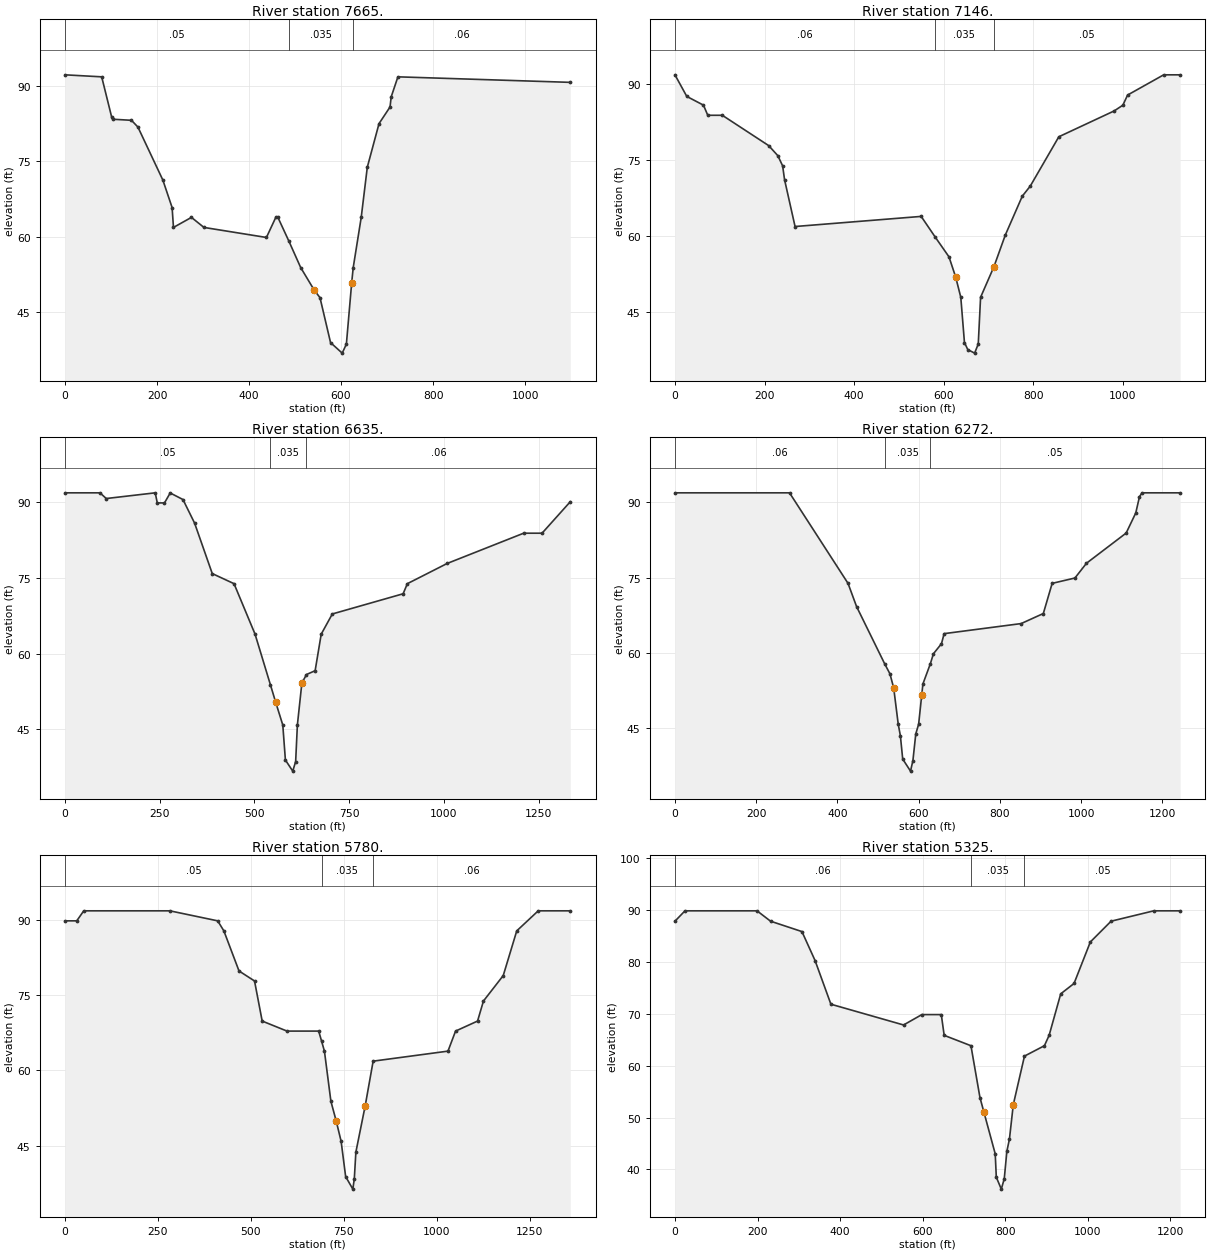
Type RM Length L Ch R = 1 ,7665.   ,483.42,518.81,532.63
XS GIS Cut Line= 4
  6422298.351672 2057233.5553931  6422050.820207 2057620.9959717
 6421943.1978083  2057814.716261 6421679.5229859 2058137.5833625
#Sta/Elev= 30
       0   92.24   79.65   91.84  101.28   83.84  104.48   83.39  144.38   83.18
  158.37   81.84  212.64   71.27  232.72    65.8  235.69   61.84  274.77   63.84
  301.93   61.84  437.77   59.84  458.09   63.84  462.73   63.84  486.23   59.18
  512.28   53.84  541.22   49.42  554.23   47.84  577.15    38.9  602.47    36.8
  611.58    38.6  623.14   50.85  626.44   53.84  643.83   63.84  657.06   73.84
  682.52   82.52   706.5   85.84  708.96   87.84  723.58   91.84 1098.23   90.74
#Mann= 3 ,-1 , 0
       0     .05       0  486.23    .035       0  626.44     .06       0
Bank Sta=541.22,623.14
XS Rating Curve= 0 ,0
Exp/Cntr=0.3,0.1

Type RM Length L Ch R = 1 ,7146.   ,455.16,511.54,541.53
XS GIS Cut Line= 3
 6422040.0579529 2056980.6428247 6421728.8845969 2057259.9288252
 6421259.7957397 2057793.1917528
#Sta/Elev= 30
       0   91.84   26.43   87.57    63.7   85.84   73.29   83.84  105.77   83.84
  209.38   77.84  229.86   75.84  240.48   73.84  244.79    71.1  268.25   61.84
  549.94   63.84  580.59   59.84  612.05   55.84  626.96   51.85  638.42   47.84
  646.58    38.9  654.01    37.5  669.29    36.8  677.42    38.6  682.61   47.84
  712.48   53.91  737.77   60.14  775.75   67.84  793.62   69.84  857.38   79.59
  980.94    84.7 1000.45   85.84 1010.93   87.84 1091.54   91.84 1128.35   91.84
#Mann= 3 ,-1 , 0
       0     .06       0  580.59    .035       0  712.48     .05       0
Bank Sta=626.96,712.48
XS Rating Curve= 0 ,0
Exp/Cntr=0.3,0.1

Type RM Length L Ch R = 1 ,6635.   ,348.69,362.82,378.39
XS GIS Cut Line= 4
 6421874.8408072 2056802.9818272 6421577.2817378 2056894.5449342
 6421200.6034133 2057066.7407153 6420750.2710501  2057475.621689
#Sta/Elev= 30
       0   91.84   92.22   91.84  108.77   90.71  238.06   91.84  243.51   89.84
   262.5   89.84  277.61   91.81  311.33   90.51  341.99   85.84  388.64   75.84
  446.11   73.84  501.62   63.84  542.06   53.84  555.99   50.37  574.84   45.84
  581.73    38.9  601.16    36.7  608.81    38.6  613.36   45.84  625.22   54.15
  637.39   55.84  660.24    56.6   676.3   63.84   705.6   67.84  892.54   71.84
  903.74   73.84 1008.66   77.84  1210.7   83.84 1259.33   83.84 1333.76   90.07
#Mann= 3 ,-1 , 0
       0     .05       0  542.06    .035       0  637.39     .06       0
Bank Sta=555.99,625.22
XS Rating Curve= 0 ,0
Exp/Cntr=0.3,0.1

Type RM Length L Ch R = 1 ,6272.   ,424.48,491.73,562.7
XS GIS Cut Line= 4
 6421785.2956081 2056601.2739249 6421338.6627505 2056628.1795364
 6421053.4634199  2056714.277427 6420597.4136432 2056915.0604174
#Sta/Elev= 30
       0   91.84  282.04   91.84  426.04   73.84  447.11   69.22  516.28   57.84
   529.3   55.84  538.51   53.02  549.62   45.84  554.92   43.54  560.66    38.9
  579.88    36.5   585.8    38.6  592.83    43.9  599.89   45.84  607.37   51.54
  610.41   53.84  628.67   57.84  636.29   59.84  656.12   61.84  662.61   63.84
  852.21   65.84  906.82   67.84  928.57   73.84  984.62    74.9 1013.08   77.84
 1110.71   83.84 1134.39   87.84 1143.53   91.07 1149.79   91.84 1243.65   91.84
#Mann= 3 ,-1 , 0
       0     .06       0  516.28    .035       0  628.67     .05       0
Bank Sta=538.51,607.37
XS Rating Curve= 0 ,0
Exp/Cntr=0.3,0.1

Type RM Length L Ch R = 1 ,5780.   ,445.59,455.6,394.01
XS GIS Cut Line= 4
 6422059.7326846 2056246.1201085 6421403.2361802 2056240.7389578
 6421182.6102794 2056170.7844247 6420730.5963184 2056036.2564618
#Sta/Elev= 30
       0   89.84   31.47   89.84   50.35   91.84  282.07   91.84  410.79   89.84
  427.39   87.84  468.16   79.84  509.92   77.84  530.53   69.84  597.29   67.84
  682.58   67.84  690.35   65.84  698.03   63.84  715.42   53.84  729.83   49.86
  742.97   45.84  755.13    38.8  774.53    36.3  778.48    38.4  782.68    43.7
  807.72   52.92  829.14   61.84 1030.52   63.84 1050.95   67.84 1110.13   69.84
 1125.99   73.84 1179.24   78.92 1215.62   87.84 1273.36   91.84 1359.58   91.84
#Mann= 3 ,-1 , 0
       0     .05       0  690.35    .035       0  829.14     .06       0
Bank Sta=729.83,807.72
XS Rating Curve= 0 ,0
Exp/Cntr=0.3,0.1

Type RM Length L Ch R = 1 ,5325.   ,360.91,397.41,407.35
XS GIS Cut Line= 4
 6422059.7326846 2055815.6306083 6421636.7911093 2055810.9909965
 6421214.8969943 2055777.9627427 6420843.5998205 2055708.0082096
#Sta/Elev= 30
       0   87.84   24.29   89.84  198.86   89.84  231.66   87.84  307.65   85.84
  339.44   80.26  377.82   71.84  553.86   67.84  598.21   69.84  645.27   69.84
  652.27   65.84  717.13   63.84  738.97   53.84   748.5   51.05  775.94      43
  778.55    38.5  790.67    36.2  797.84    38.2  804.14    43.5  810.36   45.84
  819.71   52.48  846.79   61.84  895.11   63.84  906.51   65.84  934.64   73.84
  966.88   75.84 1006.41   83.84 1056.62   87.84    1160   89.84 1223.98   89.84
#Mann= 3 ,-1 , 0
       0     .06       0  717.13    .035       0  846.79     .05       0
Bank Sta=748.5,819.71
XS Rating Curve= 0 ,0
Exp/Cntr=0.3,0.1