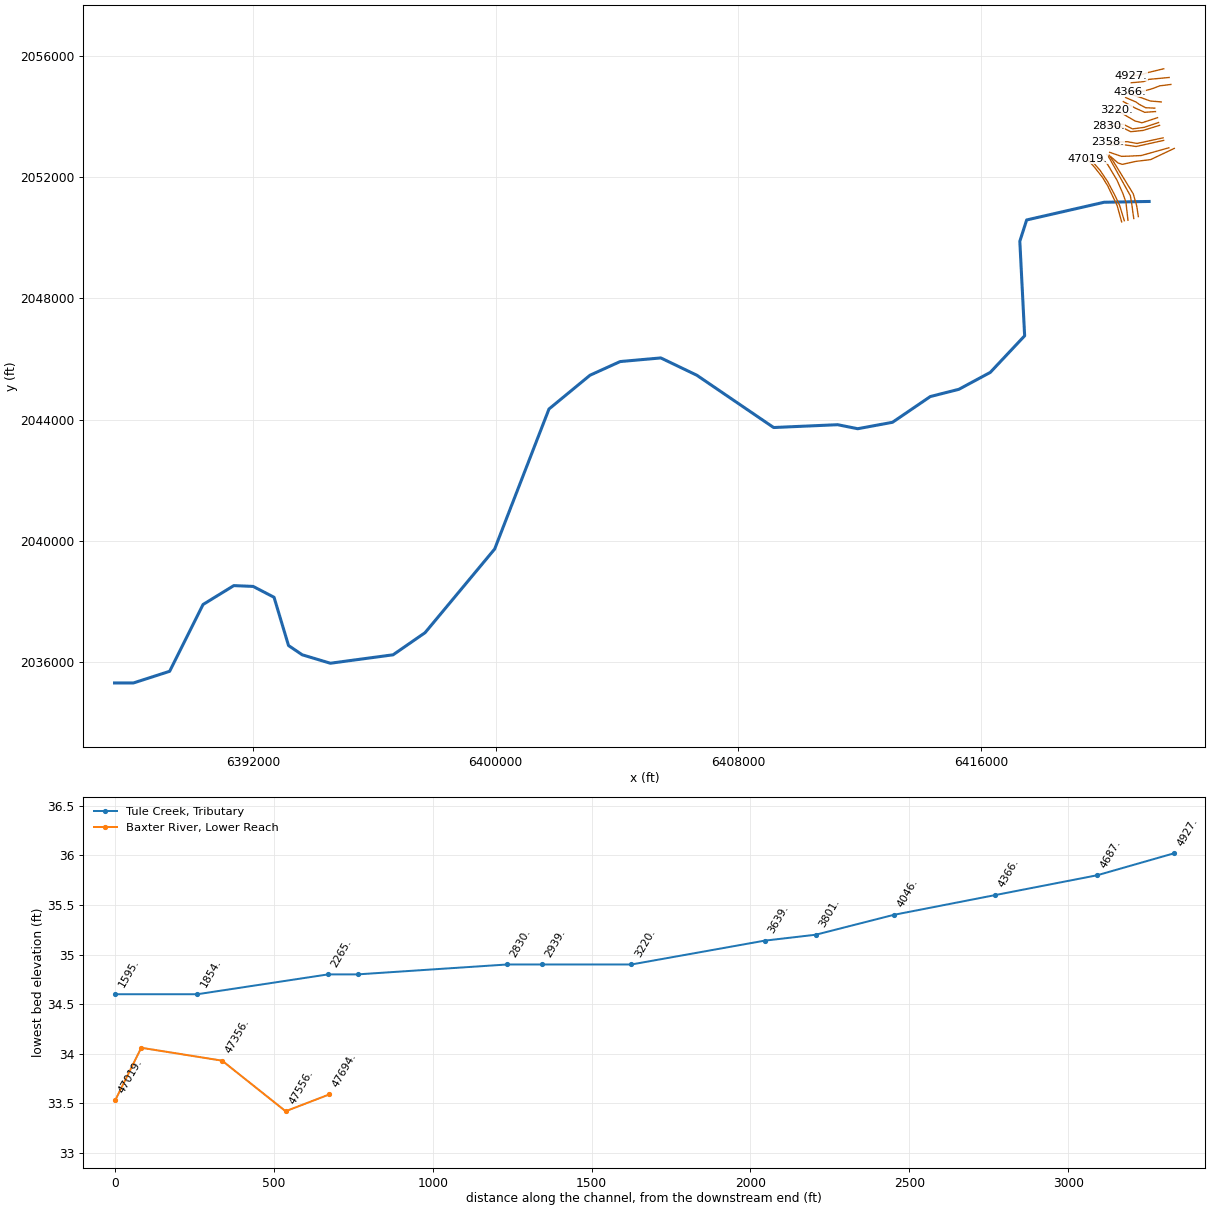
HEC-RAS study Baxter.prj: Baxter River GIS Example

--- Baxter.g02 (geometry) --- (continued)

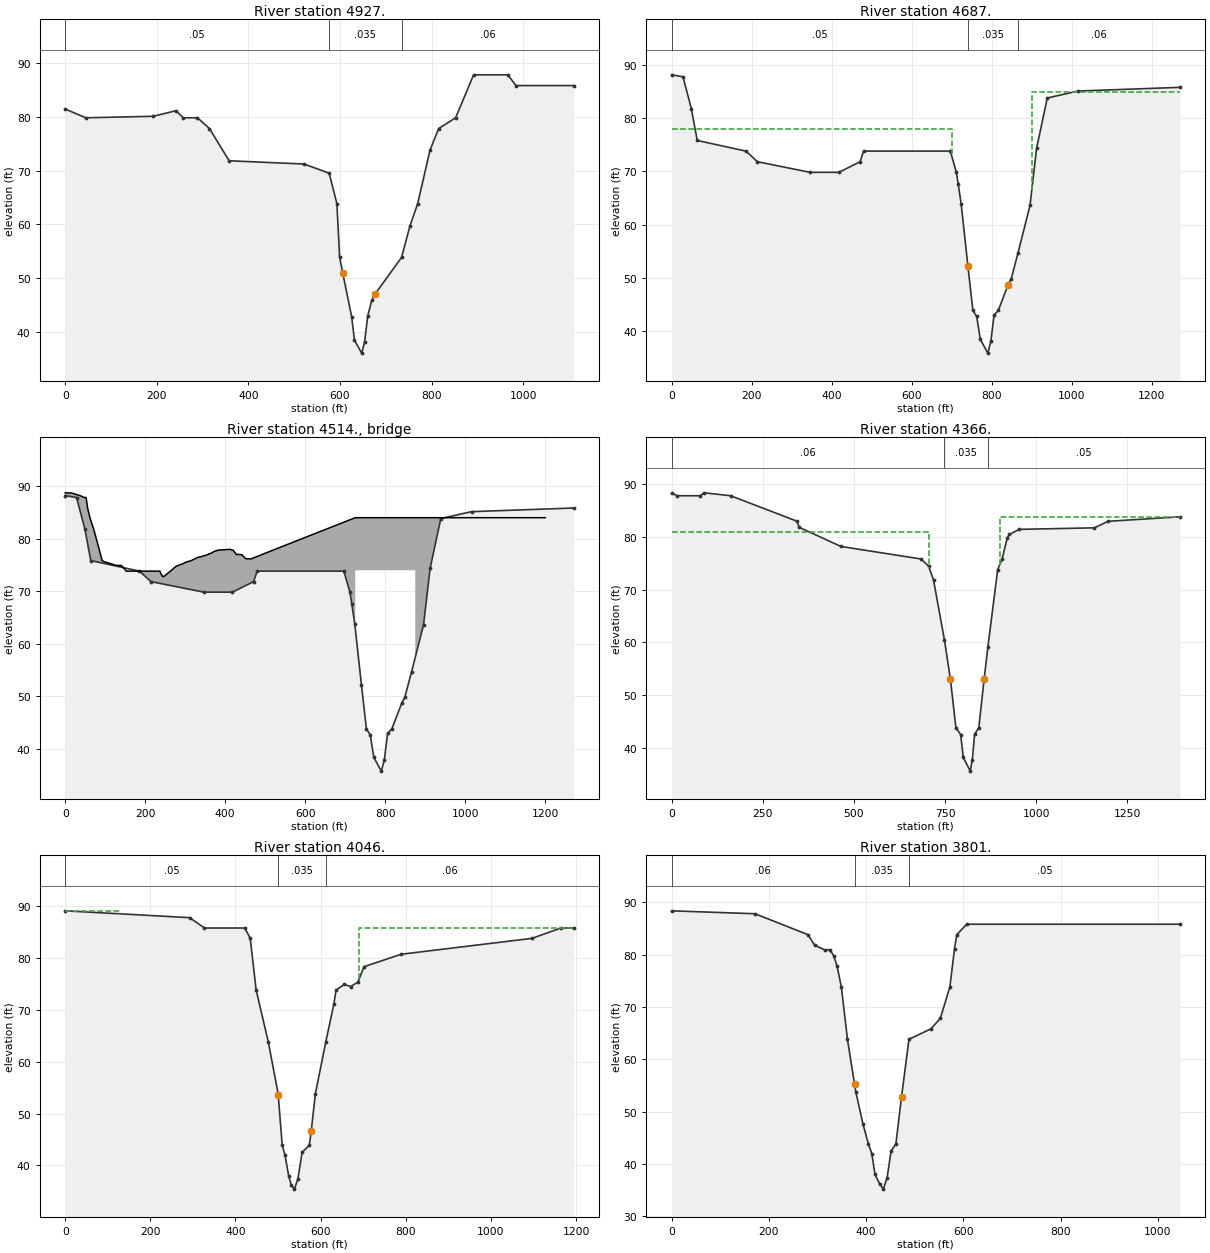
Type RM Length L Ch R = 1 ,4927.   ,232.92,240.23,246.74
XS GIS Cut Line= 4
  6422022.064819  2055568.099096 6421518.9302103 2055447.0239625
 6421231.0403517 2055358.2354966 6420940.4599651 2055336.7109884
#Sta/Elev= 30
       0   81.47      45   79.84  192.14   80.12  241.93   81.16  257.56   79.84
   288.7   79.84  315.02   77.84  358.01   71.84  521.59   71.23  576.47   69.52
  593.36   63.84   599.3   53.84  605.98   50.99   625.7   42.73   631.7   38.41
  647.57   36.02  653.69   38.01  660.77      43  669.53   45.84  676.98   47.05
  734.55   53.84  753.13   59.77  769.72   63.84   796.8   73.84  815.56   77.84
  852.67   79.84  891.89   87.84  966.67   87.84  984.41   85.84 1110.14   85.84
#Mann= 3 ,-1 , 0
       0     .05       0  576.47    .035       0  734.55     .06       0
Bank Sta=605.98,676.98
XS Rating Curve= 0 ,0
Exp/Cntr=0.3,0.1

Type RM Length L Ch R = 1 ,4687.   ,327.57,321.23,302.9
XS GIS Cut Line= 4
 6422200.8209899   2055280.37131 6421532.3830398  2055218.326383
 6421353.3866947 2055142.5356273 6420950.0896518 2055106.8004206
#Sta/Elev= 30
       0    88.2   28.26   87.84   49.14   81.84   63.88   75.84   185.6   73.84
  214.33   71.84  346.22   69.84  418.14   69.84  470.88   71.84  479.78   73.84
  696.38   73.84  711.58   69.84   716.1   67.68  723.69   63.84  740.47   52.18
  752.87   43.84  762.43    42.7   771.4    38.4  790.17    35.8   797.8      38
  805.88      43  816.49   43.84  840.93   48.68  848.88   49.84  865.69   54.67
   895.7   63.63  912.08   74.35  938.84   83.84 1015.76   85.15 1270.57   85.84
#Mann= 3 ,-1 , 0
       0     .05       0  740.47    .035       0  865.69     .06       0
#XS Ineff= 2 ,-1
       0     700      78     900 1270.57      85
Permanent Ineff=
       F       F
Bank Sta=740.47,840.93
XS Rating Curve= 0 ,0
Exp/Cntr=0.3,0.1

Type RM Length L Ch R = 3 ,4514.   ,,,
Node Name=Yosemite Street
Bridge Culvert--1,0,-1,-1, 0
Deck Dist Width WeirC Skew NumUp NumDn MinLoCord MaxHiCord MaxSubmerge Is_Ogee
100,96,2.6,0, 68, 68, , , 0.95, 0, 0,0,,
       0   15.84   38.96   47.45   52.19   54.37   55.98   58.77   62.42   68.02
   71.18    82.9   92.33    96.7  118.56  127.25  140.33  150.82  152.09  155.23
   180.5  189.97  207.31  219.58  236.79  238.37  243.91   247.2  256.83  260.81
  263.15  276.94  287.04  294.83  299.52  308.71  309.17  315.37  319.48  320.32
  329.13  331.76  340.19  345.44  352.11  359.42  363.77  373.26  374.58  382.66
  382.75  383.33  398.14  412.47  416.47  419.25  427.98  432.98  441.15  451.21
  460.76  466.12     525     725     725     875     875    1200
   88.73    88.7   88.15   87.84   87.84   86.75   85.84   84.96   83.84   82.55
   81.84   78.56   75.84   75.65   75.14   74.93   74.91   74.03   73.84   73.84
   73.84   73.84   73.84   73.84   73.84   73.47   72.79   72.86   73.45    73.7
   73.84   74.76   75.05   75.26   75.48   75.69   75.71   75.84   76.01   76.04
   76.39   76.47   76.58   76.75   76.85   77.12    77.2   77.62   77.64   77.83
   77.83   77.84   77.91   77.99   77.84   77.84   76.99   77.02   76.96    76.2
   76.17   76.21      78      84      84      84      84      84
                                                                                
                                                                                
                                                                                
                                                                                
                                                                                
                                                                                
                                      74      74
       0   15.84   38.96   47.45   52.19   54.37   55.98   58.77   62.42   68.02
   71.18    82.9   92.33    96.7  118.56  127.25  140.33  150.82  152.09  155.23
   180.5  189.97  207.31  219.58  236.79  238.37  243.91   247.2  256.83  260.81
  263.15  276.94  287.04  294.83  299.52  308.71  309.17  315.37  319.48  320.32
  329.13  331.76  340.19  345.44  352.11  359.42  363.77  373.26  374.58  382.66
  382.75  383.33  398.14  412.47  416.47  419.25  427.98  432.98  441.15  451.21
  460.76  466.12     525     725     725     875     875    1200
   88.73    88.7   88.15   87.84   87.84   86.75   85.84   84.96   83.84   82.55
   81.84   78.56   75.84   75.65   75.14   74.93   74.91   74.03   73.84   73.84
   73.84   73.84   73.84   73.84   73.84   73.47   72.79   72.86   73.45    73.7
   73.84   74.76   75.05   75.26   75.48   75.69   75.71   75.84   76.01   76.04
   76.39   76.47   76.58   76.75   76.85   77.12    77.2   77.62   77.64   77.83
   77.83   77.84   77.91   77.99   77.84   77.84   76.99   77.02   76.96    76.2
   76.17   76.21      78      84      84      84      84      84
                                                                                
                                                                                
                                                                                
                                                                                
                                                                                
                                                                                
                                      74      74
BR Coef=-1 , 0 , 0 ,, 0 ,,,0.8,0,,0,
WSPro=,,,, 1 ,,,, 0 ,,,, 0 ,,,,-1 ,-1 ,-1 , 0 , 0 , 0 , 0 , 0
BC Design=,, 0 ,, 0 ,,,,,,
BC HTab HWMax=95
BC HTab MaxFlow=10000
BC Use User HTab Curves=0
BC User HTab FreeFlow(D)= 0

Type RM Length L Ch R = 1 ,4366.   ,356.48,320.19,265.47
XS GIS Cut Line= 5
  6422256.976254 2055050.6451565 6421889.4144178 2055004.6998974
 6421634.1631098  2054907.704424 6421332.9665901 2054826.0240055
 6420893.9343877 2054815.8139531
#Sta/Elev= 30
       0   88.32   15.65   87.84   78.09   87.84   89.64   88.39  161.84   87.84
  342.96   83.03  350.11   81.84  464.24   78.22  684.19   75.84     705   74.49
  718.53   71.84  748.43   60.45  764.81   53.03  779.88   43.84  792.85   42.53
   800.1    38.2  819.32    35.6  824.94    37.8  831.13   42.58  842.68   43.84
  857.29   53.07  867.79   59.23  894.48   73.84  906.64   75.84  920.82   79.84
  926.51   80.49  953.56   81.46 1159.86   81.75 1197.76   82.99 1394.71   83.84
#Mann= 3 ,-1 , 0
       0     .06       0  748.43    .035       0  867.79     .05       0
#XS Ineff= 2 ,-1
       0  706.56      81     900 1394.71   83.84
Permanent Ineff=
       F       F
Bank Sta=764.81,857.29
XS Rating Curve= 0 ,0
Exp/Cntr=0.3,0.1

Type RM Length L Ch R = 1 ,4046.   ,256.61,245.09,234.47
XS GIS Cut Line= 4
  6421940.591346 2054474.6389447 6421579.4678244 2054505.3281276
 6421283.5062871 2054612.9505263 6420792.4791728 2054774.3841007
#Sta/Elev= 30
       0   89.16  292.39   87.84  327.19   85.84  421.91   85.84   434.7   83.84
  448.62   73.84  477.12   63.84   500.2   53.84   500.4   53.63  509.84   43.84
  516.31      42  524.92      38  531.08    36.2  538.55    35.4   546.8    37.4
  556.46    42.5  573.47   43.84  578.09    46.7   587.8   53.84  612.22   63.84
  631.25   71.19  636.24   73.84  655.63   74.94  670.69   74.53  687.56   75.39
  702.05   78.37  789.23   80.77 1096.53   83.84 1164.68   85.84 1194.23   85.84
#Mann= 3 ,-1 , 0
       0     .05       0   500.2    .035       0  612.22     .06       0
#XS Ineff= 2 ,-1
       0  128.5289.16025  690.55 1194.23   85.84
Permanent Ineff=
       F       F
Bank Sta=500.4,578.09
XS Rating Curve= 0 ,0
Exp/Cntr=0.3,0.1

Type RM Length L Ch R = 1 ,3801.   ,152.9,161.27,167.29
XS GIS Cut Line= 5
 6421727.4485694 2054269.9042043  6421424.760641 2054283.3569864
 6421209.5158909 2054397.7057762 6421108.6199306 2054471.6961723
 6420765.5735613 2054619.6769173
#Sta/Elev= 30
       0    88.4  171.37   87.84  280.35   83.84  294.02   81.84  315.03   80.92
  324.96   80.97  333.26   79.84  340.13   77.84  348.97   73.84  361.53   63.84
  376.08   55.27  378.57   53.84  393.48   47.61  404.59   43.84  411.55      42
  418.21      38  427.81    36.2  435.23    35.2  443.14    37.4  451.28    42.5
  461.11   43.84  472.71   52.83  488.02   63.84  533.19   65.84  552.46   67.84
  572.17   73.84  581.68   81.14  586.34   83.84  606.87   85.84 1045.44   85.84
#Mann= 3 ,-1 , 0
       0     .06       0  376.08    .035       0  488.02     .05       0
Bank Sta=376.08,472.71
XS Rating Curve= 0 ,0
Exp/Cntr=0.3,0.1

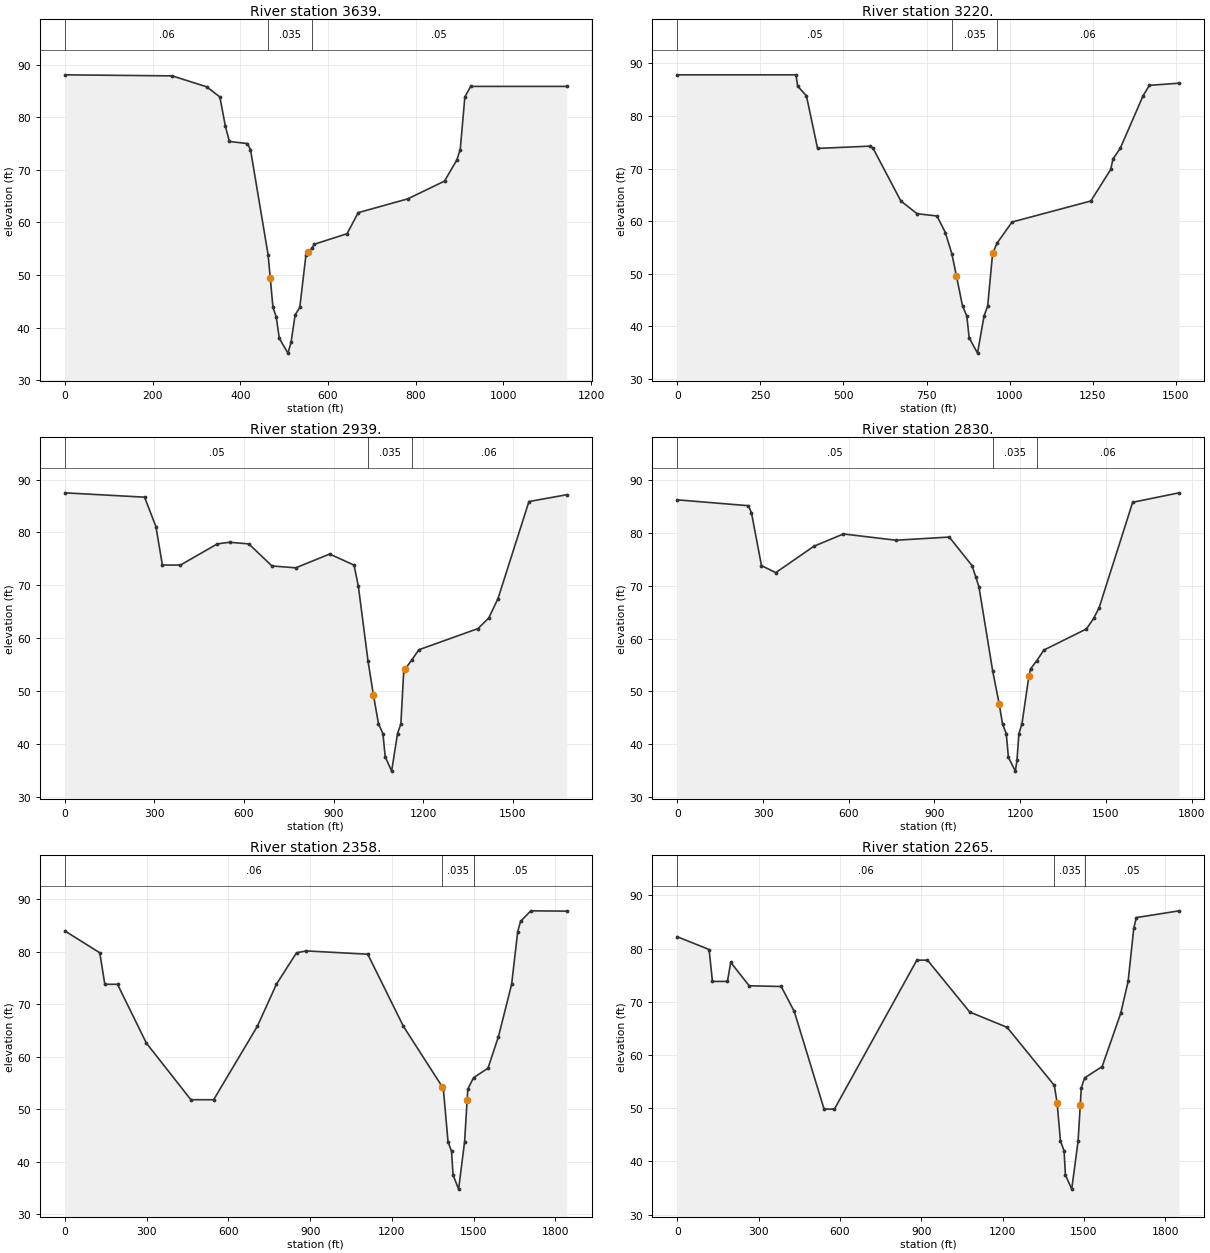
Type RM Length L Ch R = 1 ,3639.   ,393.56,418.86,402.11
XS GIS Cut Line= 4
 6421749.3093876 2054157.2370123 6421396.1734318 2054132.0129986
 6421076.6695258 2054274.9489976 6420689.9016147 2054485.1489544
#Sta/Elev= 30
       0   88.04   244.9   87.84  323.07   85.77  353.36   83.84  366.09   78.23
  375.14   75.37  416.05   74.98  423.19   73.84  463.37   53.84  468.33   49.37
  474.46   43.84  482.02      42   488.9   37.95  508.66   35.14   515.7    37.2
  524.91   42.38  535.64   43.84  549.71   53.84  555.12   54.33  562.86   55.04
  568.74   55.84  643.46   57.84  668.78   61.84     782   64.47  865.59   67.84
   893.6   71.84  901.47   73.84  912.01   83.84  925.22   85.84 1144.25   85.84
#Mann= 3 ,-1 , 0
       0     .06       0  463.37    .035       0  562.86     .05       0
Bank Sta=468.33,555.12
XS Rating Curve= 0 ,0
Exp/Cntr=0.3,0.1

Type RM Length L Ch R = 1 ,3220.   ,287.29,281.67,325.5
XS GIS Cut Line= 6
 6421816.5733454 2053955.4450443 6421303.6854602 2053787.2850788
 6421076.6695258 2053846.1410952 6420874.8775578 2053963.8530804
 6420689.9016147 2054073.1570296 6420446.0696553 2054224.5010174
#Sta/Elev= 30
       0   87.84  357.18   87.84  362.28   85.69  388.63   83.84  422.13   73.84
  580.87   74.28  589.33   73.84  672.67   63.84  721.64   61.42  781.37   60.99
  806.48   57.84  825.93   53.84  840.03   49.54  858.28   43.84     871      42
  878.22    37.8  903.36    34.9  923.07      42  933.83   43.84  948.66   53.84
  949.93   54.03   962.3   55.84 1007.19   59.84 1244.21   63.84 1304.04   69.84
 1310.82   71.84 1332.54   73.84 1401.29   83.84 1420.33   85.84 1509.73   86.25
#Mann= 3 ,-1 , 0
       0     .05       0  825.93    .035       0   962.3     .06       0
Bank Sta=840.03,949.93
XS Rating Curve= 0 ,0
Exp/Cntr=0.3,0.1

Type RM Length L Ch R = 1 ,2939.   ,109.06,109.27,98.98
XS GIS Cut Line= 5
  6421850.205348  2053795.693115 6421370.9494653 2053635.9411383
 6420992.5895431 2053585.4931582 6420706.7175923 2053728.4291099
 6420235.8696985 2053787.2850788
#Sta/Elev= 30
       0   87.49  266.92   86.67  304.99   81.11  326.61   73.84   387.1   73.84
  510.58   77.84  551.54   78.15  616.21   77.84  693.63   73.67  773.47   73.32
  886.89   75.92  968.65   73.84  983.07   69.84 1015.61   55.64  1033.5   49.31
 1050.53   43.84 1065.35      42 1072.97   37.62  1094.5    34.9 1114.29      42
 1125.47   43.84 1135.11   53.84 1140.83   54.25 1161.11   55.84 1185.96   57.84
 1383.95   61.84 1419.81   63.84 1450.88   67.51 1554.41   85.84 1681.02   87.13
#Mann= 3 ,-1 , 0
       0     .05       0 1015.61    .035       0 1161.11     .06       0
Bank Sta=1033.5,1140.83
XS Rating Curve= 0 ,0
Exp/Cntr=0.3,0.1

Type RM Length L Ch R = 1 ,2830.   ,397.69,471.43,505.66
XS GIS Cut Line= 5
 6421883.8373505 2053703.2050961 6421337.3174628 2053535.0451307
 6420933.7335268 2053493.0051393 6420631.0455984 2053644.3491271
 6420193.8297072 2053694.7971073
#Sta/Elev= 30
       0    86.3  249.24   85.19  259.71   83.84  294.73   73.84   344.7   72.51
  478.23   77.51  581.64   79.84  765.06   78.65  951.79   79.25 1031.55   73.84
 1044.31   71.74 1055.67   69.84 1103.94   53.84 1126.53   47.65 1138.26   43.84
 1151.32      42 1158.91    37.5 1183.13    34.9 1188.88      37 1195.55      42
 1206.24   43.84 1230.26   52.83 1236.34   54.27 1258.15   55.84 1282.96   57.84
 1431.77   61.84 1457.24   63.84 1476.11   65.84 1593.73   85.84 1756.11   87.63
#Mann= 3 ,-1 , 0
       0     .05       0 1103.94    .035       0 1258.15     .06       0
Bank Sta=1126.53,1230.26
XS Rating Curve= 0 ,0
Exp/Cntr=0.3,0.1

Type RM Length L Ch R = 1 ,2358.   ,103.59,92.62,89.23
XS GIS Cut Line= 5
 6422001.5493358 2053291.2132186 6421143.9334836 2053106.2372282
 6420816.0215888 2053165.0932445 6420370.3976614 2053148.2772196
 6420185.4217184 2053148.2772196
#Sta/Elev= 30
       0   84.01  128.06   79.84  146.57   73.84  193.09   73.84  298.79   62.65
  462.39   51.84  545.86   51.84  706.23   65.84  776.13   73.84   849.9   79.84
  885.98    80.2 1111.41   79.57 1242.09   65.84 1384.42   54.33 1388.86   53.84
  1405.9   43.84 1418.87      42 1424.33    37.5 1444.74    34.8 1466.68   43.84
 1476.03   51.83  1478.4   53.84 1499.37   56.03 1552.36   57.84 1590.76   63.84
 1639.27   73.84 1661.44   83.84 1672.04   85.84 1709.67   87.84 1841.41   87.78
#Mann= 3 ,-1 , 0
       0     .06       0 1384.42    .035       0 1499.37     .05       0
Bank Sta=1384.42,1476.03
XS Rating Curve= 0 ,0
Exp/Cntr=0.3,0.1

Type RM Length L Ch R = 1 ,2265.   ,411.11,411.57,375.33
XS GIS Cut Line= 5
 6422018.3653134 2053207.1332359 6421110.3015284 2053005.3412679
 6420706.7175923 2053064.1972369 6420479.7016579 2053064.1972369
 6420193.8297072 2053047.3812592
#Sta/Elev= 30
       0   82.24   117.5   79.84  129.87   73.84  185.08   73.84  197.33   77.42
  265.39   73.02  383.52   72.89  431.73    68.2  541.69   49.84   579.8   49.84
  883.91   77.84  923.15   77.84 1078.96   68.09 1216.93   65.21 1391.05   54.31
 1401.68   50.94 1413.73   43.84  1427.2      42 1431.98    37.5 1455.34    34.8
 1478.85   43.84 1486.94   50.69 1490.62   53.84 1502.92   55.71 1567.57   57.84
 1636.03   67.84 1663.32   73.84 1684.27   83.84 1693.68   85.84 1851.45   87.11
#Mann= 3 ,-1 , 0
       0     .06       0 1391.05    .035       0 1502.92     .05       0
Bank Sta=1401.68,1486.94
XS Rating Curve= 0 ,0
Exp/Cntr=0.3,0.1

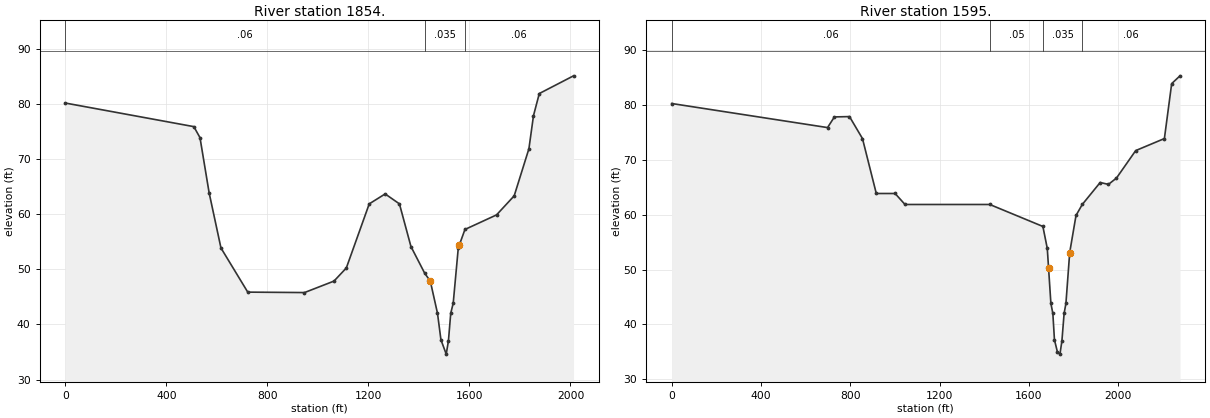
Type RM Length L Ch R = 1 ,1854.   ,227.51,258.79,268.52
XS GIS Cut Line= 5
 6422192.0691175 2052963.7118541 6421280.1430916 2052707.6981328
 6420863.1063735 2052687.5189123 6420627.6824029 2052680.7925213
 6420237.9717194 2052814.0593095
#Sta/Elev= 30
       0   80.12   509.1   75.84  533.55   73.84  569.68   63.84  616.54   53.84
  722.57   45.84  947.18   45.76  1063.9   47.84 1112.78   50.22 1203.43   61.84
 1266.44   63.64 1322.94   61.84 1368.57    54.1 1423.26   49.24 1445.12   47.84
 1473.63      42 1487.22    37.2  1508.2    34.6  1516.9      37 1526.04      42
 1535.84   43.84 1555.87   53.84  1560.2    54.4 1582.26    57.2 1707.38   59.84
 1777.26    63.3 1835.51   71.84 1853.62   77.84  1876.6   81.84 2012.09   85.05
#Mann= 3 ,-1 , 0
       0     .06       0 1423.26    .035       0 1582.26     .06       0
Bank Sta=1445.12,1560.2
XS Rating Curve= 0 ,0
Exp/Cntr=0.3,0.1

Type RM Length L Ch R = 1 ,1595.   ,601.62,1595.1,597.12
XS GIS Cut Line= 6
 6422369.1971783 2052943.6596315 6421588.0439919   2052573.50648
 6421098.3621653 2052514.3141536  6420657.110411  2052417.454009
 6420517.2012974 2052460.5029779 6420275.0509832 2052670.3666247
#Sta/Elev= 30
       0   80.22  698.06   75.84  728.81   77.78  796.33   77.84   854.5   73.84
  916.37   63.84 1000.66   63.84 1044.95   61.84  1424.6   61.84 1662.48   57.84
 1682.15   53.84 1687.87    50.3 1698.27   43.84 1707.09      42 1714.27    37.2
 1727.52      35 1738.86    34.6 1747.56   36.97 1757.49      42 1765.68   43.84
 1782.52   53.09 1810.81   59.84  1838.8   61.84 1919.01   65.84 1956.07    65.5
 1992.04   66.65 2078.08   71.65 2206.63   73.84 2239.24   83.84 2276.51   85.26
#Mann= 4 ,-1 , 0
       0     .06       0  1424.6     .05       0 1662.48    .035       0
  1838.8     .06       0
Bank Sta=1687.87,1782.52
XS Rating Curve= 0 ,0
Exp/Cntr=0.3,0.1

River Reach=Baxter River    ,Lower Reach
Reach XY= 30
 6421540.4499851 2051194.1899983 6420055.4399767 2051167.6800068
 6417503.0800234 2050584.2799906 6417277.6799867 2049881.5500087
  6417436.779981 2046765.6799998 6416303.1399811 2045559.1099864
 6415268.9299987 2045002.2299967 6414327.5399906 2044763.5700178
  6413081.199996 2043914.9899963  6411934.290019  2043702.840009
 6411271.3400057 2043835.4399992 6409163.1500126 2043742.6199777
 6406630.6800199 2045466.2999997 6405444.0000144 2046036.4299915
 6404104.8399983 2045917.0999784 6403110.4099846 2045466.2999997
  6401757.989979 2044352.5400203 6399968.0199967 2039738.4000136
 6397674.2099829 2036980.5199967 6396620.1199801 2036251.2699883
 6394551.7100029 2035972.8299935 6393623.5799844 2036251.2699883
 6393172.7700182 2036556.2300096 6392695.4399782 2038147.3099942
 6392005.9800207  2038505.310021  6391369.539999 2038531.8300001
 6390355.2300122 2037908.6500153 6389254.7300223 2035707.6499881
 6388061.4199984 2035323.1400171 6387438.2400136 2035323.1400171

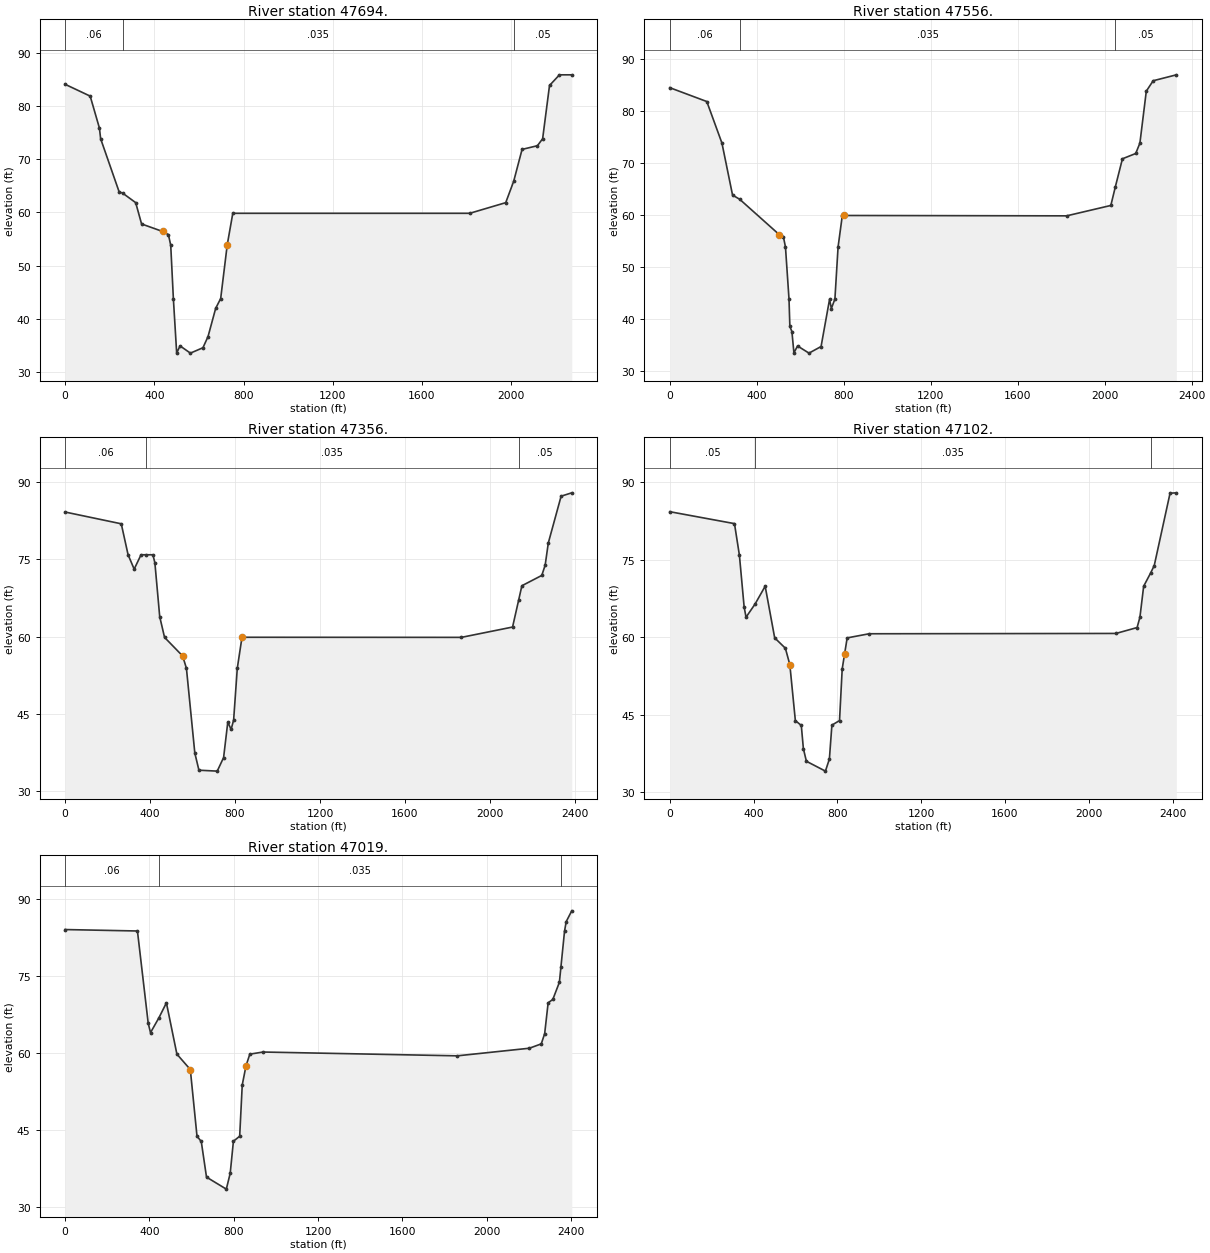
Type RM Length L Ch R = 1 ,47694.  ,157.08,138.01,115.25
XS GIS Cut Line= 5
 6421184.4600559 2050695.4960081 6421130.6488802 2051045.2687211
 6421017.6453781 2051443.4715065 6420377.2922312 2052487.4085894
 6420221.2397601  2052718.796697
#Sta/Elev= 30
       0   84.06   112.4   81.84   153.8   75.84  159.25   73.84   242.4   63.84
  257.29   63.65  316.39   61.84  342.82   57.84  437.24   56.43   463.1   55.84
  473.52   53.84  485.34   43.84  500.14   33.61  515.31   34.95  561.66   33.59
  617.94    34.6  640.78    36.7  675.05      42  697.49   43.84  726.89   53.93
   751.8   59.84 1813.96   59.84 1975.51   61.84 2011.29   65.86 2048.83   71.84
 2117.59   72.53 2141.02   73.84 2171.88   83.84 2216.45   85.84 2271.59   85.84
#Mann= 3 ,-1 , 0
       0     .06       0  257.29    .035       0 2011.29     .05       0
Bank Sta=437.24,726.89
XS Rating Curve= 0 ,0
Exp/Cntr=0.3,0.1

Type RM Length L Ch R = 1 ,47556.  ,188.27,200.04,182.63
XS GIS Cut Line= 5
 6421033.7887356 2050630.9225784 6420963.8342024 2051131.3666117
 6420920.7852335 2051384.2791801 6420242.7642683 2052600.4120442
  6420143.381727 2052744.6933309
#Sta/Elev= 30
       0   84.51   170.5   81.84  240.09   73.84  288.82   63.84  321.97   63.02
  503.05   56.25  522.49   55.84  532.18   53.84   548.4   43.84  552.39   38.55
  561.81   37.57  571.01   33.47  587.71    34.8  640.31   33.42  695.86   34.69
  734.97   43.79  743.14      42  759.52   43.84  774.03   53.84  793.31   59.84
  802.17   59.91 1824.94   59.84 2028.16   61.84 2048.34   65.33 2081.48   70.82
 2142.51   71.84 2161.82   73.84 2191.25   83.84 2222.82   85.84 2329.43   86.98
#Mann= 3 ,-1 , 0
       0     .06       0  321.97    .035       0 2048.34     .05       0
Bank Sta=503.05,802.17
XS Rating Curve= 0 ,0
Exp/Cntr=0.3,0.1

Type RM Length L Ch R = 1 ,47356.  ,211.15,254.47,293.61
XS GIS Cut Line= 6
 6420842.7590216 2050573.7481598 6420775.4950165 2051165.6712344
 6420681.3254472 2051441.4535986 6420479.5334792 2051898.8487103
 6420170.1191598 2052416.7813888 6419901.0631867 2052706.0165351
#Sta/Elev= 30
       0   84.12  264.36   81.84  296.46   75.84  325.14   73.06  357.39   75.84
  378.46   75.84  413.35   75.84  422.63   74.28  445.42   63.84  468.13   59.84
  553.43   56.23  571.18   53.84  610.69   37.43  629.99   34.11   716.2   33.93
  746.18   36.56   765.9   43.43  781.56      42  793.41   43.84  810.59   53.84
  832.77   59.86 1865.78   59.84 2106.71   61.84 2135.66    67.1 2150.59   69.84
 2244.34   71.84 2260.29   73.84 2275.09   78.14 2335.37   87.19 2385.43   87.84
#Mann= 3 ,-1 , 0
       0     .06       0  378.46    .035       0 2135.66     .05       0
Bank Sta=553.43,832.77
XS Rating Curve= 0 ,0
Exp/Cntr=0.3,0.1

Type RM Length L Ch R = 1 ,47102.  ,82.86,82.14,76.88
XS GIS Cut Line= 6
 6420721.6838408 2050560.2953777 6420566.9766574 2051064.7752741
  6420405.543083 2051407.8215961 6420170.1191598 2051851.7639257
 6419921.2424071 2052221.7158118 6419551.2904737  2052645.478921
#Sta/Elev= 30
       0   84.26  309.01   81.95   332.5   75.84  355.06   65.84  364.13   63.84
   407.4    66.4  455.47   69.84  500.91   59.84  551.91   57.84  573.15   54.67
   599.5   43.84  627.88    42.9  637.85    38.4  652.16   35.97  743.02   34.06
  761.92    36.4  773.85   42.96  810.29   43.84  823.08   53.84  834.65   56.78
  846.78   59.84  951.73   60.64 2129.45    60.7 2230.38   61.84 2243.86   63.84
 2261.69   69.84 2295.07   72.41 2312.19   73.84 2387.62   87.84 2417.71   87.91
#Mann= 3 ,-1 , 0
       0     .05       0   407.4    .035       0 2295.07     .06       0
Bank Sta=573.15,834.65
XS Rating Curve= 0 ,0
Exp/Cntr=0.3,0.1

Type RM Length L Ch R = 1 ,47019.  ,509.62,485.71,411.41
XS GIS Cut Line= 6
 6420634.2406626 2050519.9369841 6420486.2598702 2051058.0488831
 6420176.8455508 2051703.7831334 6420008.6855854 2051979.5654975
 6419739.6296596 2052322.6118195 6419490.7529069 2052598.3941363
#Sta/Elev= 30
       0   84.12  343.26   83.84  394.41   65.84   405.3   64.03  445.81   66.97
  480.71   69.84  530.51   59.84   594.2   56.84  625.94   43.84  646.19   42.82
  671.04   35.87  765.09   33.53  783.54   36.62  798.74   42.86  828.47   43.84
  840.67   53.84  858.71   57.59  876.68   59.84  939.86   60.25 1861.47   59.51
 2203.31   60.99 2259.95   61.84 2276.08   63.84 2292.52   69.84 2314.85   70.51
  2345.9   73.84  2353.4    76.9 2370.43   83.84  2378.3   85.67 2404.61   87.77
#Mann= 3 ,-1 , 0
       0     .06       0  445.81    .035       0  2353.4     .05       0
Bank Sta=594.2,858.71
XS Rating Curve= 0 ,0
Exp/Cntr=0.3,0.1