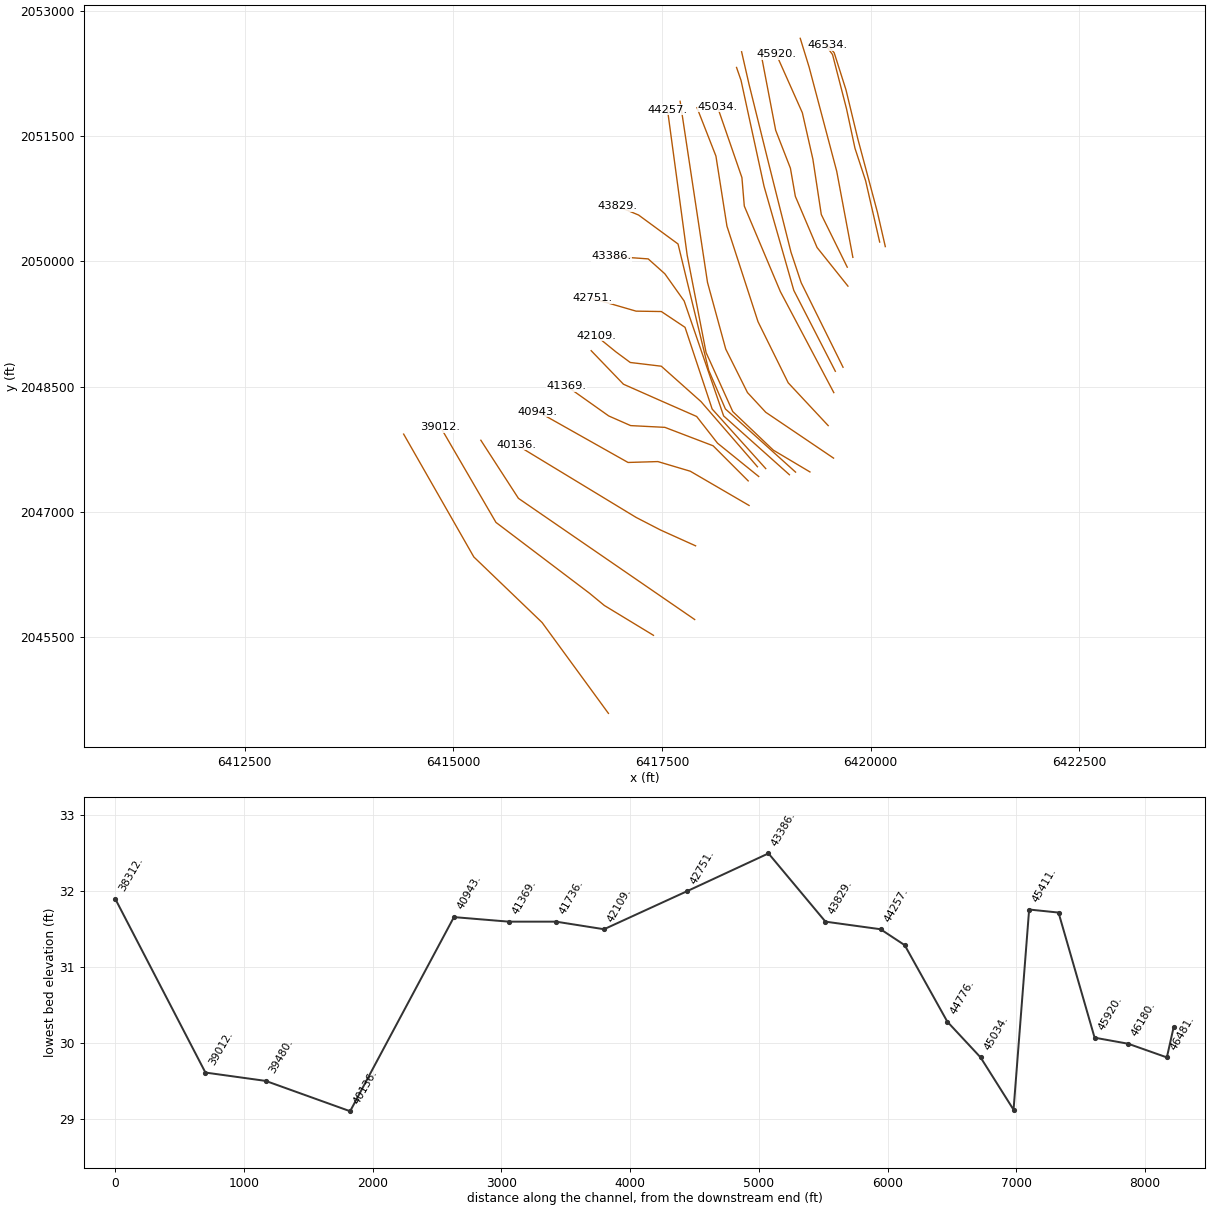
HEC-RAS study Baxter.prj: Baxter River GIS Example

--- Baxter.g02 (geometry) --- (continued)

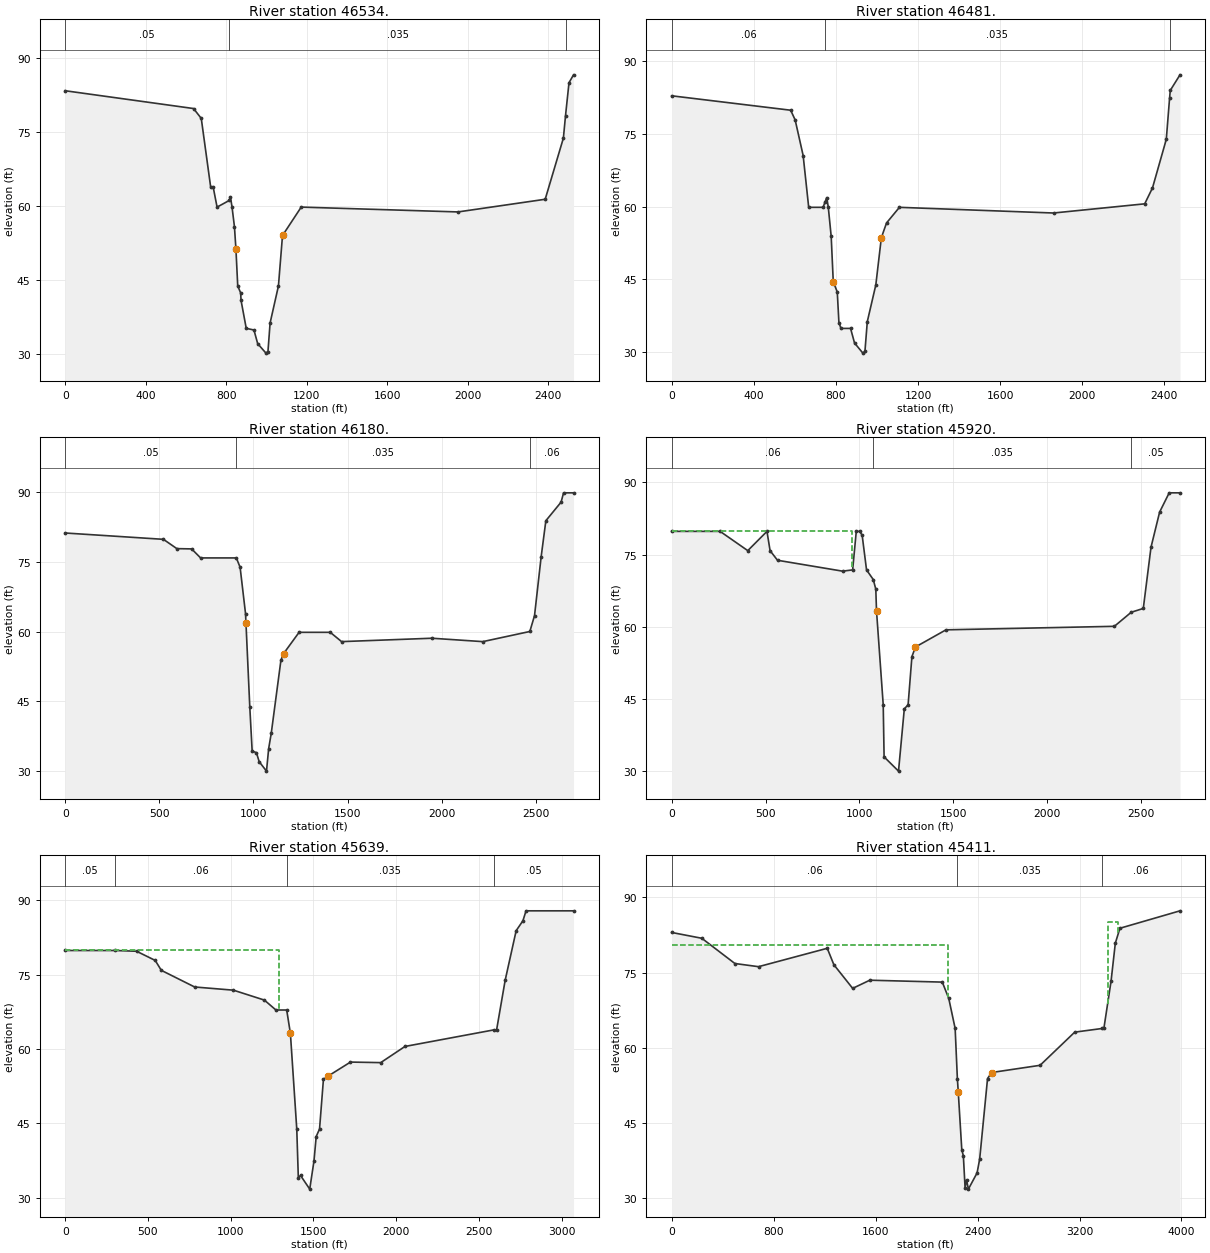
Type RM Length L Ch R = 1 ,46534.  ,45.43,52.85,56.5
XS GIS Cut Line= 6
 6420177.1145989 2050176.0834706 6420082.9450296 2050586.3937977
  6419847.521059 2051467.5520186  6419705.997657 2052053.5558464
 6419564.7432558  2052497.498176 6419484.0265159 2052591.6677453
#Sta/Elev= 30
       0   83.45  637.64   79.84  676.06   77.84  723.04   63.84   735.6   63.84
  754.61   59.84  815.79    61.2  821.32   61.84  829.02   59.84  840.98   55.84
  848.43   51.25  857.27   43.84  871.81   42.43  873.72   40.92  899.55   35.24
  937.89    34.9  956.43   32.13  997.52   30.21 1007.45   30.51 1018.07   36.32
 1059.53   43.84 1079.29   53.84 1082.58   54.25 1172.73   59.84  1951.7   58.86
 2385.03   61.43 2475.45   73.84 2486.01   78.38 2503.37   85.08 2525.86   86.68
#Mann= 3 ,-1 , 0
       0     .05       0  815.79    .035       0 2486.01     .06       0
Bank Sta=848.43,1082.58
XS Rating Curve= 0 ,0
Exp/Cntr=0.3,0.1

Type RM Length L Ch R = 1 ,46481.  ,322.97,300.51,288.13
XS GIS Cut Line= 6
 6420109.5815457 2050230.7018379 6419941.4215803 2050963.8793138
 6419813.6200084 2051354.0104204 6419712.7240481 2051824.8583142
 6419544.8331307 2052476.5118113 6419450.6635614 2052604.3133832
#Sta/Elev= 30
       0   82.81  579.62   79.84  601.48   77.84  640.38   70.51   667.4   59.84
  737.51   59.84  747.11   60.95  755.38   61.84  762.91   59.84  776.99   53.84
  787.08   44.51  806.59    42.4  814.62    36.1  824.66    34.9  871.34    34.9
  890.75   31.89  931.35   29.81  941.34   30.16  952.85    36.3  994.29   43.84
 1021.34   53.59 1046.56   56.62 1109.28   59.84 1859.92   58.67 2304.04   60.56
    2342   63.84  2409.2   73.84 2425.14   82.29 2428.61   83.92 2475.96   87.13
#Mann= 3 ,-1 , 0
       0     .06       0  747.11    .035       0 2425.14     .05       0
Bank Sta=787.08,1021.34
XS Rating Curve= 0 ,0
Exp/Cntr=0.3,0.1

Type RM Length L Ch R = 1 ,46180.  ,272.51,260.8,234.04
XS GIS Cut Line= 4
  6419788.396042 2050047.4074926 6419594.9166842  2051078.469319
 6419263.6276303  2052327.902325 6419157.7961715 2052670.7029347
#Sta/Elev= 30
       0    81.2  521.74   79.84  593.11   77.84   671.5   77.78  719.36   75.84
  909.12   75.84  929.14   73.84  957.99   63.84  960.33   61.79   980.5   43.84
  993.16   34.32 1015.99   33.95 1030.33   32.03 1069.34   29.99 1080.89   34.85
 1094.53    38.1 1145.98   53.84 1160.22   55.27  1242.4   59.84 1408.12   59.84
 1468.29   57.84 1948.09   58.57 2218.38   57.84 2468.27   60.02  2493.2   63.43
 2528.53   76.12 2553.42   83.84 2634.34   87.84 2647.54   89.84 2700.43   89.84
#Mann= 3 ,-1 , 0
       0     .05       0  909.12    .035       0 2468.27     .06       0
Bank Sta=960.33,1160.22
XS Rating Curve= 0 ,0
Exp/Cntr=0.3,0.1

Type RM Length L Ch R = 1 ,45920.  ,250.93,280.31,313.43
XS GIS Cut Line= 5
 6419721.1320369 2049929.6955073 6419410.0361197 2050560.2953777
 6419309.1401121 2051224.5272508  6419183.020138 2051779.4551273
 6418871.9242208 2052477.3189555
#Sta/Elev= 30
       0   79.84  258.04   79.84  405.42   75.84   507.7   79.84  524.26   75.84
  563.85   73.84  910.28   71.58  964.15   71.84   983.5   79.84 1001.95   79.84
 1014.85   79.03 1038.18   71.84 1073.94   69.84 1087.53   67.84 1091.28   63.34
 1127.02   43.84 1131.69   33.03 1208.51   30.07 1239.39      43 1259.61   43.84
 1279.91   53.84 1298.97   55.84 1461.41    59.4 2358.49   60.13 2448.39   63.05
 2512.62   63.84 2553.71   76.55 2599.58   83.84 2650.59   87.84 2708.16   87.84
#Mann= 3 ,-1 , 0
       0     .06       0 1073.94    .035       0 2448.39     .05       0
#XS Ineff= 1 ,-1
       0  959.21   79.84
Permanent Ineff=
       F
Bank Sta=1091.28,1298.97
XS Rating Curve= 0 ,0
Exp/Cntr=0.3,0.1

Type RM Length L Ch R = 1 ,45639.  ,229.21,228.25,215.91
XS GIS Cut Line= 6
 6419729.5400257 2049702.6795729 6419359.5881396 2050165.1194779
 6419098.9401552 2050778.9033234 6419040.0841863 2051115.2232543
  6418863.516232 2051569.2551705 6418678.5402889 2052536.1749718
#Sta/Elev= 30
       0   79.84  301.97   79.84  431.23   79.69   543.9   77.84  580.83   75.84
   782.5   72.48 1016.53   71.84  1203.7   69.84 1273.48   67.84 1338.61   67.84
 1360.94   63.13 1399.43   43.84 1408.89   34.02 1422.21   34.47 1477.81   31.72
 1503.48    37.4  1516.9   42.33 1537.07   43.84 1560.54   53.84 1590.89   54.56
 1724.03   57.34 1906.83   57.23 2053.42   60.49 2591.92   63.84  2607.2   63.84
 2658.93   73.84 2725.41   83.84 2766.29   85.84 2785.05   87.84 3072.09   87.84
#Mann= 4 ,-1 , 0
       0     .05       0  301.97     .06       0 1338.61    .035       0
 2591.92     .05       0
#XS Ineff= 1 ,-1
       0 1292.18   79.84
Permanent Ineff=
       F
Bank Sta=1360.94,1590.89
XS Rating Curve= 0 ,0
Exp/Cntr=0.3,0.1

Type RM Length L Ch R = 1 ,45411.  ,111.19,121.08,110.37
XS GIS Cut Line= 6
 6419670.6398938 2048731.0497263 6419168.9735946  2049743.847714
 6419047.0796254 2050108.8195129 6418778.0236996 2051178.3168723
  6418542.599729 2052126.7390983 6418455.1565508 2052510.1438139
#Sta/Elev= 30
       0      83  236.64   81.84  496.12    76.8   681.3   76.17 1220.72   79.84
 1272.56   76.56 1420.03   71.84 1554.57   73.47  2123.4   73.09 2173.97   69.83
 2224.13   63.84 2241.54   53.84 2248.73   51.08 2276.11   39.65 2288.58    38.4
 2302.14      32 2313.56   33.64 2327.94   31.76  2396.2      35 2416.41   37.73
 2478.35   53.84 2510.43   55.04 2890.56   56.48 3162.29    63.1 3380.07   63.84
 3391.05   63.84 3447.18   73.23 3480.91   80.87 3516.95   83.84  3988.3   87.32
#Mann= 3 ,-1 , 0
       0     .06       0 2241.54    .035       0 3380.07     .06       0
#XS Ineff= 2 ,-1
       0    2170    80.5    3420    3500      85
Permanent Ineff=
       F       F
Bank Sta=2248.73,2510.43
XS Rating Curve= 0 ,0
Exp/Cntr=0.3,0.1

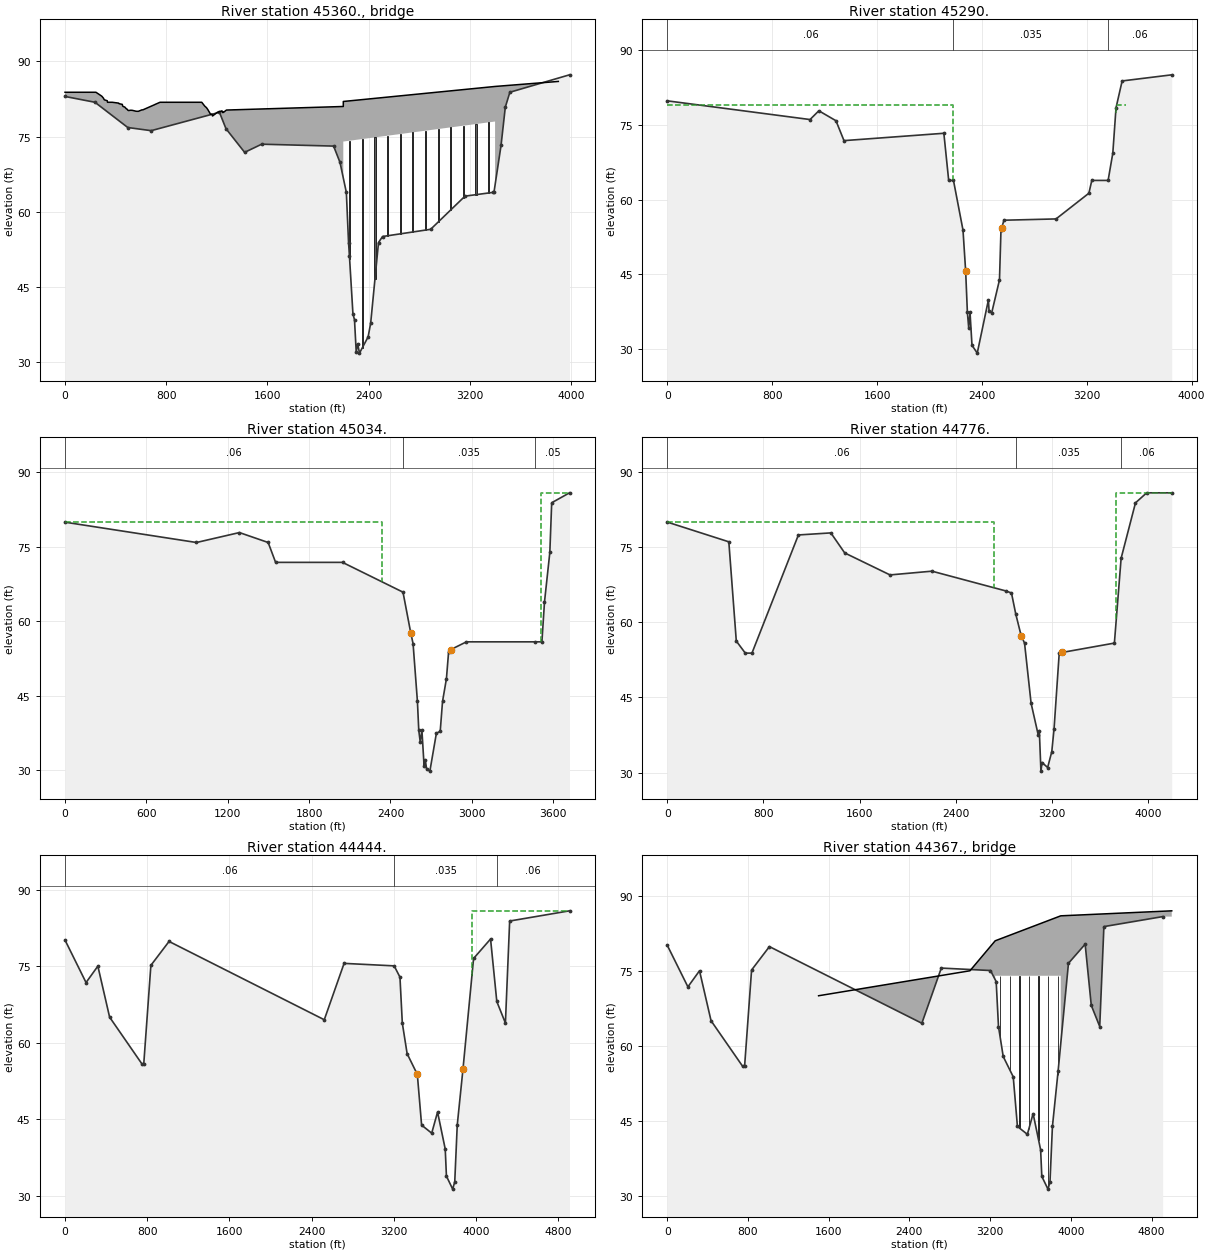
Type RM Length L Ch R = 3 ,45360.  ,,,
Node Name=Railroad
Bridge Culvert--1,0,-1,-1, 0
Deck Dist Width WeirC Skew NumUp NumDn MinLoCord MaxHiCord MaxSubmerge Is_Ogee
40,20,2.6,0, 136, 136, , , 0.95, 0, 0,0,,
       0    4.85   14.53   17.81   27.63   31.57   42.17   51.18   57.44   64.66
   71.66   79.77   86.38  104.19  119.01  124.35  138.85  144.88  159.58  164.55
  170.18   196.4  199.96   224.4  226.64  244.51  246.31  251.49  253.74  273.43
  290.48  304.22  310.25  333.81  334.66  335.96  365.36  365.66  373.82  423.93
  424.73  426.85   452.9  455.21  460.12  472.74  478.41  484.98  490.53  493.89
  497.85  502.85  521.82  524.66  532.35  561.74  570.35  579.03  608.33  615.57
  641.11  647.87   676.5  681.04  709.17  711.85  746.87  747.13  750.93  781.25
  782.67  803.96  805.36  822.43  824.29  842.86  846.32  849.93  867.05  872.15
  886.31  892.52  896.67  903.35   916.3  923.76  932.93  941.83  955.05  964.87
  975.94   985.5  997.46 1002.64 1015.62  1030.3 1036.52 1051.63 1053.66 1069.81
 1071.42 1080.93 1092.16 1105.41 1118.24  1128.8 1141.64  1145.1 1151.45 1161.03
 1162.72 1166.28 1173.24 1181.95 1185.49 1194.24  1195.5 1203.25 1204.61 1204.72
 1213.27 1221.36 1222.49 1230.49 1238.01 1240.35 1246.39 1248.23 1251.92 1269.91
 1276.11    2200    2200    3400    3400    3900
   83.84   83.84   83.84   83.84   83.84   83.84   83.84   83.84   83.84   83.84
   83.84   83.84   83.84   83.84   83.84   83.84   83.84   83.84   83.84   83.84
   83.84   83.84   83.84   83.84   83.84   83.84   83.81   83.74   83.68   83.35
   83.06   82.65   82.34   82.15   82.03   81.84   81.84   81.84   81.84   81.69
   81.67   81.56   81.42   81.12      81   80.88   80.72   80.53   80.47   80.36
   80.23   80.19   80.26   80.24   80.23   80.05   80.04   80.03   80.33   80.33
   80.61    80.7   81.01   81.07   81.37   81.41    81.8    81.8   81.84   81.84
   81.84   81.84   81.84   81.84   81.84   81.84   81.84   81.84   81.84   81.84
   81.84   81.84   81.84   81.84   81.84   81.84   81.84   81.84   81.84   81.84
   81.84   81.84   81.84   81.84   81.84   81.84   81.84   81.84   81.84   81.84
   81.84   81.84   81.48   81.05   80.77   80.39   79.84   79.69   79.41   79.49
   79.36    79.1   79.24   79.41   79.51   79.67   79.71   79.84   79.85   79.85
   79.91   79.96   79.98   80.04   80.09   80.14   79.79   79.88   79.81   80.15
   80.29      81      82      85      85      86
                                                                                
                                                                                
                                                                                
                                                                                
                                                                                
                                                                                
                                                                                
                                                                                
                                                                                
                                                                                
                                                                                
                                                                                
                                                                                
               0      74      78       0       0
       0    4.85   14.53   17.81   27.63   31.57   42.17   51.18   57.44   64.66
   71.66   79.77   86.38  104.19  119.01  124.35  138.85  144.88  159.58  164.55
  170.18   196.4  199.96   224.4  226.64  244.51  246.31  251.49  253.74  273.43
  290.48  304.22  310.25  333.81  334.66  335.96  365.36  365.66  373.82  423.93
  424.73  426.85   452.9  455.21  460.12  472.74  478.41  484.98  490.53  493.89
  497.85  502.85  521.82  524.66  532.35  561.74  570.35  579.03  608.33  615.57
  641.11  647.87   676.5  681.04  709.17  711.85  746.87  747.13  750.93  781.25
  782.67  803.96  805.36  822.43  824.29  842.86  846.32  849.93  867.05  872.15
  886.31  892.52  896.67  903.35   916.3  923.76  932.93  941.83  955.05  964.87
  975.94   985.5  997.46 1002.64 1015.62  1030.3 1036.52 1051.63 1053.66 1069.81
 1071.42 1080.93 1092.16 1105.41 1118.24  1128.8 1141.64  1145.1 1151.45 1161.03
 1162.72 1166.28 1173.24 1181.95 1185.49 1194.24  1195.5 1203.25 1204.61 1204.72
 1213.27 1221.36 1222.49 1230.49 1238.01 1240.35 1246.39 1248.23 1251.92 1269.91
 1276.11    2200    2200    3400    3400    3900
   83.84   83.84   83.84   83.84   83.84   83.84   83.84   83.84   83.84   83.84
   83.84   83.84   83.84   83.84   83.84   83.84   83.84   83.84   83.84   83.84
   83.84   83.84   83.84   83.84   83.84   83.84   83.81   83.74   83.68   83.35
   83.06   82.65   82.34   82.15   82.03   81.84   81.84   81.84   81.84   81.69
   81.67   81.56   81.42   81.12      81   80.88   80.72   80.53   80.47   80.36
   80.23   80.19   80.26   80.24   80.23   80.05   80.04   80.03   80.33   80.33
   80.61    80.7   81.01   81.07   81.37   81.41    81.8    81.8   81.84   81.84
   81.84   81.84   81.84   81.84   81.84   81.84   81.84   81.84   81.84   81.84
   81.84   81.84   81.84   81.84   81.84   81.84   81.84   81.84   81.84   81.84
   81.84   81.84   81.84   81.84   81.84   81.84   81.84   81.84   81.84   81.84
   81.84   81.84   81.48   81.05   80.77   80.39   79.84   79.69   79.41   79.49
   79.36    79.1   79.24   79.41   79.51   79.67   79.71   79.84   79.85   79.85
   79.91   79.96   79.98   80.04   80.09   80.14   79.79   79.88   79.81   80.15
   80.29      81      82      85      85      86
                                                                                
                                                                                
                                                                                
                                                                                
                                                                                
                                                                                
                                                                                
                                                                                
                                                                                
                                                                                
                                                                                
                                                                                
                                                                                
               0      74      78       0       0
Pier Skew, UpSta & Num, DnSta & Num=  ,2250, 2 ,2250, 2 , 0 , 0 , 0 ,,
      10      10
   29.12      78
      10      10
   29.12      78
Pier Skew, UpSta & Num, DnSta & Num=  ,2350, 2 ,2350, 2 , 0 , 0 , 0 ,,
      10      10
   29.12      78
      10      10
   29.12      78
Pier Skew, UpSta & Num, DnSta & Num=  ,2450, 2 ,2450, 2 , 0 , 0 , 0 ,,
      10      10
   29.12      78
      10      10
   29.12      78
Pier Skew, UpSta & Num, DnSta & Num=  ,2550, 2 ,2550, 2 , 0 , 0 , 0 ,,
      10      10
   29.12      78
      10      10
   29.12      78
Pier Skew, UpSta & Num, DnSta & Num=  ,2650, 2 ,2650, 2 , 0 , 0 , 0 ,,
      10      10
   29.12      78
      10      10
   29.12      78
Pier Skew, UpSta & Num, DnSta & Num=  ,2750, 2 ,2750, 2 , 0 , 0 , 0 ,,
      10      10
   29.12      78
      10      10
   29.12      78
Pier Skew, UpSta & Num, DnSta & Num=  ,2850, 2 ,2850, 2 , 0 , 0 , 0 ,,
      10      10
   29.12      78
      10      10
   29.12      78
Pier Skew, UpSta & Num, DnSta & Num=  ,2950, 2 ,2950, 2 , 0 , 0 , 0 ,,
      10      10
   29.12      78
      10      10
   29.12      78
Pier Skew, UpSta & Num, DnSta & Num=  ,3050, 2 ,3050, 2 , 0 , 0 , 0 ,,
      10      10
   29.12      78
      10      10
   29.12      78
Pier Skew, UpSta & Num, DnSta & Num=  ,3150, 2 ,3150, 2 , 0 , 0 , 0 ,,
      10      10
   29.12      78
      10      10
   29.12      78
Pier Skew, UpSta & Num, DnSta & Num=  ,3250, 2 ,3250, 2 , 0 , 0 , 0 ,,
      10      10
   29.12      78
      10      10
   29.12      78
Pier Skew, UpSta & Num, DnSta & Num=  ,3350, 2 ,3350, 2 , 0 , 0 , 0 ,,
      10      10
   29.12      78
      10      10
   29.12      78
BR Coef=-1 , 0 , 0 ,, 0 ,,,0.8,0,,0,
WSPro=,,,, 1 ,,,, 0 ,,,, 0 ,,,,-1 ,-1 ,-1 , 0 , 0 , 0 , 0 , 0
BC Design=,, 0 ,, 0 ,,12,2250,2250,100,10
BC HTab HWMax=95
BC HTab MaxFlow=200000
BC Use User HTab Curves=0
BC User HTab FreeFlow(D)= 0

Type RM Length L Ch R = 1 ,45290.  ,274.1,256.23,255.57
XS GIS Cut Line= 5
 6419578.4651333  2048682.823002 6419080.7116279 2049651.4244011
 6418724.0997263 2050898.6266844 6418448.4301597 2052167.0974919
  6418394.618984  2052321.804628
#Sta/Elev= 30
       0   79.84 1089.01   76.08 1156.34   77.84 1286.91   75.84 1348.02   71.84
 2109.82   73.32 2146.65   63.84  2183.2   63.84 2255.88   53.84 2276.17   45.59
 2289.32    37.3 2299.36    34.2 2309.38    37.3 2324.41    30.7 2364.53   29.12
 2449.58    39.8 2454.58    37.6 2474.58    37.2 2534.14   43.84  2545.5   53.84
 2550.79   54.28 2568.29   55.84 2965.46    56.1 3216.19   61.27 3238.34   63.84
 3362.69   63.84 3398.55   69.32 3423.05   78.44 3469.73   83.84 3848.07   85.07
#Mann= 3 ,-1 , 0
       0     .06       0  2183.2    .035       0 3362.69     .06       0
#XS Ineff= 2 ,-1
       0    2180      79    3420    3500      79
Permanent Ineff=
       F       F
Bank Sta=2276.17,2550.79
XS Rating Curve= 0 ,0
Exp/Cntr=0.3,0.1

Type RM Length L Ch R = 1 ,45034.  ,282.79,257.86,241.35
XS GIS Cut Line= 5
 6419559.9675579 2048427.2198583 6418919.2780535 2049637.9716191
 6418487.4647081 2050661.9916188 6418459.0684926 2051002.7461094
 6418165.9214518 2051850.9567342
#Sta/Elev= 30
       0   79.93   969.5   75.84 1286.17   77.84 1498.23   75.84 1553.07   71.84
 2046.48   71.84 2492.63   65.84  2550.5   57.54 2566.92   55.48    2599   43.84
 2608.83   38.04  2619.4   35.73 2632.17   38.02    2648   30.92 2657.21      32
 2666.65   30.25 2690.82   29.81 2738.85   37.44 2767.05   37.82 2784.18   43.84
 2812.88   48.41 2828.98   53.84 2843.64   54.26 2960.33   55.84 3468.07   55.84
 3517.02   55.84 3536.07   63.84 3575.45   73.84 3589.23   83.84 3720.54   85.84
#Mann= 3 ,-1 , 0
       0     .06       0 2492.63    .035       0 3468.07     .05       0
#XS Ineff= 2 ,-1
       0 2337.5379.93319 3512.78 3720.54   85.84
Permanent Ineff=
       F       F
Bank Sta=2550.5,2843.64
XS Rating Curve= 0 ,0
Exp/Cntr=0.3,0.1

Type RM Length L Ch R = 1 ,44776.  ,335.08,331.39,355.75
XS GIS Cut Line= 6
 6419492.7035528 2048032.0439584 6419013.4476701 2048544.9318436
 6418651.9037255 2049276.4276744 6418279.5685582 2050420.8633937
 6418147.4238291 2051260.7152573 6417920.4078947 2051840.8671476
#Sta/Elev= 30
       0      80   511.9   76.06  574.06   56.25  648.81   53.84  704.26   53.84
 1090.47   77.43  1360.2   77.84 1475.49   73.84 1852.28   69.45 2200.47    70.2
 2815.83   66.25 2862.07   65.84 2897.83   61.63 2942.31   57.34 2970.68   55.84
  3025.1   43.84 3084.01   37.55 3093.49   38.38 3106.96   30.28 3116.21      32
  3162.9      31 3197.25   34.19 3215.93   38.67 3259.04   53.84 3282.24   53.97
 3717.74   55.84 3773.75   72.78 3893.12   83.84 3986.27   85.84 4194.57   85.84
#Mann= 3 ,-1 , 0
       0     .06       0 2897.83    .035       0 3773.75     .06       0
#XS Ineff= 2 ,-1
       0 2713.19      80 3733.94 4194.57   85.84
Permanent Ineff=
       F       F
Bank Sta=2942.31,3282.24
XS Rating Curve= 0 ,0
Exp/Cntr=0.3,0.1

Type RM Length L Ch R = 1 ,44444.  ,191.29,187.6,190.02
XS GIS Cut Line= 6
 6419557.0550794 2047642.5285289  6418744.391697 2048191.7959351
 6418525.3263129 2048428.1568878 6418265.1358144 2048948.5157323
 6418046.5278688 2049747.2755682 6417718.6159267 2051916.5391415
#Sta/Elev= 30
       0   80.11  204.65   71.78  319.73      75  434.03      65  748.38   55.84
  766.43   55.84   835.7   75.15 1012.49   79.84 2523.31   64.49 2716.12   75.54
 3203.58   75.05 3259.91   72.84 3282.83   63.84 3329.68   57.84 3429.03   53.77
 3470.57   43.84 3568.94   42.26 3625.99    46.4 3700.55   39.15 3712.25   33.84
 3773.14   31.29 3793.21   32.73 3817.45   43.84 3873.88   54.93 3976.44    76.5
 4141.73   80.32 4202.48   68.07 4286.28   63.84 4327.64   83.84 4910.04   85.84
#Mann= 3 ,-1 , 0
       0     .06       0 3203.58    .035       0 4202.48     .06       0
#XS Ineff= 2 ,-1
       0    3220      74    3960 4908.64   85.84
Permanent Ineff=
       F       F
Bank Sta=3429.03,3873.88
XS Rating Curve= 0 ,0
Exp/Cntr=0.3,0.1

Type RM Length L Ch R = 3 ,44367.  ,,,
Node Name=Highway
Bridge Culvert--1,0,-1,-1, 0
Deck Dist Width WeirC Skew NumUp NumDn MinLoCord MaxHiCord MaxSubmerge Is_Ogee
40,90,2.6,0, 7, 7, , , 0.95, 0, 0,0,,
    1500    3000    3250    3250    3900    3900    5000
      70      75      81      81      86      86      87
                              74      74
    1500    3000    3300    3300    4000    4000    5000
      70      75      81      81      86      86      87
                              74      74
Pier Skew, UpSta & Num, DnSta & Num=  ,3300, 2 ,3340, 2 , 0 , 0 , 0 ,,
       4       4
   31.29      74
       4       4
   31.29      74
Pier Skew, UpSta & Num, DnSta & Num=  ,3395, 2 ,3435, 2 , 0 , 0 , 0 ,,
       4       4
   31.29      74
       4       4
   31.29      74
Pier Skew, UpSta & Num, DnSta & Num=  ,3490, 2 ,3530, 2 , 0 , 0 , 0 ,,
       4       4
   31.29      74
       4       4
   31.29      74
Pier Skew, UpSta & Num, DnSta & Num=  ,3585, 2 ,3625, 2 , 0 , 0 , 0 ,,
       4       4
   31.29      74
       4       4
   31.29      74
Pier Skew, UpSta & Num, DnSta & Num=  ,3680, 2 ,3720, 2 , 0 , 0 , 0 ,,
       4       4
   31.29      74
       4       4
   31.29      74
Pier Skew, UpSta & Num, DnSta & Num=  ,3775, 2 ,3815, 2 , 0 , 0 , 0 ,,
       4       4
   31.29      74
       4       4
   31.29      74
Pier Skew, UpSta & Num, DnSta & Num=  ,3870, 2 ,3910, 2 , 0 , 0 , 0 ,,
       4       4
   31.29      74
       4       4
   31.29      74
BR Coef=-1 , 0 , 0 ,, 0 ,,,0.8,0,,0,
WSPro=,,,, 1 ,,,, 0 ,,,, 0 ,,,,-1 ,-1 ,-1 , 0 , 0 , 0 , 0 , 0
BC Design=,, 0 ,, 0 ,,7,3300,3340,95,4
BC HTab HWMax=95
BC HTab MaxFlow=200000
BC Use User HTab Curves=0
BC User HTab FreeFlow(D)= 0

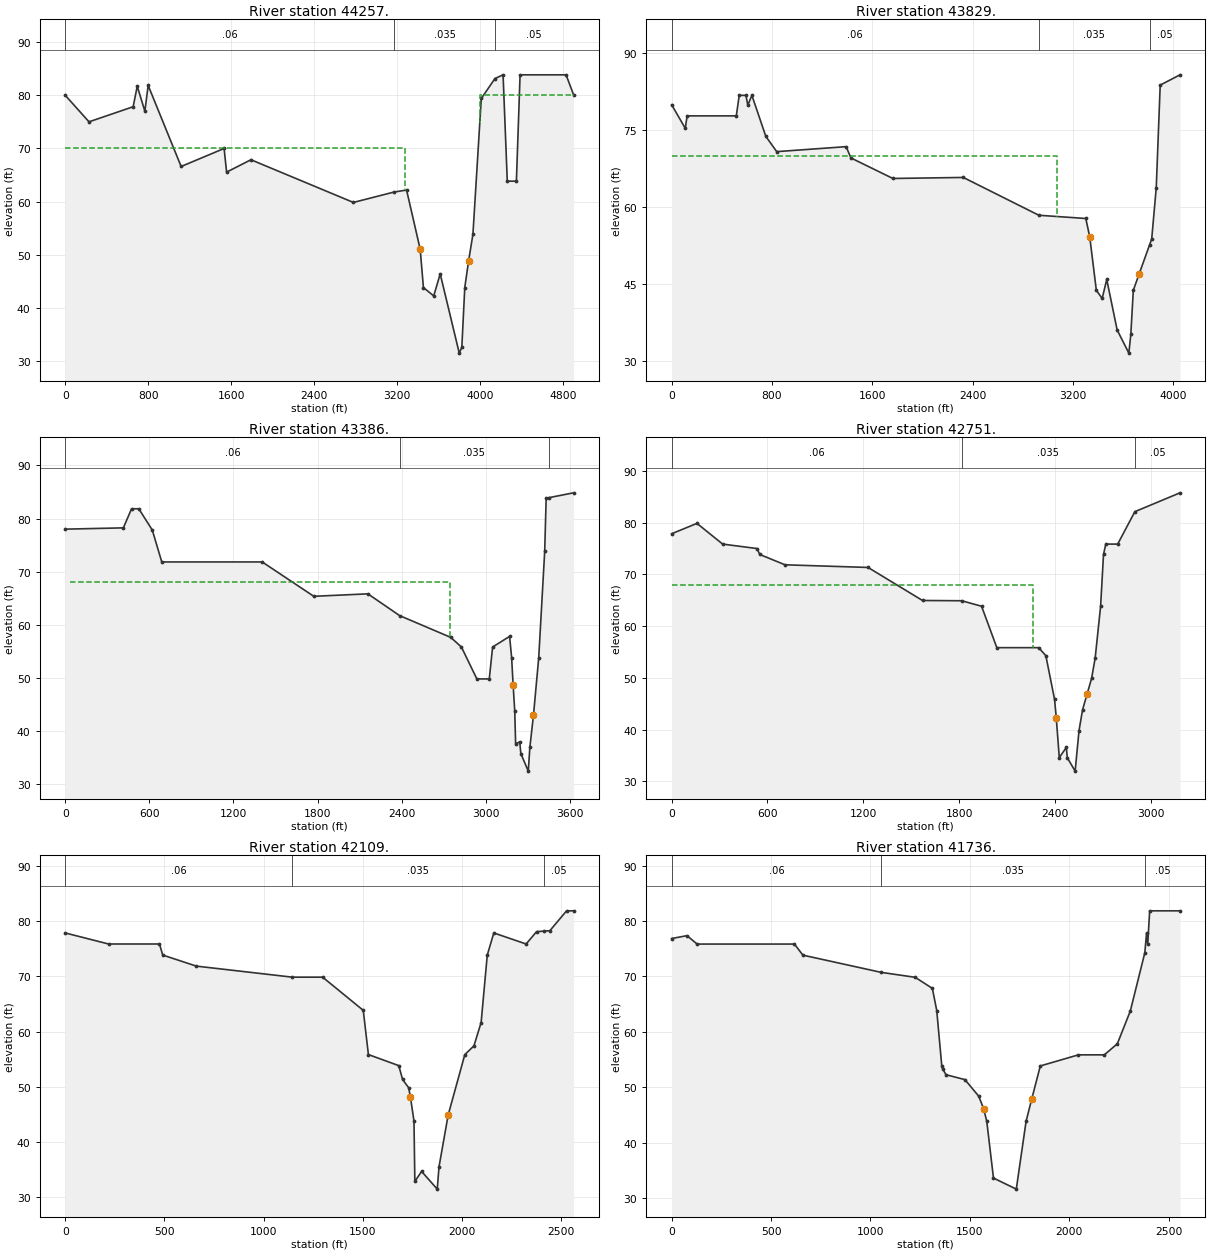
Type RM Length L Ch R = 1 ,44257.  ,119.44,428.14,566.78
XS GIS Cut Line= 6
 6419274.0956071 2047477.1160819 6418834.7329641 2047738.3947009
 6418349.2157971 2048200.2039239 6418029.7118438 2048906.4757409
 6417802.6959094 2050075.1875103 6417567.2719388 2051815.6431338
#Sta/Elev= 30
       0      80  229.64      75  655.66   77.84  695.03    81.7  768.38      77
  800.43   81.84 1118.44    66.6 1533.08   69.99 1557.11   65.54 1791.89   67.87
 2780.24   59.84 3171.67   61.79 3293.47   62.17 3424.79   51.03 3456.03   43.84
  3555.2   42.26 3617.95    46.4 3801.71    31.5 3826.52    32.6 3855.05   43.84
  3891.9   48.84 3933.55   53.84 4014.33   79.39 4146.06   83.14 4224.48   83.84
 4265.14   63.84 4352.99   63.84 4388.53   83.84 4832.35   83.84 4904.25   80.11
#Mann= 3 ,-1 , 0
       0     .06       0 3171.67    .035       0 4146.06     .05       0
#XS Ineff= 2 ,-1
       0    3280      70    4000 4904.25  80.109
Permanent Ineff=
       F       F
Bank Sta=3424.79,3891.9
XS Rating Curve= 0 ,0
Exp/Cntr=0.3,0.1

Type RM Length L Ch R = 1 ,43829.  ,414.85,442.62,553.77
XS GIS Cut Line= 6
 6419101.7316473  2047475.014061   6418260.93182 2048231.7339056
 6418061.2418729 2048694.1738106 6417693.3919129 2050207.6134997
 6417220.4420456 2050554.4433929 6416968.2020974  2050659.543395
#Sta/Elev= 30
       0      80  108.54   75.41  123.35   77.84  515.48   77.84  538.75   81.84
  592.47   81.84  606.99   79.92  639.79   81.84  750.93   73.84  837.85   70.87
 1391.42   71.84 1429.65   69.64 1764.35   65.64 2325.82   65.84 2928.65   58.47
 3302.98   57.84 3334.48   54.23 3386.99   43.84  3433.5   42.26 3469.99   45.95
 3552.93   36.12 3646.22    31.6 3661.97   35.25 3681.89   43.84 3728.17   47.01
 3811.36   52.68 3828.57   53.84 3864.81   63.84 3896.35   83.84 4054.22   85.84
#Mann= 3 ,-1 , 0
       0     .06       0 2928.65    .035       0 3811.36     .05       0
#XS Ineff= 1 ,-1
       0 3073.36      70
Permanent Ineff=
       F
Bank Sta=3334.48,3728.17
XS Rating Curve= 0 ,0
Exp/Cntr=0.3,0.1

Type RM Length L Ch R = 1 ,43386.  ,462.42,634.69,621.98
XS GIS Cut Line= 6
 6419028.1616269 2047443.4840793 6418239.9118007 2048147.6539228
 6417766.9619333 2049524.4636282 6417535.7419571 2049850.2735494
   6417336.05201 2050028.9435245  6416894.632077 2050060.4735062
#Sta/Elev= 30
       0   78.01  414.74   78.25  473.23   81.84  524.92   81.84  621.09   77.84
  688.73   71.84 1405.14   71.84 1773.03   65.38    2159   65.84 2385.14   61.75
  2750.2   57.65 2825.95   55.84 2936.09   49.84 3024.69   49.84 3048.46   55.84
 3169.64   57.84 3184.06   53.84 3194.76    48.7 3206.24   43.84 3212.62   37.63
 3242.01      38 3249.85    35.8 3302.87    32.5  3314.2      37 3340.03   43.04
  3377.4   53.84 3419.95   73.84 3430.44   83.84 3451.88   83.94 3625.61   84.84
#Mann= 3 ,-1 , 0
       0     .06       0 2385.14    .035       0 3451.88     .05       0
#XS Ineff= 1 ,-1
   37.42 2743.48      68
Permanent Ineff=
       F
Bank Sta=3194.76,3340.03
XS Rating Curve= 0 ,0
Exp/Cntr=0.3,0.1

Type RM Length L Ch R = 1 ,42751.  ,688.21,642.75,621.09
XS GIS Cut Line= 6
  6418744.391697 2047517.0540524 6418102.2664965 2048230.6398683
 6417777.4718957 2049209.1637166 6417493.7019658 2049398.3436541
 6417190.7047079 2049403.0932234 6416663.4121482 2049555.9936099
#Sta/Elev= 30
       0   77.84  158.46   79.84  319.42   75.84  535.09   74.98  551.55   73.84
  710.17   71.84 1230.07   71.33 1571.26   64.95 1816.74    64.9 1941.13   63.84
 2036.78   55.84 2298.77   55.84 2343.69    54.3 2398.43   45.84 2408.96   42.33
  2427.9   34.62 2472.18   36.58 2477.97    34.6 2527.27      32  2551.5    39.8
 2573.71   43.84 2601.59   46.83 2630.43   49.92 2652.72   53.84 2686.81   63.84
 2705.01   73.84 2719.29   75.84 2793.73   75.84  2901.3    82.1 3184.08   85.74
#Mann= 3 ,-1 , 0
       0     .06       0 1816.74    .035       0  2901.3     .05       0
#XS Ineff= 1 ,-1
       0 2262.99      68
Permanent Ineff=
       F
Bank Sta=2408.96,2601.59
XS Rating Curve= 0 ,0
Exp/Cntr=0.3,0.1

Type RM Length L Ch R = 1 ,42109.  ,377.39,372.57,283.73
XS GIS Cut Line= 6
 6418644.9204513 2047539.3136146 6417968.4614228 2048319.8432665
 6417492.7100285 2048743.5593254 6417121.0292104 2048788.1610482
 6416950.0560738 2048914.5325093 6416712.1803766 2049107.8064837
#Sta/Elev= 30
       0   77.84  218.66   75.84  475.47   75.84  491.66   73.84  661.11   71.84
 1145.17   69.84 1298.19   69.84    1503   63.84    1529   55.84 1682.18   53.84
 1701.27   51.33 1731.97   49.84  1740.4   48.24 1758.81   43.84 1763.15    32.9
 1797.26    34.7 1876.22    31.5 1885.06   35.54 1931.17    44.9 2015.23   55.84
 2061.12   57.41 2097.39   61.64 2128.42   73.84 2161.39   77.84 2324.26   75.84
  2376.9   78.07 2416.94   78.18 2443.89   78.24 2528.25   81.84  2563.4   81.84
#Mann= 3 ,-1 , 0
       0     .06       0 1145.17    .035       0 2416.94     .05       0
Bank Sta=1740.4,1931.17
XS Rating Curve= 0 ,0
Exp/Cntr=0.3,0.1

Type RM Length L Ch R = 1 ,41736.  ,287.7,367.05,432.26
XS GIS Cut Line= 6
 6418660.3117143   2047422.46406 6418166.3418276 2047821.8440016
 6417916.4260874   2048141.43647 6417492.7100285 2048327.2768791
  6417039.259472  2048527.984466 6416652.7114287 2048929.3997345
#Sta/Elev= 30
       0   76.84   76.91   77.36  128.07   75.84  617.34   75.84  660.06   73.84
  1053.9   70.73 1224.79   69.84 1311.19   67.84 1333.25   63.84 1358.61   53.84
  1363.4   53.28 1379.98   52.25 1474.92   51.37 1544.41   48.38 1569.29   46.09
 1584.85   43.84 1618.61    33.6 1733.36    31.6 1782.62   43.84 1811.24    47.9
 1854.23   53.84 2046.02   55.84 2176.11   55.84 2241.57   57.84 2306.77   63.74
 2379.89   74.28 2388.59   77.84 2394.49   75.84 2404.24   81.84 2556.77   81.84
#Mann= 3 ,-1 , 0
       0     .06       0  1053.9    .035       0 2379.89     .05       0
Bank Sta=1569.29,1811.24
XS Rating Curve= 0 ,0
Exp/Cntr=0.3,0.1

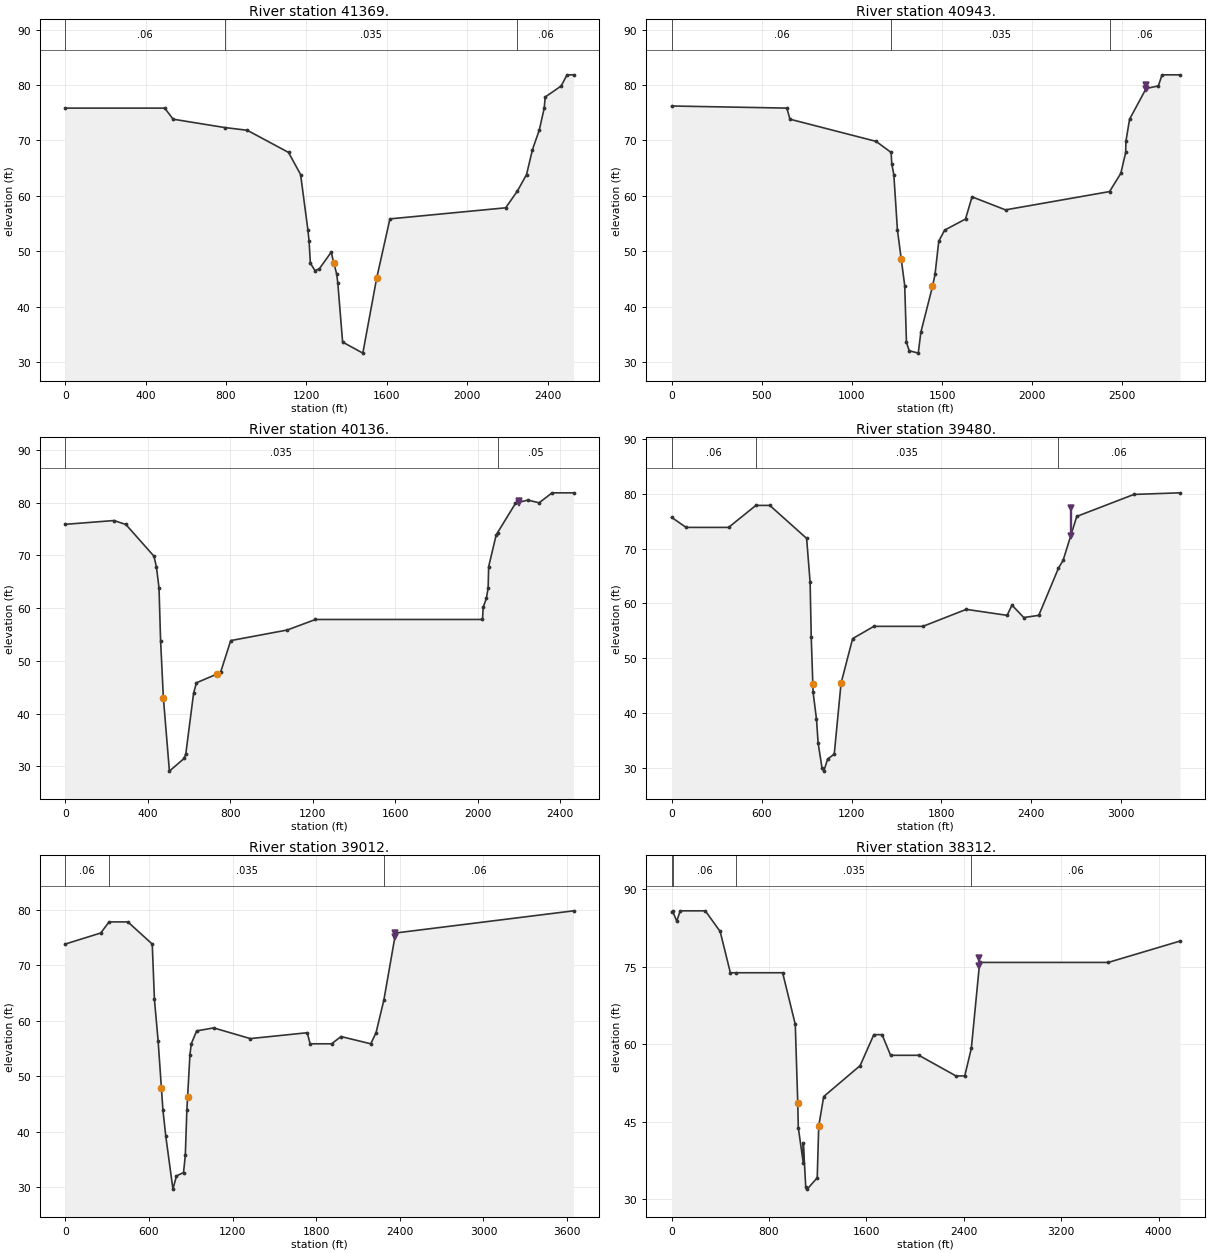
Type RM Length L Ch R = 1 ,41369.  ,425.26,426.3,407.56
XS GIS Cut Line= 6
 6418534.1917402 2047369.9141063 6418113.7918266 2047790.3140199
 6417535.7419571 2048011.0239391 6417125.8520532 2048032.0439584
 6416863.1020953 2048147.6539228  6416358.622199 2048504.9938258
#Sta/Elev= 30
       0   75.84     495   75.84   536.9   73.84  793.95   72.33  905.69   71.84
 1111.02   67.84 1171.12   63.84 1207.39   53.84 1213.27   51.84 1219.68   47.84
 1242.79   46.51 1264.13   46.82  1323.5   49.84 1335.74   47.94 1351.06   45.84
 1356.33    44.2 1380.14    33.6 1480.71    31.6 1549.43   45.11  1615.5   55.84
 2191.38   57.84 2249.83   60.88 2295.26   63.84 2324.67   68.35 2358.28   71.84
 2383.23   75.84 2387.86   77.84 2467.55   79.84 2496.43   81.84 2528.99   81.85
#Mann= 3 ,-1 , 0
       0     .06       0  793.95    .035       0 2249.83     .06       0
Bank Sta=1335.74,1549.43
XS Rating Curve= 0 ,0
Exp/Cntr=0.3,0.1

Type RM Length L Ch R = 1 ,40943.  ,826.24,806.49,525.17
XS GIS Cut Line= 5
 6418544.7017499 2047075.6341667 6417840.5319064 2047485.5240707
 6417451.6619744 2047601.1340351 6417094.3220715 2047590.6240254
 6416011.7923057 2048200.2039239
#Sta/Elev= 30
       0   76.22  639.15   75.84  656.33   73.84 1134.23   69.84  1217.7   67.84
 1220.96   65.84 1232.53   63.84 1252.65   53.84 1273.64   48.64 1292.99   43.84
 1302.66    33.6 1317.89    32.1 1368.19   31.66 1382.38    35.4 1447.09   43.69
 1461.05   45.84    1482   51.84  1514.5   53.84 1630.27   55.84 1666.52   59.84
 1852.17   57.49 2429.48   60.79 2491.93   64.07 2518.97   67.84 2520.22   69.84
 2540.59   73.84 2632.38   79.37 2700.12   79.84 2720.74   81.84 2820.33   81.84
#Mann= 3 ,-1 , 0
       0     .06       0  1217.7    .035       0 2429.48     .06       0
Levee=0,,,-1,2630.25,79.95625,,	380
Bank Sta=1273.64,1447.09
XS Rating Curve= 0 ,0
Exp/Cntr=0.3,0.1

Type RM Length L Ch R = 1 ,40136.  ,661.44,655.91,599.95
XS GIS Cut Line= 4
 6417903.5918697 2046592.1742424  6417484.132157 2046781.1770076
 6417190.7047079 2046932.6234269 6415759.5523575 2047800.8239823
#Sta/Elev= 30
       0   75.87  236.55   76.59  294.15   75.84  430.11   69.84  442.09   67.84
  454.69   63.84  462.37   53.84  475.83   43.01  505.14    29.1  576.25    31.5
  584.74    32.4  622.26   43.84  636.05   45.84  736.07    47.5  753.33   47.84
  802.34   53.84 1076.03   55.84 1213.27   57.84 2022.79   57.84 2026.26   60.17
 2041.79   61.84 2050.26   63.84 2052.71   67.84  2089.1   73.84 2096.25   74.32
 2182.76   79.84 2242.23   80.47  2297.4   79.95 2360.19   81.84 2464.19   81.84
#Mann= 2 ,-1 , 0
       0    .035       0 2096.25     .05       0
Levee=0,,,-1,2197.8,80.22,,	380
Bank Sta=475.83,736.07
XS Rating Curve= 0 ,0
Exp/Cntr=0.3,0.1

Type RM Length L Ch R = 1 ,39480.  ,474.01,468.09,436.4
XS GIS Cut Line= 3
 6417893.0819074 2045709.3344237 6415781.0439683 2047160.8173223
 6415330.6130551 2047856.6583672
#Sta/Elev= 30
       0   75.66   96.61   73.84  379.71   73.84  561.59   77.84  654.78   77.84
  900.46   71.84  923.73   63.84  931.22   53.84  941.88   45.31   943.7   43.84
  966.28   38.92  977.12   34.62 1003.42   30.02 1015.09    29.5  1040.2   31.68
 1084.75    32.6 1130.21   45.51 1207.42   53.61 1348.98   55.84  1676.3   55.84
 1965.59   58.93 2238.46   57.84 2270.31   59.71 2349.15   57.44  2449.3   57.84
 2580.91   66.44 2611.63   67.84 2702.79   75.84 3084.13   79.84 3391.62   80.13
#Mann= 3 ,-1 , 0
       0     .06       0  561.59    .035       0 2580.91     .06       0
Levee=0,,,-1,2661.54,77.33,,	380
Bank Sta=941.88,1130.21
XS Rating Curve= 0 ,0
Exp/Cntr=0.3,0.1

Type RM Length L Ch R = 1 ,39012.  ,742.69,700.15,609.51
XS GIS Cut Line= 5
 6417399.1119734 2045520.1544863 6416810.5521416 2045877.4943892
 6416631.8821665 2046024.6343826 6415512.0072129 2046872.3175141
 6414847.1531781  2048014.308323
#Sta/Elev= 30
       0   73.84  254.94   75.84  314.61   77.84  449.27   77.84  624.32   73.84
     640   63.84  666.56   56.33  690.09   47.81  701.08   43.84  721.17    39.2
  772.72   29.61  798.12      32  848.65    32.6  861.46    35.7  872.52   43.84
  877.88   46.27  894.55   53.84  904.32   55.84  942.79   58.17 1064.65   58.71
 1327.75   56.78 1736.01   57.84 1756.62   55.84 1910.57   55.84 1978.27   57.15
 2191.68   55.84 2229.53   57.84 2285.94   63.78 2369.72   75.84 3645.96   79.84
#Mann= 3 ,-1 , 0
       0     .06       0  314.61    .035       0 2285.94     .06       0
Levee=0,,,-1,2364.84,75.81,,	380
Bank Sta=690.09,877.88
XS Rating Curve= 0 ,0
Exp/Cntr=0.3,0.1

Type RM Length L Ch R = 1 ,38312.  ,374.38,367.97,323.69
XS GIS Cut Line= 4
  6416859.415654 2044585.2038341 6416064.3219057 2045673.7250315
 6415246.5330724 2046458.8286426 6414405.7332451 2047930.2283403
#Sta/Elev= 30
       0   85.65    7.24   85.79   41.85   83.84   70.01   85.84  276.11   85.84
   398.3   81.84  482.18   73.84     531   73.84  911.56   73.84 1015.52   63.84
 1035.88   48.65 1040.27   43.84 1080.99      37 1081.52    40.8 1101.68    32.3
 1113.67    31.9 1195.81    34.1 1208.17    44.1 1249.02   49.84 1548.48   55.84
 1660.85   61.84 1728.69   61.84 1798.53   57.84 2031.24   57.84 2335.57   53.84
 2407.72   53.84  2461.9   59.17 2530.41   75.84  3587.1   75.84 4176.32   79.98
#Mann= 4 ,-1 , 0
       0     .06       0    7.24     .06       0     531    .035       0
  2461.9     .06       0
Levee=0,,,-1,2527.47,76.67,,	380
Bank Sta=1035.88,1208.17
XS Rating Curve= 0 ,0
Exp/Cntr=0.3,0.1