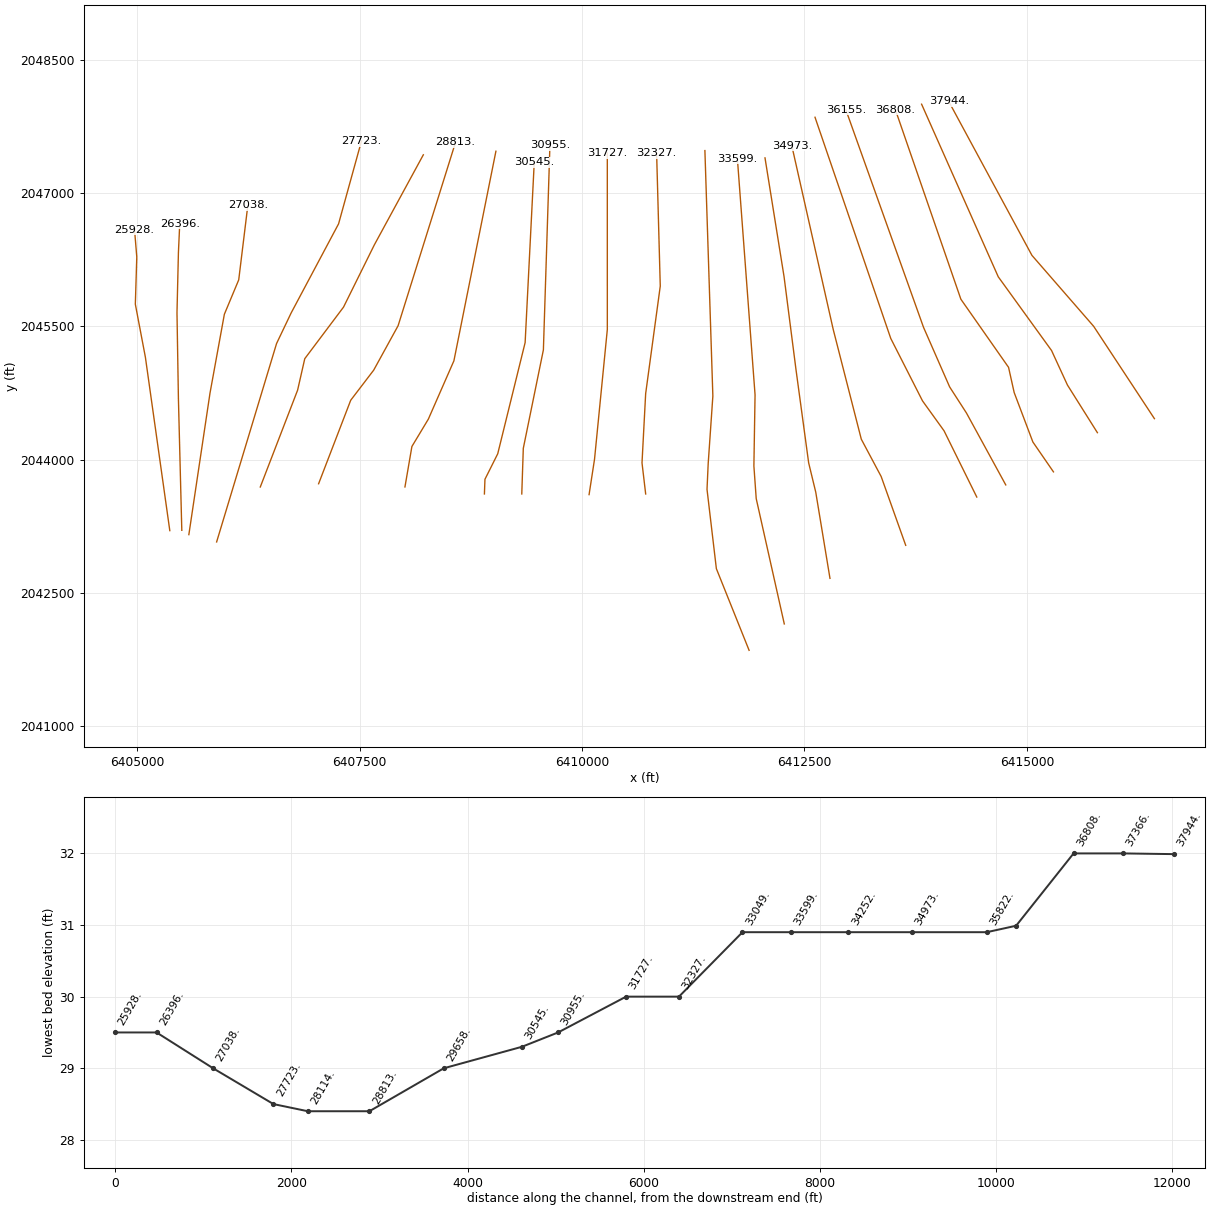
HEC-RAS study Baxter.prj: Baxter River GIS Example

--- Baxter.g02 (geometry) --- (continued)

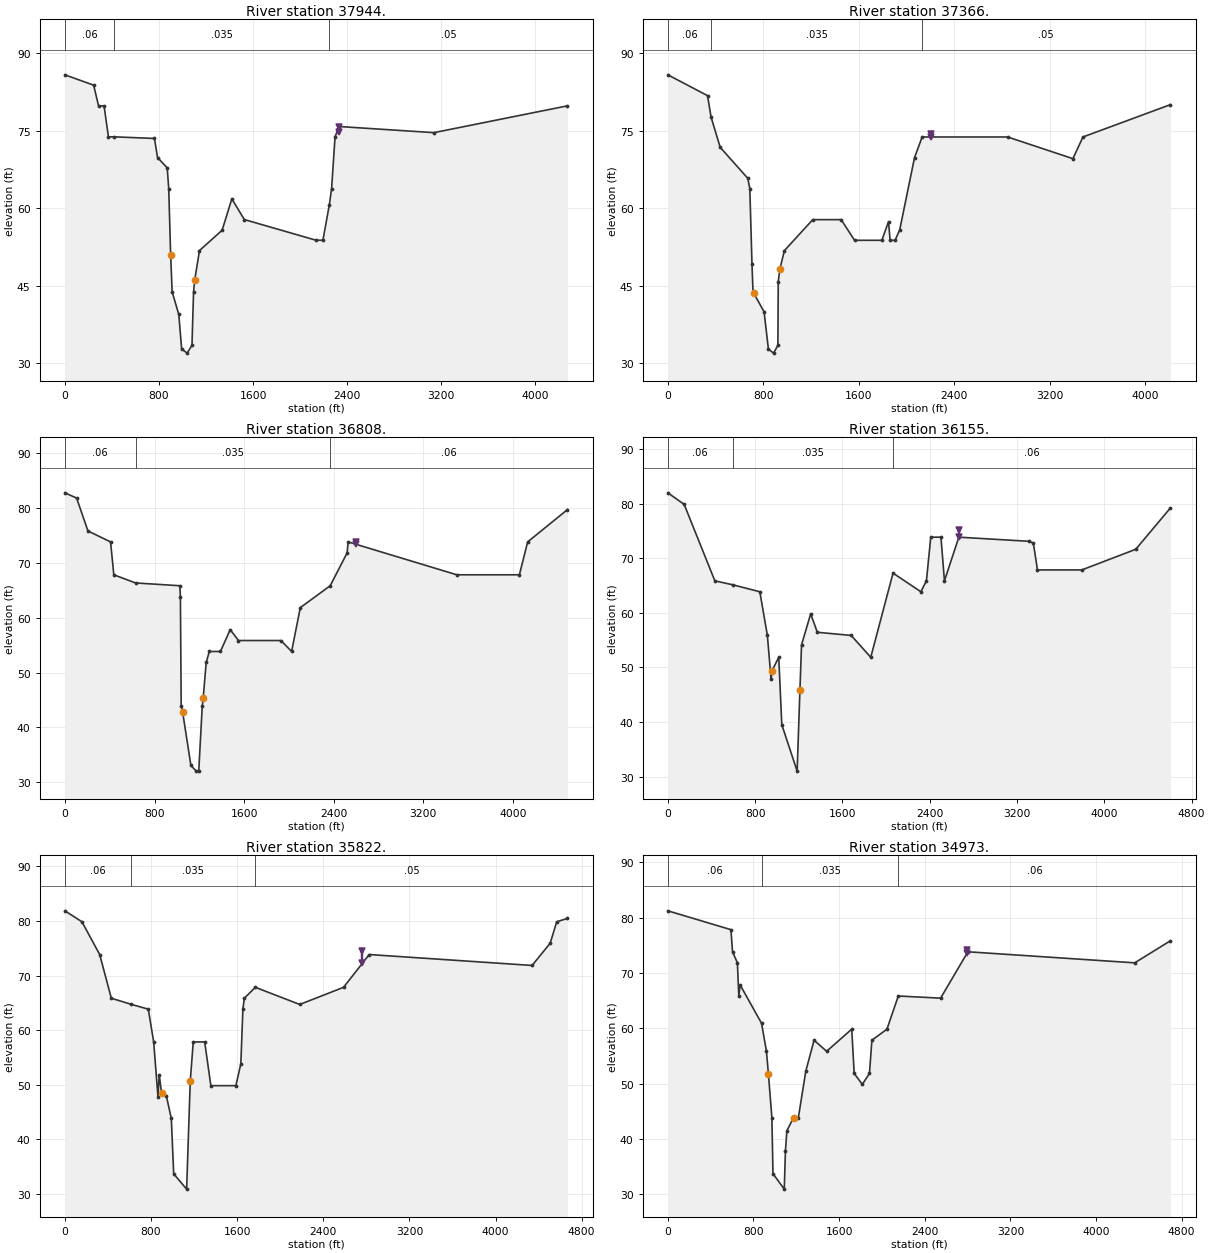
Type RM Length L Ch R = 1 ,37944.  ,606.16,578.05,519.9
XS GIS Cut Line= 5
 6416434.1628402 2044461.9290764 6415971.7229352   2045166.09892
 6415751.0129688 2045502.4188509 6415057.3531349 2046301.1786868
 6414121.9633152 2048035.3283424
#Sta/Elev= 30
       0   85.84  244.26   83.84  285.92   79.84  332.83   79.84  369.94   73.84
  418.97   73.84   761.4   73.53  787.53   69.84  869.79   67.84  882.67   63.84
  898.95      51  911.77   43.84  968.36   39.47  992.51    32.8 1038.87   31.99
  1080.3    33.5 1093.83   43.84 1103.96   46.21 1144.27   51.84 1336.67   55.77
 1419.25   61.84 1525.21   57.84 2134.18   53.84 2193.73   53.84 2248.61   60.72
 2267.59   63.84 2296.83   73.84 2331.18   75.84 3137.03   74.65 4272.96   79.84
#Mann= 3 ,-1 , 0
       0     .06       0  418.97    .035       0 2248.61     .05       0
Levee=0,,,-1,2330.57,74.77473,,	380
Bank Sta=898.95,1103.96
XS Rating Curve= 0 ,0
Exp/Cntr=0.3,0.1

Type RM Length L Ch R = 1 ,37366.  ,589.97,558.31,507.96
XS GIS Cut Line= 5
 6415793.0529601 2044304.2791207 6415456.7330292 2044840.2889987
 6415278.0630541 2045229.1589307 6414678.9932126 2046059.4487483
  6413817.173366 2048003.7983133
#Sta/Elev= 30
       0   85.87  332.34   81.84  362.04   77.68  438.32   71.84  669.63   65.84
  686.69   63.84  704.62   49.32  713.45   43.84  717.84   43.66  806.15      40
  842.34    32.8  885.71      32  921.86    33.5  924.98   45.84  938.07   48.23
  976.46   51.84 1214.05   57.84 1452.13   57.84 1564.35   53.84 1793.01   53.84
 1849.03   57.45 1862.29   53.84 1903.78   53.84 1942.65   55.84 2066.85   69.84
  2130.9   73.84 2847.47   73.84  3394.2   69.64 3478.39   73.84 4211.37    80.1
#Mann= 3 ,-1 , 0
       0     .06       0  362.04    .035       0  2130.9     .05       0
Levee=0,,,-1,2202.75,74.34217,,	380
Bank Sta=717.84,938.07
XS Rating Curve= 0 ,0
Exp/Cntr=0.3,0.1

Type RM Length L Ch R = 1 ,36808.  ,564.92,652.32,662.06
XS GIS Cut Line= 6
 6415299.0830734 2043862.8591877 6415067.8630973 2044199.1791186
 6414857.6631404  2044756.209016 6414794.6031771 2045039.9789459
  6414258.593299 2045807.2088001 6413522.8934265   2047940.73835
#Sta/Elev= 30
       0    82.8  104.68   81.84  205.51   75.84  407.57   73.84  436.54   67.84
  630.47   66.35  1026.1   65.84 1031.08   63.84 1038.18   43.84 1051.62   42.71
 1124.73   33.04 1172.84      32 1194.97      32 1226.01   43.84 1235.14    45.4
 1261.36   51.84 1289.37   53.84 1388.34   53.84 1475.88   57.83 1549.58   55.84
 1929.04   55.84 2024.06   53.84 2101.65   61.84 2368.46   65.84 2519.88   71.84
 2528.36   73.84 3498.69   67.84 4057.72   67.84 4131.58   73.84 4486.93   79.74
#Mann= 3 ,-1 , 0
       0     .06       0  630.47    .035       0 2368.46     .06       0
Levee=0,,,-1,2598.81,73.87553,,	380
Bank Sta=1051.62,1235.14
XS Rating Curve= 0 ,0
Exp/Cntr=0.3,0.1

Type RM Length L Ch R = 1 ,36155.  ,323.19,333.66,348.72
XS GIS Cut Line= 5
 6414763.0731954 2043715.7192416 6414321.6532624 2044524.9890398
 6414132.4733249 2044819.2689794 6413838.1933854 2045491.9088412
 6412965.8635764   2047940.73835
#Sta/Elev= 30
       0   81.96  149.37   79.84  430.49   65.84  593.77   65.12  842.64   63.84
  911.84   55.84  945.72   47.84  953.66   49.33 1015.97   51.84 1043.98    39.5
 1184.61   30.99 1210.23   45.88 1224.79    54.1  1308.7    59.8 1369.41   56.42
 1679.83   55.84 1859.29   51.84  2063.4   67.26 2318.54   63.84 2369.36   65.84
 2409.21   73.84 2502.62   73.84 2534.49   65.84 2666.57   73.84 3310.38   73.08
 3349.24   72.76 3387.07   67.84 3793.69   67.84 4287.41   71.62 4605.43   79.19
#Mann= 3 ,-1 , 0
       0     .06       0  593.77    .035       0  2063.4     .06       0
Levee=0,,,-1,2670.33,75.14,,	380
Bank Sta=953.66,1210.23
XS Rating Curve= 0 ,0
Exp/Cntr=0.3,0.1

Type RM Length L Ch R = 1 ,35822.  ,862.61,848.98,790.43
XS GIS Cut Line= 5
 6414437.2632268 2043579.0892578 6414069.4133142 2044325.2990927
 6413827.6833757 2044661.6190236 6413470.3434728 2045365.7888671
 6412619.0336358 2047856.6583672
#Sta/Elev= 30
       0   81.84  157.88   79.84     323   73.84  431.11   65.84  616.74   64.72
  774.58   63.84  824.42   57.84  864.26   47.84  875.96   51.84  897.52   48.47
  941.69   48.02  988.21   43.84 1010.49    33.7 1130.63    30.9 1164.22   50.66
 1192.04   57.84 1298.37   57.84 1355.48   49.84 1587.98   49.84 1634.07   53.84
 1653.19   63.84 1666.69   65.84  1768.7   67.84 2181.32    64.7 2588.33   67.84
 2826.78   73.84 4339.45   71.84 4507.73   75.91 4568.38   79.84 4668.11   80.45
#Mann= 3 ,-1 , 0
       0     .06       0  616.74    .035       0  1768.7     .05       0
Levee=0,,,-1,2762.86,74.57,,	380
Bank Sta=897.52,1164.22
XS Rating Curve= 0 ,0
Exp/Cntr=0.3,0.1

Type RM Length L Ch R = 1 ,34973.  ,757.28,720.97,618.53
XS GIS Cut Line= 5
 6413638.5034382 2043035.1968962 6413362.6159919  2043810.309234
 6413139.2784994 2044230.7091476 6412823.9785878 2045465.6338643
 6412358.1305197 2047536.1201125
#Sta/Elev= 30
       0   81.25  589.19   77.84  604.08   73.84  649.58   71.84  662.62   65.84
   675.1   67.84  875.31    60.9     921   55.84  939.35   51.73  971.76   43.84
  981.99    33.7  1087.4    30.9 1098.45   37.84 1112.18   41.47 1174.44   43.84
 1219.33   43.84  1288.5   52.22 1365.81   57.84 1483.54   55.84 1717.92   59.84
 1740.77   51.84 1816.64   49.84 1883.64   51.84 1906.33   57.84 2046.95   59.84
 2153.04   65.84 2548.19   65.45 2803.38   73.84 4361.75   71.84 4695.57   75.83
#Mann= 3 ,-1 , 0
       0     .06       0  875.31    .035       0 2153.04     .06       0
Levee=0,,,-1,2796.42,74.19,,	380
Bank Sta=939.35,1174.44
XS Rating Curve= 0 ,0
Exp/Cntr=0.3,0.1

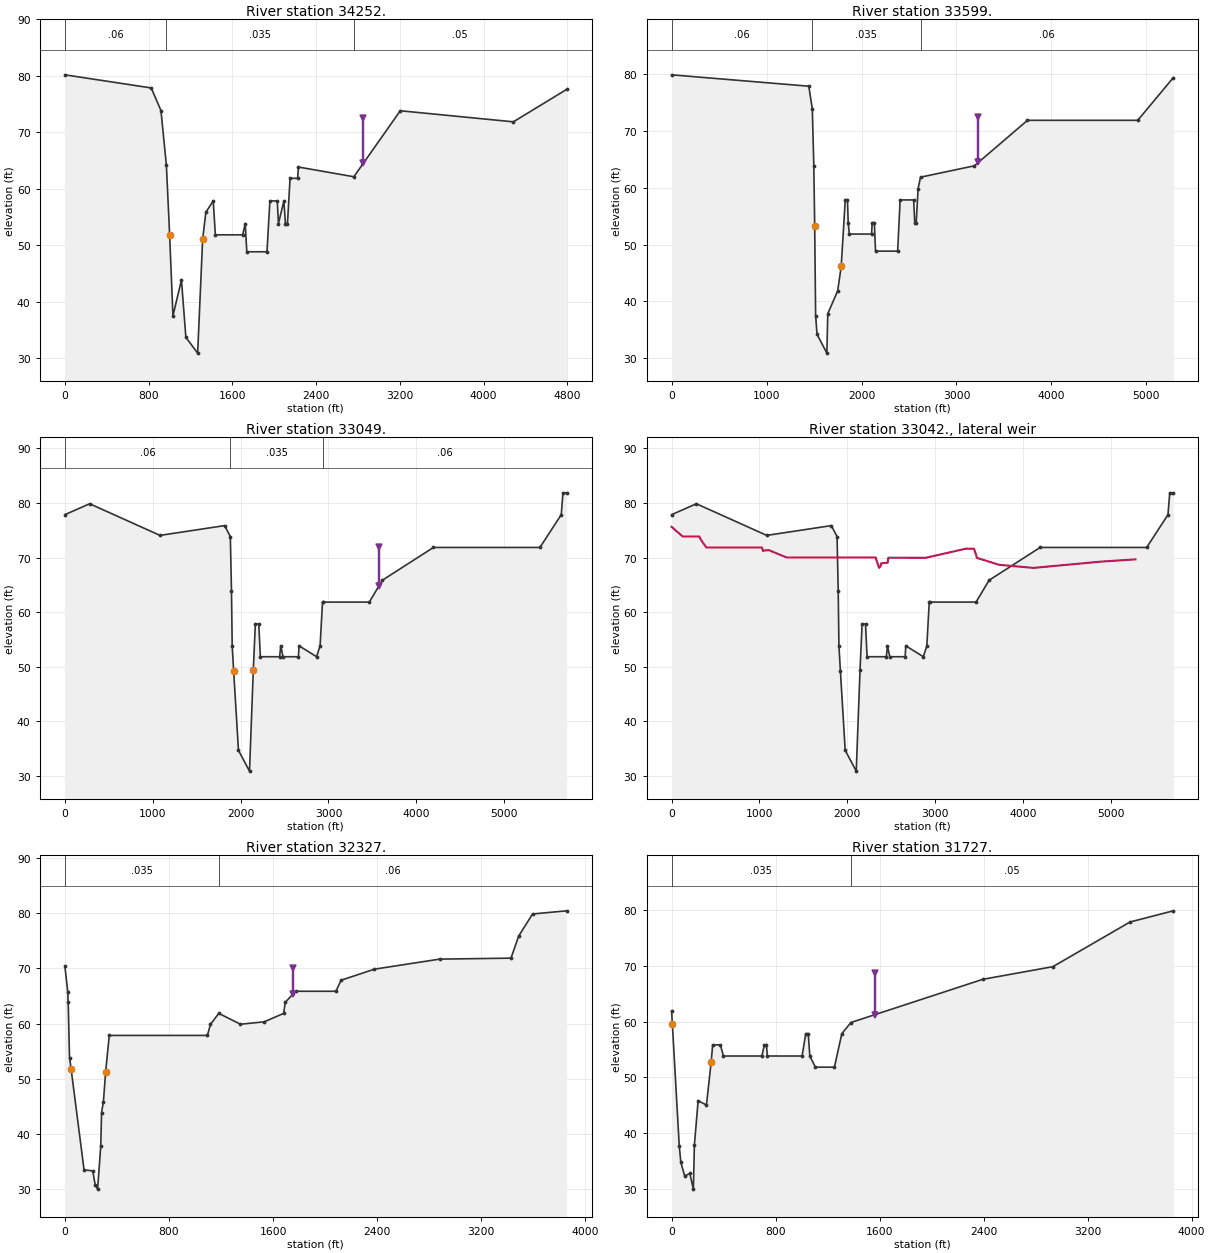
Type RM Length L Ch R = 1 ,34252.  ,678.44,652.64,592.59
XS GIS Cut Line= 6
  6412787.195968 2042663.4884821 6412627.4375539 2043633.4502685
 6412547.5583468 2043964.3783985 6412406.3630187 2045005.7454192
 6412270.9692171 2046061.8170245 6412056.8718027 2047399.1843019
#Sta/Elev= 30
       0   80.16     825   77.84  918.14   73.84     970   64.14 1001.12   51.77
  1032.6    37.5  1113.9   43.84 1156.11    33.7 1268.72    30.9 1316.59   51.12
 1347.24   55.84 1417.61   57.84 1437.97   51.84 1699.35   51.84 1723.34   53.84
  1738.2   48.84 1931.03   48.84 1958.92   57.84 2029.53   57.84  2040.8   53.84
 2092.51   57.84 2107.49   53.84 2126.81   53.84 2151.74   61.84 2223.73   61.84
 2231.78   63.84 2761.17   62.12 3204.93    73.8 4285.47   71.84 4793.47   77.57
#Mann= 3 ,-1 , 0
       0     .06       0     970    .035       0 2761.17     .05       0
Levee=0,,,-1,2852,72.5,,	380
Bank Sta=1001.12,1316.59
XS Rating Curve= 0 ,0
Exp/Cntr=0.3,0.1

Type RM Length L Ch R = 1 ,33599.  ,555.14,550.5,509.63
XS GIS Cut Line= 5
  6412273.686773 2042149.9792871 6411958.2476987 2043560.6967645
 6411931.9726745 2043928.5466771 6411945.1102102 2044729.9340391
 6411746.4840064   2047390.05527
#Sta/Elev= 30
       0   79.84 1444.77   77.84 1481.87   73.84  1497.6   63.84 1506.98    53.3
 1516.71    37.5 1531.67    34.2 1634.94    30.9 1644.72   37.84 1748.91   41.84
 1786.01   46.14 1828.86   57.84 1852.36   57.84 1859.64   53.84 1871.85   51.84
 2105.99   51.84 2112.11   53.84 2135.39   53.84 2147.47   48.84 2380.46   48.84
  2406.7   57.84 2549.17   57.84 2560.39   53.84  2575.8   53.84 2596.08   59.84
 2621.52   61.84 3188.61   63.84 3748.04   71.84 4909.13   71.84 5283.36   79.34
#Mann= 3 ,-1 , 0
       0     .06       0 1481.87    .035       0 2621.52     .06       0
Levee=0,,,-1,3232.02,72.5,,	380
Bank Sta=1506.98,1786.01
XS Rating Curve= 0 ,0
Exp/Cntr=0.3,0.1

Type RM Length L Ch R = 1 ,33049.  ,701.35,721.15,745.3
XS GIS Cut Line= 6
 6411878.0788058 2041852.8221331 6411510.2288458 2042772.4469383
 6411405.1288911 2043665.7967666 6411418.2663795 2043954.8217013
 6411470.8163806 2044716.7965034 6411381.3219238 2047481.3457788
#Sta/Elev= 30
       0   77.84  281.95   79.84 1082.55   74.05  1817.7   75.84 1882.94   73.84
 1896.07   63.84 1904.07   53.84 1920.95   49.21  1975.5    34.7 2101.17    30.9
 2144.39   49.42 2167.68   57.84 2206.58   57.84 2224.57   51.84 2443.89   51.84
 2456.81   53.84 2482.42   51.84 2657.89   51.84 2664.79   53.84 2864.66   51.84
 2904.43   53.84 2932.01   61.84 2943.09   61.84 3464.45   61.84    3613   65.84
 4194.16   71.84 5406.33   71.84 5648.91   77.84 5668.59   81.84 5709.08   81.84
#Mann= 3 ,-1 , 0
       0     .06       0 1882.94    .035       0 2943.09     .06       0
Levee=0,,,-1,3576.91,72,,	380
Bank Sta=1920.95,2144.39
XS Rating Curve= 0 ,0
Exp/Cntr=0.3,0.1

Type RM Length L Ch R = 6 ,33042.  ,,,
Node Name=South LS
Lateral Weir Pos= 0
Lateral Weir End=                ,                ,        ,Southside
Lateral Weir Distance=0
Lateral Weir TW Multiple XS=0
Lateral Weir WD=20
Lateral Weir Coef=2
Lateral Weir WSCriteria=-1
Lateral Weir Flap Gates= 0
Lateral Weir Hagers EQN= 0 ,,,,,
Lateral Weir SS=0.05,0.05,
Lateral Weir Type= 0
Lateral Weir Connection Pos and Dist= 0 ,
Lateral Weir SE= 27
       0   75.61  126.44   73.84  316.56   73.84  322.16   73.56  353.48   72.78
  395.98   71.84 1027.15   71.84 1041.47   71.16 1055.95   71.29 1105.99   71.34
 1311.88      70 2321.67      70 2361.29    68.1  2380.2   68.45  2385.2   68.94
 2459.27   69.06 2466.56   69.96 2892.25   69.95 3350.42   71.62 3440.53    71.6
 3468.49   70.35  3471.7   69.97 3473.22   69.94 3728.17   68.66 4117.38    68.1
 4895.43   69.26 5278.64   69.66
Lateral Weir HW RS Station=33049.  ,0
Lateral Weir TW RS Station=,0
LW Div RC= 0 ,False,

Type RM Length L Ch R = 1 ,32327.  ,622.82,600.26,528.79
XS GIS Cut Line= 5
 6410715.5872346  2043613.931172 6410674.3556182  2043963.853698
 6410715.4102991 2044743.8925881 6410879.6290227 2045955.0056514
 6410838.5743418 2047453.5014338
#Sta/Elev= 30
       0   70.38   21.98   65.76   25.61   63.84   35.66   53.84   48.49   51.67
  147.23    33.5  214.25    33.3  233.46    30.7  251.54      30  275.87   37.84
  281.86   43.84   296.1   45.84  313.23   51.26  341.05   57.84 1095.01   57.84
 1118.71   59.84 1182.55   61.84    1349   59.87 1531.27    60.3 1681.65   61.84
 1693.11   63.84 1773.32   65.84  2082.3   65.84 2122.68   67.84  2378.3   69.84
 2878.88   71.66 3428.02   71.84 3486.96   75.84 3593.66   79.84 3854.72   80.41
#Mann= 2 ,-1 , 0
       0    .035       0 1182.55     .06       0
Levee=0,,,-1,1752.85,70.00698,,	380
Bank Sta=48.49,313.23
XS Rating Curve= 0 ,0
Exp/Cntr=0.3,0.1

Type RM Length L Ch R = 1 ,31727.  ,761.92,772,797.79
XS GIS Cut Line= 4
 6410079.4474069 2043606.5299361 6410140.6447663 2044004.9083789
 6410284.5265989 2045466.3726105 6410284.3361731 2047453.5014338
#Sta/Elev= 30
       0   61.91    5.71   59.58   58.62    37.8   70.86    34.8  100.53   32.36
  140.15    32.8  167.32      30   175.1   37.84  203.94   45.84     268   45.06
  304.05   52.73  315.91   55.84  374.66   55.84  399.03   53.84  694.39   53.84
  713.58   55.84  729.16   55.84  736.66   53.84 1003.57   53.84 1032.07   57.84
 1050.96   57.84  1063.1   53.84 1105.93   51.84 1252.33   51.84 1309.18   57.84
 1379.44   59.84 2392.78   67.57 2932.65   69.84 3526.04   77.84 3858.71   79.84
#Mann= 2 ,-1 , 0
       0    .035       0 1379.44     .05       0
Levee=0,,,-1,1564.59,68.7301,,	380
Bank Sta=5.71,304.05
XS Rating Curve= 0 ,0
Exp/Cntr=0.3,0.1

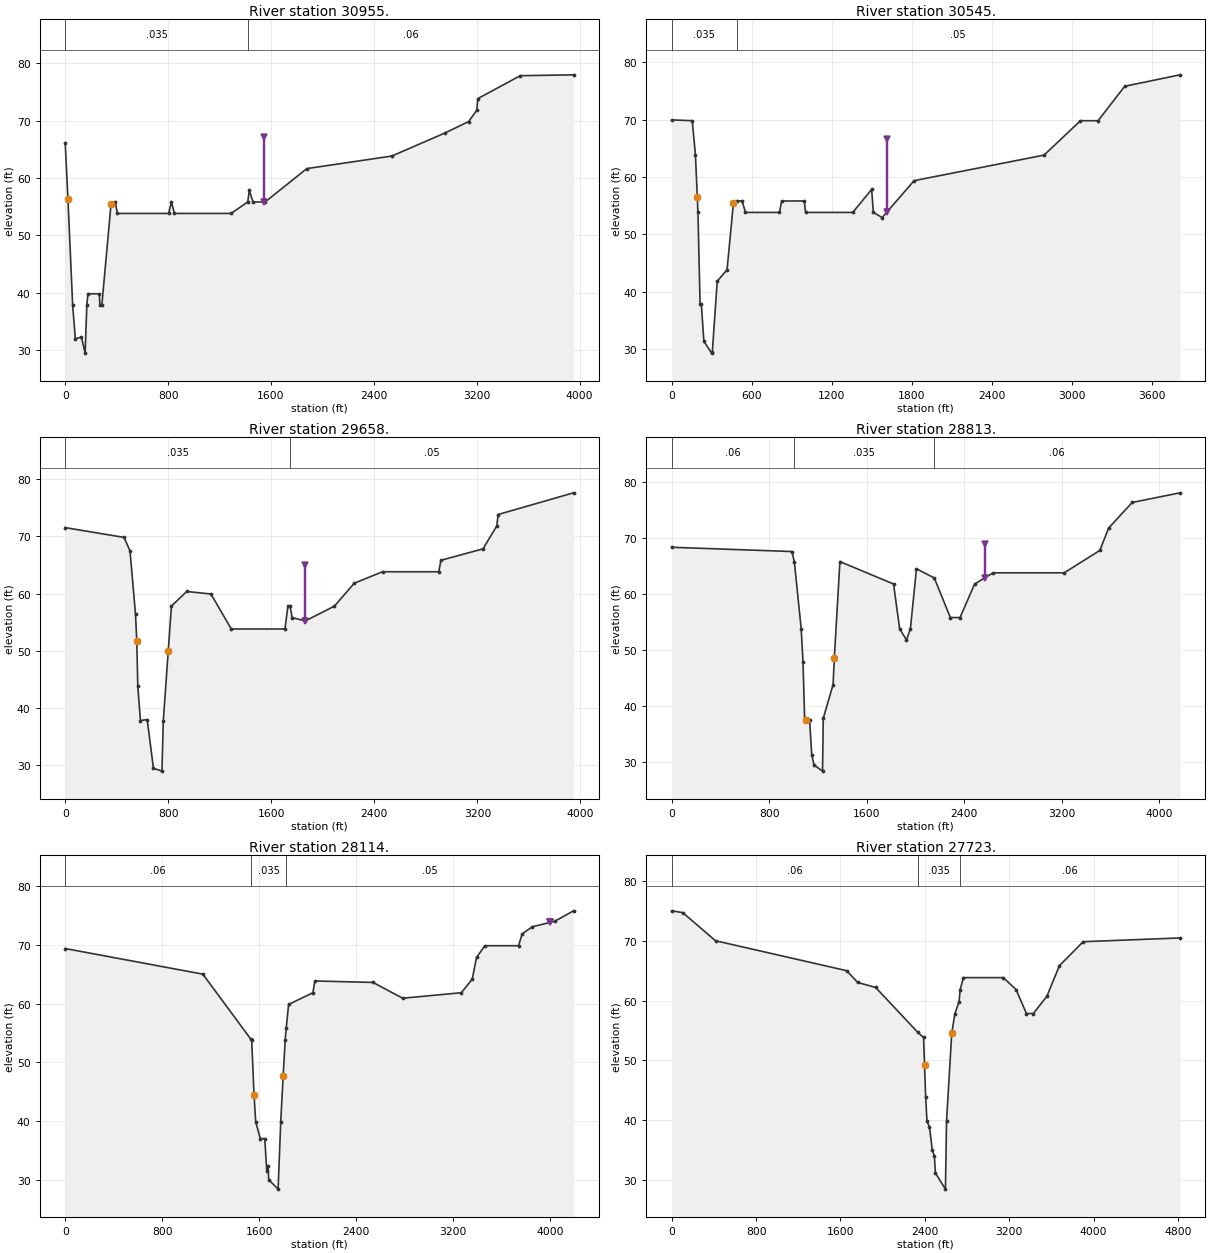
Type RM Length L Ch R = 1 ,30955.  ,434.65,410.31,257.47
XS GIS Cut Line= 4
  6409322.941892 2043613.9722108 6409340.0785594 2044128.0724217
 6409565.8792808  2045236.548759  6409639.359792  2047542.883945
#Sta/Elev= 30
       0   66.13   21.18   56.38   58.08    37.8   78.76      32  126.07    32.3
  154.91    29.5  168.14   37.84  176.39   39.84  265.37   39.84  269.93   37.84
  284.83   37.84   356.1    55.4     389   55.84  405.97   53.84  804.13   53.84
  825.96   55.84   849.2   53.84    1290   53.84 1419.67   55.84 1431.34   57.84
    1461   55.84 1554.73   55.84 1878.57   61.65 2540.43   63.84 2951.43   67.84
 3137.14   69.84 3201.46   71.84 3208.22   73.84 3538.71   77.84 3953.13   77.99
#Mann= 2 ,-1 , 0
       0    .035       0 1419.67     .06       0
Levee=0,,,-1,1546.26,67.12914,,	380
Bank Sta=21.18,356.1
XS Rating Curve= 0 ,0
Exp/Cntr=0.3,0.1

Type RM Length L Ch R = 1 ,30545.  ,902.81,887.34,816.68
XS GIS Cut Line= 5
 6408902.9193746  2043613.931172 6408909.0044335 2043779.1076575
  6409052.695793  2044066.490424 6409360.6058762 2045318.6581209
 6409463.2426022 2047350.8647078
#Sta/Elev= 30
       0   69.98  154.46   69.84  178.25   63.84  192.02   56.49  196.98   53.84
  213.06   37.84  222.41    37.8  241.47   31.36  299.68    29.3  304.49   29.41
   341.4   41.84  415.07   43.84  462.86   55.45  486.59   55.84  527.81   55.84
  553.38   53.84  808.31   53.84  824.76   55.84  994.53   55.84 1003.71   53.84
  1357.1   53.84 1499.17   57.84 1512.08   53.84 1577.72   52.95  1817.5   59.38
  2791.9   63.84 3064.89   69.84 3197.12   69.84 3396.05   75.84 3810.86   77.84
#Mann= 2 ,-1 , 0
       0    .035       0  486.59     .05       0
Levee=0,,,-1,1613.59,66.62889,,	380
Bank Sta=192.02,462.86
XS Rating Curve= 0 ,0
Exp/Cntr=0.3,0.1

Type RM Length L Ch R = 1 ,29658.  ,857.08,844.81,775.99
XS GIS Cut Line= 5
 6408009.7468605 2043692.6432103 6408087.9108625 2044148.5997858
 6408272.6569029  2044456.509869 6408560.0396694 2045113.3847163
 6409032.1684762 2047474.0287506
#Sta/Elev= 30
       0   71.55  456.95   69.84  503.24   67.47  545.73    56.4  555.68   51.78
  563.54   43.84  584.14   37.84  636.55   38.01  684.92    29.5  750.91      29
  761.66   37.84  799.77   49.98  824.81   57.84  943.13   60.39 1131.47   59.95
  1289.3   53.84 1705.87   53.84 1729.09   57.84 1745.78   57.84 1761.82   55.84
 1862.84   55.23 2090.23   57.84 2244.32   61.84 2463.75   63.84 2899.89   63.84
  2916.6   65.84 3243.16   67.84 3350.31   71.84  3360.7   73.84 3946.07   77.63
#Mann= 2 ,-1 , 0
       0    .035       0 1745.78     .05       0
Levee=0,,,-1,1860.77,65.0979,,	380
Bank Sta=555.68,799.77
XS Rating Curve= 0 ,0
Exp/Cntr=0.3,0.1

Type RM Length L Ch R = 1 ,28813.  ,668.58,698.93,673.99
XS GIS Cut Line= 5
 6407039.1905082 2043728.8185786 6407400.1680035 2044669.5066666
 6407658.4019393 2045008.4386926 6407932.7754932 2045508.7669463
 6408578.3603092 2047574.6383858
#Sta/Elev= 30
       0    68.4  986.21   67.64 1006.19   65.79 1062.14   53.84 1077.04   47.91
 1090.21   37.84 1097.92   37.57 1131.31    37.5 1148.43   31.34  1167.2    29.5
 1237.24    28.4 1243.06   37.84 1323.58   43.84 1334.11   48.68 1379.66   65.84
 1819.57   61.84 1869.55   53.84 1925.69   51.84 1957.69   53.84 2007.52   64.56
 2154.01   62.91 2285.24   55.84 2364.68   55.84  2484.5   61.84 2636.54   63.84
 3219.63   63.84 3511.44   67.84 3583.49   71.84 3776.76   76.41 4168.68   78.13
#Mann= 3 ,-1 , 0
       0     .06       0 1006.19    .035       0 2154.01     .06       0
Levee=0,,,-1,2569.44,69.04,,	380
Bank Sta=1097.92,1334.11
XS Rating Curve= 0 ,0
Exp/Cntr=0.3,0.1

Type RM Length L Ch R = 1 ,28114.  ,360.35,390.56,451.68
XS GIS Cut Line= 6
 6406383.6799769 2043692.2465963 6406803.0020416 2044782.4839928
 6406883.7001317 2045137.5556842 6407319.4699133 2045718.5819807
 6407665.1485421 2046418.4992649 6408216.2795937 2047433.7407431
#Sta/Elev= 30
       0   69.36  1135.8      65 1532.22   53.91 1538.58   53.84 1558.21    44.4
 1571.87   39.84 1609.75      37 1646.74      37 1662.86    31.5 1673.88   32.42
 1678.95      30 1756.66    28.4 1778.32   39.84 1798.21   47.61 1815.18   53.84
 1823.77   55.84 1843.18   59.84 2044.01   61.84 2059.64   63.84 2539.62   63.59
 2784.66    60.9  3268.8   61.84 3358.53   64.14 3393.88   67.84 3462.99   69.84
 3740.63   69.84 3770.26   71.84 3853.73   73.06 4039.32      74 4194.32   75.78
#Mann= 3 ,-1 , 0
       0     .06       0 1532.22    .035       0 1823.77     .05       0
Levee=0,,,-1,4002.5,73.93548,,	380
Bank Sta=1558.21,1798.21
XS Rating Curve= 0 ,0
Exp/Cntr=0.3,0.1

Type RM Length L Ch R = 1 ,27723.  ,624.48,685.03,705.83
XS GIS Cut Line= 5
 6405892.9099351 2043073.4349505  6406566.613635 2045308.1594714
 6406730.9316186  2045653.227204 6407263.6861287 2046656.2023339
 6407520.7882071 2047588.1972914
#Sta/Elev= 30
       0      75  104.87    74.7  415.72      70 1659.09      65 1763.01   63.03
 1933.44    62.2 2334.07   54.68 2387.62   53.84 2396.83   49.29 2407.87   43.84
 2420.33   39.84 2444.04   38.88  2469.9   35.07 2490.44      34 2500.08    31.2
 2595.07    28.5 2605.65   39.84 2654.85   54.53 2685.28   57.84 2724.49   59.84
 2734.86   61.84 2764.91   63.84 3143.26   63.84 3265.17   61.84 3362.84   57.84
 3428.83   57.84 3557.37   60.74 3675.82   65.84 3900.81   69.84 4818.76   70.47
#Mann= 3 ,-1 , 0
       0     .06       0 2334.07    .035       0 2734.86     .06       0
Bank Sta=2396.83,2654.85
XS Rating Curve= 0 ,0
Exp/Cntr=0.3,0.1

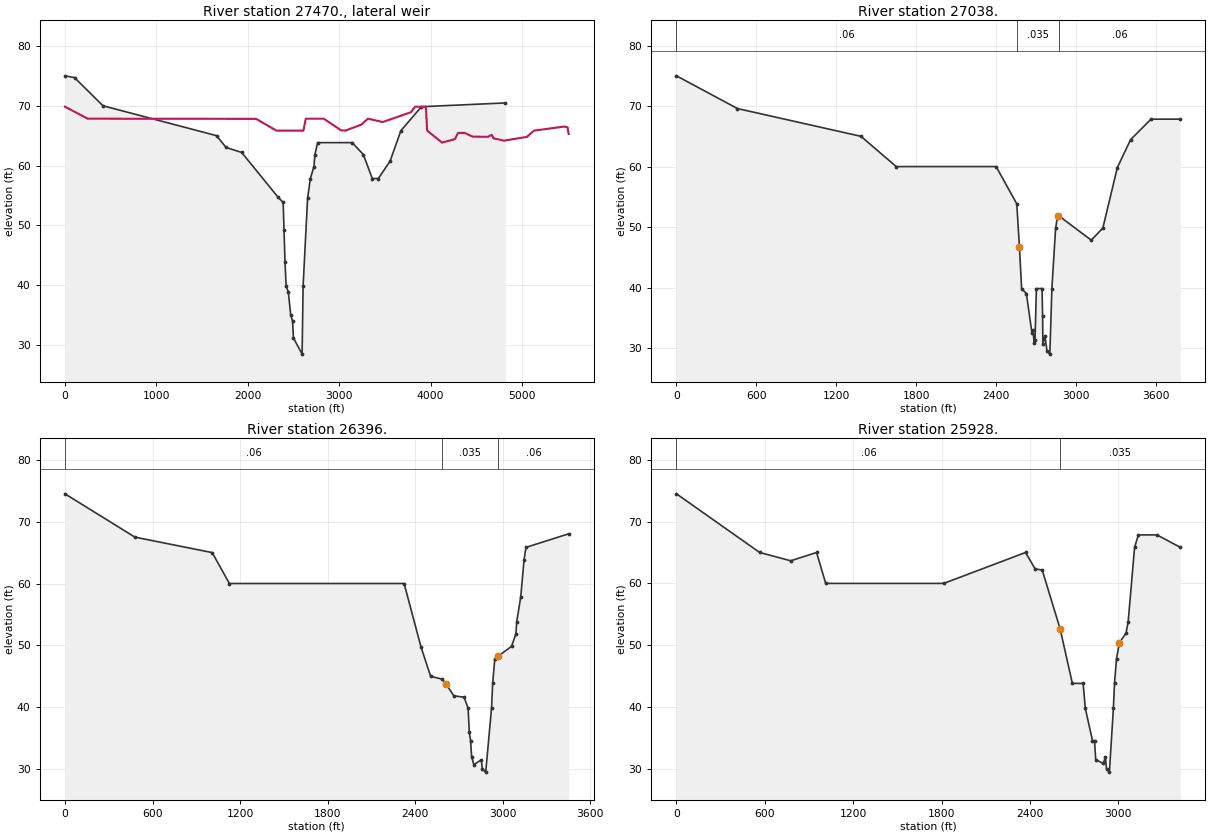
Type RM Length L Ch R = 6 ,27470.  ,,,
Node Name=North LS
Lateral Weir Pos= 3
Lateral Weir End=                ,                ,        ,Northside
Lateral Weir Distance=0
Lateral Weir TW Multiple XS=0
Lateral Weir WD=20
Lateral Weir Coef=2
Lateral Weir WSCriteria=-1
Lateral Weir Flap Gates= 0
Lateral Weir Hagers EQN= 0 ,,,,,
Lateral Weir SS=0.05,0.05,
Lateral Weir Type= 0
Lateral Weir Connection Pos and Dist= 0 ,
Lateral Weir SE= 30
       0   69.84   248.5   67.84 2091.82   67.81 2313.68   65.84 2609.55   65.84
 2635.68   67.84 2831.04   67.84 3021.44   65.89 3066.15   65.84 3242.95   66.84
 3316.39   67.84 3476.85   67.28  3786.3   68.92 3830.66   69.84 3949.75   69.84
 3962.76   65.84 4126.04   63.84 4267.12   64.43 4300.91   65.45 4371.78   65.47
 4461.03   64.84 4626.77   64.81 4670.04   65.14 4689.74   64.55    4804   64.17
  5054.3   64.79 5130.79   65.84 5467.54   66.53 5499.43   66.38 5512.54   65.28
LW Div RC= 0 ,False,

Type RM Length L Ch R = 1 ,27038.  ,481.08,641.78,711.72
XS GIS Cut Line= 5
 6405580.7057804  2043155.593966 6405818.4851523 2044750.2047568
 6405979.8813799 2045637.8838906 6406141.2776076  2046025.234818
 6406243.6811175 2046864.6507802
#Sta/Elev= 30
       0      75  457.66   69.59 1384.39      65 1648.72      60 2398.35      60
 2553.29   53.84 2573.53   46.64 2589.69   39.84 2625.55      39 2666.92   32.53
 2675.15      33 2683.12    30.9 2690.27    31.3 2700.57   39.84 2743.13   39.84
 2746.91   35.24 2749.25   30.66 2764.97      32 2780.18    29.5 2801.52      29
 2816.67   39.84 2844.85   49.84 2859.58   51.84 2869.79   51.84 3112.11   47.84
 3199.21   49.84 3307.93   59.84 3407.34   64.46 3560.66   67.84 3779.74   67.84
#Mann= 3 ,-1 , 0
       0     .06       0 2553.29    .035       0 2869.79     .06       0
Bank Sta=2573.53,2859.58
XS Rating Curve= 0 ,0
Exp/Cntr=0.3,0.1

Type RM Length L Ch R = 1 ,26396.  ,407.87,468.66,469.88
XS GIS Cut Line= 5
 6405501.4660595 2043204.3421721 6405463.4135082 2044685.6462847
 6405447.2738902 2045654.0235086 6405463.4135082  2046331.887608
 6405478.1409552 2046655.8671125
#Sta/Elev= 30
       0    74.5   479.1    67.5 1009.06      65 1126.68      60 2324.36      60
    2440   49.75 2506.02      45 2586.93   44.52 2611.51   43.76 2665.22   41.84
 2735.19   41.62 2762.94   39.84 2771.45   35.91 2779.85    34.6 2787.26      32
 2802.36    30.7 2853.41    31.5 2861.18   29.99 2883.69    29.5 2923.54   39.84
 2931.39   43.84 2945.98   47.84 2969.72   48.26 3060.94   49.84  3090.4   51.84
 3096.23   53.84  3123.8   57.84 3146.39   63.84 3159.68   65.84 3452.68   68.04
#Mann= 3 ,-1 , 0
       0     .06       0 2586.93    .035       0 2969.72     .06       0
Bank Sta=2611.51,2969.72
XS Rating Curve= 0 ,0
Exp/Cntr=0.3,0.1

Type RM Length L Ch R = 1 ,25928.  ,309.94,393.16,426.71
XS GIS Cut Line= 5
    6405366.5758  2043200.801189 6405092.2022461 2045153.6953023
 6404979.2249199 2045750.8612641 6404995.3645379 2046283.4687066
 6404970.1599786 2046590.9640941
#Sta/Elev= 30
       0   74.48     565      65  775.98   63.66   951.6      65 1013.53      60
 1814.98      60 2370.61      65 2435.44   62.36 2483.98   62.15 2605.76   52.63
 2688.69   43.84 2761.89   43.84 2776.31   39.84 2825.38    34.6 2839.11    34.6
  2847.3    31.5 2899.18    30.9 2912.97      32 2920.64      30 2940.12    29.5
 2967.36   39.84 2974.86   43.84 2988.52   47.84 3007.99    50.4 3053.41   51.98
  3067.8   53.84 3111.33   65.84 3137.12   67.84 3263.63   67.84 3421.21   65.84
#Mann= 2 ,-1 , 0
       0     .06       0 2605.76    .035       0
Bank Sta=2605.76,3007.99
XS Rating Curve= 0 ,0
Exp/Cntr=0.3,0.1