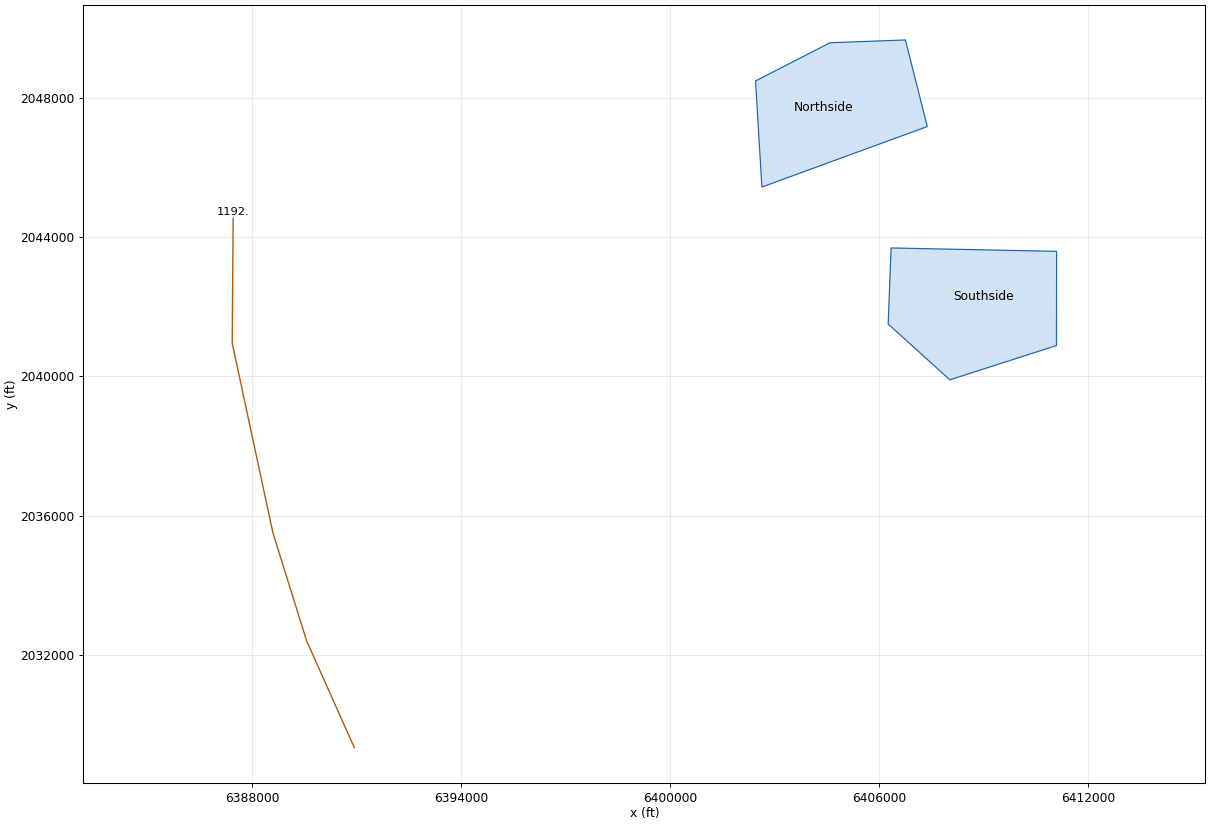
HEC-RAS study Baxter.prj: Baxter River GIS Example

--- Baxter.g02 (geometry) --- (continued)

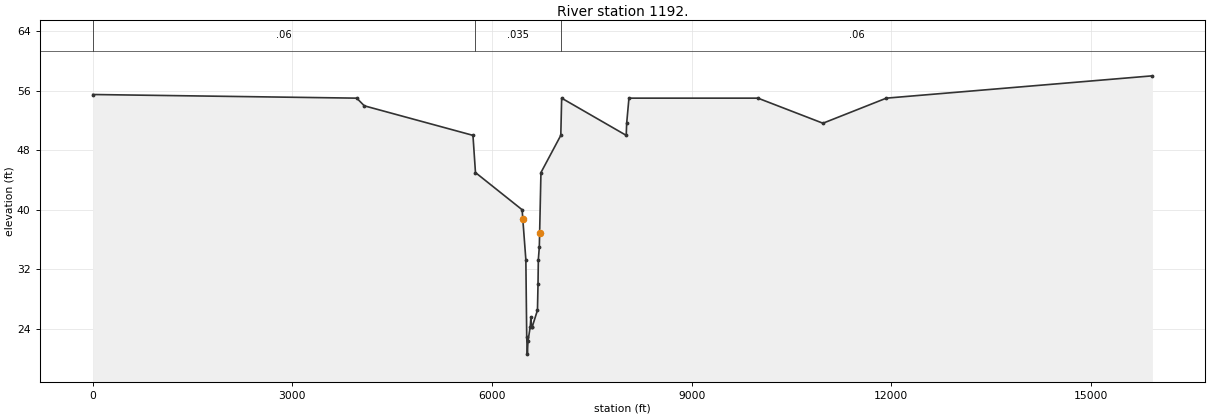
Type RM Length L Ch R = 1 ,1192.   ,2489.97,1192.08,2184.36
XS GIS Cut Line= 5
 6390934.9809811 2029344.4325601 6389565.4266274 2032410.7657738
 6388597.8620858 2035512.6637908 6387431.0931521 2040948.0996752
 6387459.5509021 2044704.5265577
#Sta/Elev= 30
       0   55.49  3966.7      55 4080.32   53.97 5713.05      50 5750.66      45
 6452.26      40 6461.74   38.77 6507.84    33.3 6520.93    22.9 6530.59    20.6
 6539.36    22.3 6573.87    24.3 6583.55    25.6 6593.32    24.2 6604.62    24.3
 6682.31    26.5  6690.5      30  6695.5    33.3 6710.22      35 6714.83   36.85
 6734.74      45 7032.99      50 7045.87      55 8016.13      50 8022.67    51.6
 8057.12      55 9995.32      5510972.02   51.6311924.81      5515923.37      58
#Mann= 3 ,-1 , 0
       0     .06       0 5750.66    .035       0 7032.99     .06       0
Bank Sta=6461.74,6714.83
XS Rating Curve= 0 ,0
Exp/Cntr=0.3,0.1

Storage Area=Northside       ,6404656.4810927,2047345.1453131
Storage Area Surface Line= 6
 6402631.9698137 2045430.5195887
 6402449.2270548 2048475.6202047
 6404586.5230883 2049570.9844248
 6406750.5353489 2049651.1330113
 6407378.3660691 2047166.5263576
 6402631.9698137 2045430.5195887
Storage Area Type= 1
Storage Area Vol Elev= 11
   63.34       0   64.59    6.26   65.84   48.26   67.09  259.54   68.34  514.59
   69.59  804.83   70.84  1129.8   72.09 1487.12   73.34 1858.41   74.59 2234.75
   75.84 2622.24

Storage Area=Southside       ,6408721.1859302,2042034.6452537
Storage Area Surface Line= 6
  6411089.902679 2043584.9518455
 6411085.7799576 2040882.1641541
 6408026.0069917 2039897.6286624
 6406255.6685722 2041498.3538592
 6406340.4752308 2043682.1245858
  6411089.902679 2043584.9518455
Storage Area Type= 1
Storage Area Vol Elev= 11
68.08583       069.21468    6.7370.34351  122.4371.47236  433.41 72.6012  776.84
73.73004 1135.4774.85889 1504.1375.98772 1879.4377.11657 2257.8278.24541 2641.06
79.37425 3031.72

Chan Stop Cuts=-1
Use User Specified Reach Order=0
User Specified Reach Order=Tule Creek      ,Tributary
User Specified Reach Order=Baxter River    ,Lower Reach
User Specified Reach Order=Baxter River    ,Upper Reach
Composite Channel Slope=5

--- Baxter.g01 (geometry) ---

Geom Title=Imported GIS Data
Program Version=3.13

Junct Name=2
Junct Desc=, 0 , 0 ,-1
Up River,Reach=Baxter River    ,Upper Reach
Up River,Reach=Tule Creek      ,Tributary
Dn River,Reach=Baxter River    ,Lower Reach
Junc L&A=514.47,0
Junc L&A=1595.1,0

River Reach=Baxter River    ,Upper Reach

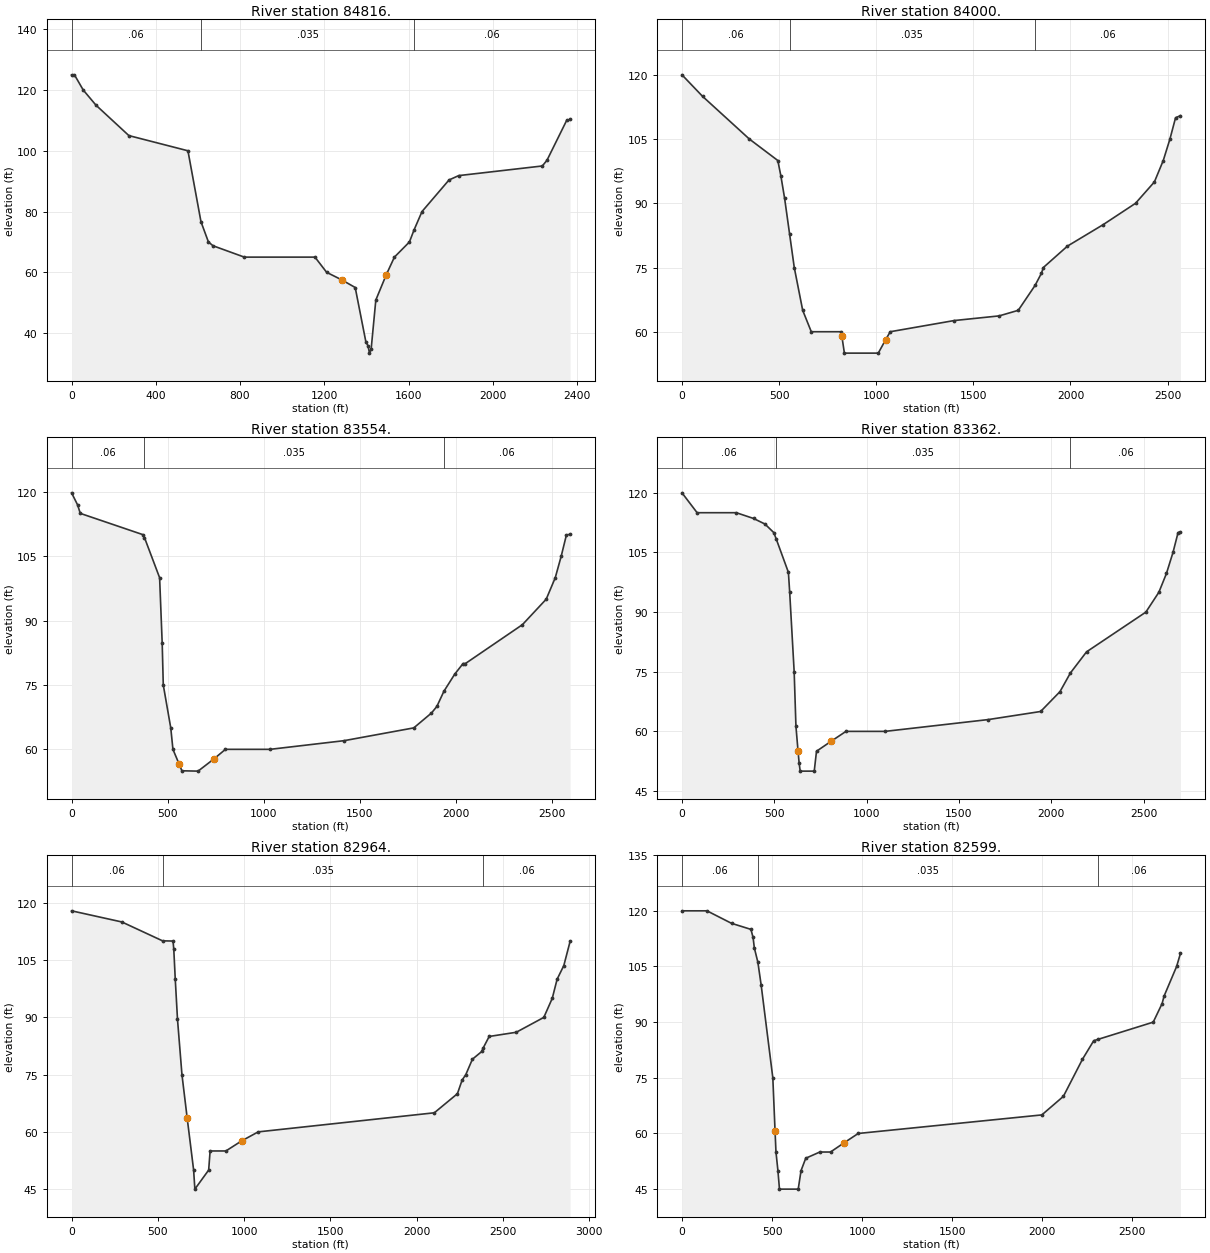
Type RM Length L Ch R = 1 ,84816.  ,343.45,815.24,627.65
XS GIS Cut Line= 3
 6451252.6104362 2049658.4807595  6450473.975481 2050754.3373982
 6449753.0171611 2051480.1020886
#Sta/Elev= 30
       0     125   13.58     125   55.26     120     116     115  272.01     105
  552.51     100  614.42   76.65  649.72      70  671.54   68.74  820.19      65
 1155.78      65 1211.11      60 1282.42   57.53 1346.84      55 1397.53    37.1
  1407.9    35.8 1414.52    33.4 1422.67    34.8 1444.74   50.88 1494.65   59.25
 1533.01      65 1604.47      70 1625.67   73.85 1664.08      80 1792.43    90.4
 1838.32   91.83 2235.35      95 2257.44   96.87 2351.04     110  2367.3  110.31
#Mann= 3 ,-1 , 0
       0     .06       0  614.42    .035       0 1625.67     .06       0
Bank Sta=1282.42,1494.65
Exp/Cntr=0.3,0.1

Type RM Length L Ch R = 1 ,84000.  ,455.68,446.09,151.22
XS GIS Cut Line= 6
 6451085.8127514 2049558.9672916 6450742.6558566 2049935.6028732
 6450550.1532417  2050027.669333 6450206.9963942 2050019.2996849
 6450031.2330754  2050186.693261 6449462.0948789 2051308.2303579
#Sta/Elev= 30
       0  120.02  105.73     115  347.08  105.01  493.38     100  509.52    96.3
  528.35   91.17  554.05   82.81  578.07      75  621.45      65  665.66      60
  819.62      60  823.03   58.98  836.19      55 1010.56      55  1048.5   58.13
 1072.21      60 1401.33   62.61 1633.01    63.7 1731.28      65 1817.88   70.82
 1850.78   73.67 1860.48      75 1984.53      80 2167.85      85 2334.97      90
 2432.27      95 2477.86     100 2512.09     105 2541.24     110 2566.57  110.47
#Mann= 3 ,-1 , 0
       0     .06       0  554.05    .035       0 1817.88     .06       0
Bank Sta=823.03,1048.5
Exp/Cntr=0.3,0.1

Type RM Length L Ch R = 1 ,83554.  ,237.02,192.39,113.07
XS GIS Cut Line= 5
  6450851.461707 2049232.5497401 6450499.9351642 2049567.3369396
 6450257.2144718 2049592.4459784 6450098.1905437  2049734.730563
 6449353.2890285 2051207.7942028
#Sta/Elev= 30
       0  119.79   31.16  116.98   45.27     115  373.71     110  379.25  109.35
  457.95     100  471.39   84.69  477.01      75  515.96      65  527.23      60
  558.46   56.67  573.81      55  658.07   54.92  739.01   57.71  800.42      60
 1032.95      60 1417.84   62.02 1780.26      65 1872.06   68.45 1900.44      70
 1936.99   73.53 1993.11   77.51 2036.74      80 2049.02      80 2345.54   89.06
 2469.33      95 2516.32     100  2547.2     105 2574.57     110 2593.54  110.09
#Mann= 3 ,-1 , 0
       0     .06       0  379.25    .035       0 1936.99     .06       0
Bank Sta=558.46,739.01
Exp/Cntr=0.3,0.1

Type RM Length L Ch R = 1 ,83362.  ,399.14,398.4,400
XS GIS Cut Line= 3
 6450767.7649427 2048939.6109702 6450031.2330754 2049659.4034467
  6449244.483178 2051132.4670865
#Sta/Elev= 30
       0     120   81.88     115  294.26     115  387.53  113.55  449.01  112.16
  497.14     110  511.03  108.31  576.33     100   583.1   95.13  607.54      75
   617.2   61.24  628.61      55  634.29   52.11  640.13      50  716.26      50
  728.51      55  807.44    57.5  888.13      60 1100.11      60 1659.22   62.97
 1942.38      65  2047.3      70 2103.62   74.69 2190.95      80 2512.34      90
 2582.84      95 2623.74   99.71  2659.2     105 2686.72     110 2699.84  110.18
#Mann= 3 ,-1 , 0
       0     .06       0  511.03    .035       0 2103.62     .06       0
Bank Sta=628.61,807.44
Exp/Cntr=0.3,0.1

Type RM Length L Ch R = 1 ,82964.  ,397.22,364.75,139.76
XS GIS Cut Line= 3
 6450474.8261254 2048596.4540753 6449512.3129565 2049701.2518289
 6449026.8715244 2051040.4006267
#Sta/Elev= 30
       0  117.92  291.48     115  527.02  110.06  588.12     110  592.41  107.82
  600.95     100  613.91    89.5  639.73      75  669.93   63.66  707.41      50
  714.56      45  794.65      50  802.97      55  894.51      55  985.77   57.64
 1081.78      60  2102.7      65 2236.43      70 2263.97   73.59 2285.11      75
 2323.45   79.04 2377.87   81.07  2385.3   81.93 2420.67      85 2577.61    86.1
 2737.49      90 2786.39      95 2814.45     100 2853.31  103.58 2889.69   109.9
#Mann= 3 ,-1 , 0
       0     .06       0  527.02    .035       0  2385.3     .06       0
Bank Sta=669.93,985.77
Exp/Cntr=0.3,0.1

Type RM Length L Ch R = 1 ,82599.  ,622.27,679.05,407.5
XS GIS Cut Line= 5
  6450014.493732 2048470.9088815 6449780.1426877 2048780.5870421
 6449713.1852667 2048872.6535492 6449520.6826045 2049332.9859426
 6448867.8475963 2050973.4431584
#Sta/Elev= 30
       0     120  138.53     120  274.98  116.63  382.64     115  394.53  112.82
  401.58     110  421.14  106.15  439.41     100  504.14      75  516.55   60.62
   521.6      55  532.42      50  541.03      45  645.11      45  660.83      50
  686.82   53.32  764.93      55  824.34      55  901.95   57.56  978.12      60
 1997.17      65 2116.78      70 2222.72      80 2285.19      85 2307.05   85.33
 2615.41      90 2664.64      95 2675.77   97.04  2745.2     105 2766.74  108.55
#Mann= 3 ,-1 , 0
       0     .06       0  421.14    .035       0 2307.05     .06       0
Bank Sta=516.55,901.95
Exp/Cntr=0.3,0.1

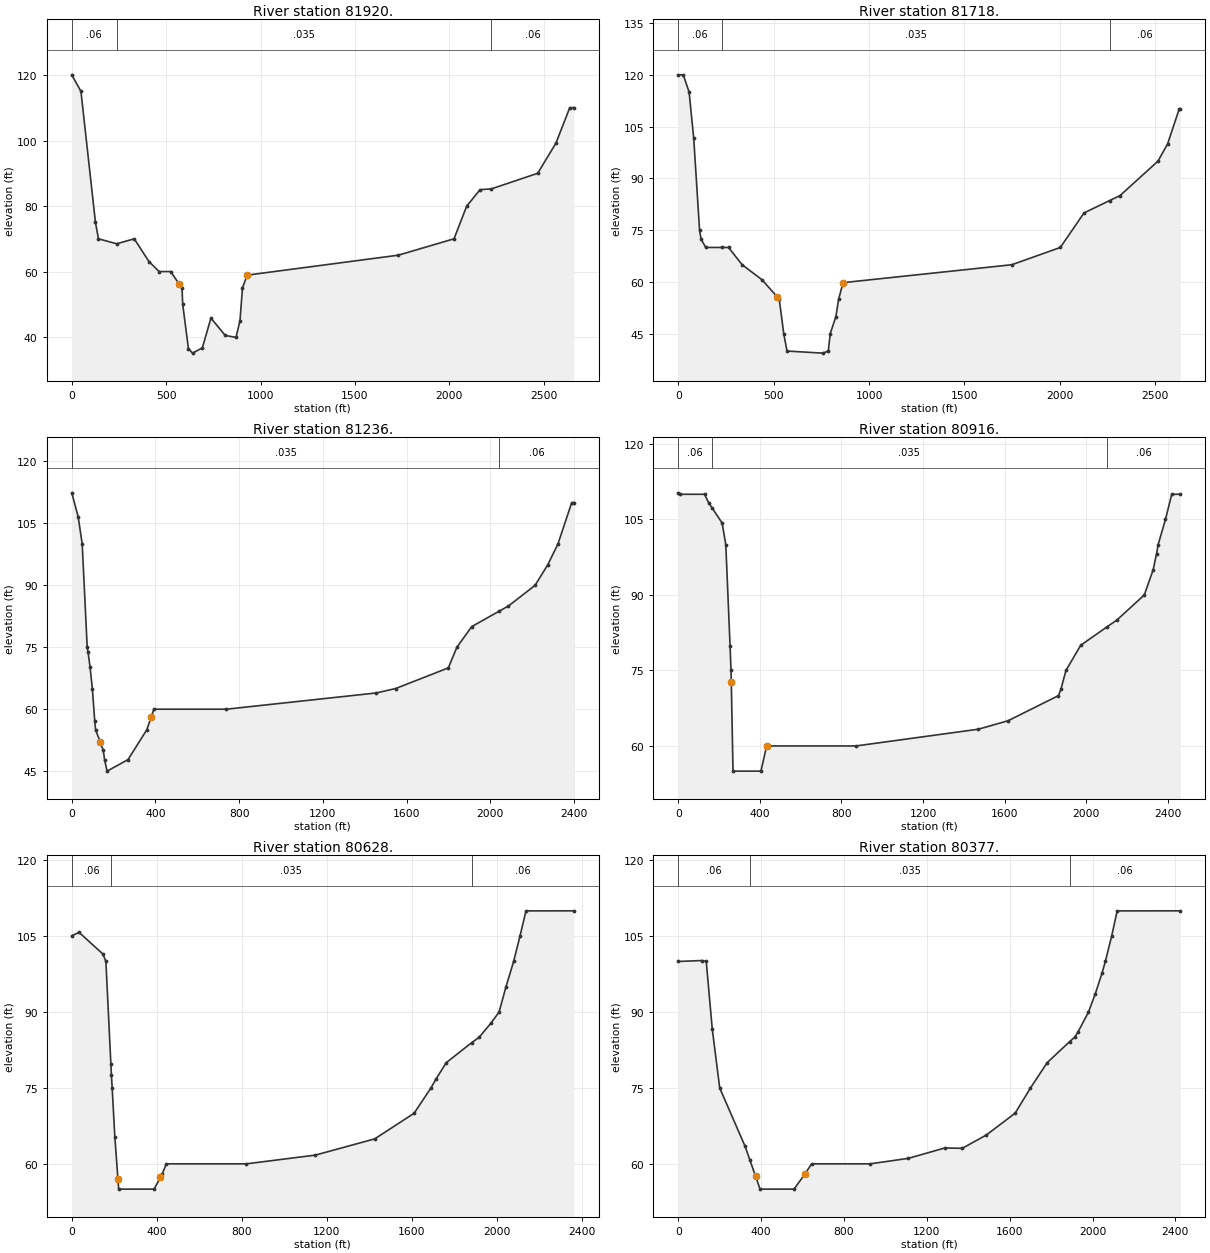
Type RM Length L Ch R = 1 ,81920.  ,111.46,201.87,246.87
XS GIS Cut Line= 4
 6449199.0808431 2048337.9254362 6449132.9930003 2048860.6202276
 6449018.8412631 2049209.0833903 6448664.3700545 2050939.3833486
#Sta/Elev= 30
       0  120.06   48.63     115  125.47      75   141.4      70  238.11   68.48
  330.88      70  409.28   63.04  463.08      60  524.31      60  569.99   56.09
  583.97      55  587.72      50  618.05    36.5  639.65    35.1  691.62    36.7
  737.27    45.8  812.88    40.5  870.18    39.9  891.07      45  904.39      55
  928.89   58.91 1729.83      65 2024.92      70 2092.42      80  2163.1      85
 2222.53   85.24 2468.37      90 2565.24   99.24 2637.94     110 2659.78  110.07
#Mann= 3 ,-1 , 0
       0     .06       0  238.11    .035       0 2222.53     .06       0
Bank Sta=569.99,928.89
Exp/Cntr=0.3,0.1

Type RM Length L Ch R = 1 ,81718.  ,541.42,481.91,140.1
XS GIS Cut Line= 5
 6449093.8289453 2048320.2546488 6449035.2411724 2048755.4780034
 6448867.8475963 2049023.3077819  6448725.563059 2049383.2040201
 6448457.7332805 2050847.8979646
#Sta/Elev= 30
       0     120   26.46     120   56.93     115   81.01  101.74   111.8      75
  119.89   72.39  144.32      70   228.9      70  263.46      70  335.06      65
  439.15   60.64  518.74   55.69  529.43      55  552.95      45  570.02      40
  757.67    39.4  786.41      40  796.25      45  826.34      50  840.37      55
  863.79   59.81 1747.77      65 2002.27      70 2126.29      80 2259.93   83.57
 2314.41      85 2513.95      95 2564.42     100 2624.52     110 2630.97  110.02
#Mann= 3 ,-1 , 0
       0     .06       0   228.9    .035       0 2259.93     .06       0
Bank Sta=518.74,863.79
Exp/Cntr=0.3,0.1

Type RM Length L Ch R = 1 ,81236.  ,440.39,320.31,102.46
XS GIS Cut Line= 5
 6448507.9513581  2048454.169538 6448533.0603969 2048579.7147319
 6448466.1029759 2048830.8051197 6448558.1694356 2049433.4220977
 6448374.0364688 2050822.7889258
#Sta/Elev= 30
       0   112.4   30.82  106.55   49.91     100   73.73      75   77.76   73.88
    87.2   70.23   98.31      65  109.88   57.08  113.92      55  135.91   52.08
  150.43      50  157.35   47.62  168.72      45  268.63   47.78  358.38      55
  378.83      58  392.19      60  738.89      60 1454.62   63.93  1547.2      65
 1799.24      70 1840.13      75 1911.06      80 2043.25   83.77 2086.67      85
 2213.84      90 2274.71      95  2322.9     100 2388.64     110 2399.02  110.04
#Mann= 2 ,-1 , 0
       0    .035       0 2043.25     .06       0
Bank Sta=135.91,378.83
Exp/Cntr=0.3,0.1

Type RM Length L Ch R = 1 ,80916.  ,268.79,287.24,282.69
XS GIS Cut Line= 4
 6448005.7705825 2048479.2785768 6448357.2971254 2049040.0471253
 6448457.7332805 2049458.5311365 6448265.2306657 2050814.4192304
#Sta/Elev= 30
       0  110.29    8.47     110  129.04     110  149.46  108.28  164.82  107.37
  215.07  104.31  233.22     100   254.2    79.8   258.8      75  260.09   72.68
  268.63      55  405.54      55  433.32      60  437.01      60  871.29      60
 1471.76   63.33 1616.64      65  1864.3      70 1876.33   71.27 1900.96      75
 1973.22      80 2100.85   83.62 2150.22      85 2285.17      90 2328.56      95
 2344.98   98.14 2352.99     100 2388.83     105 2419.68     110 2461.69  110.01
#Mann= 3 ,-1 , 0
       0     .06       0  164.82    .035       0 2100.85     .06       0
Bank Sta=260.09,437.01
Exp/Cntr=0.3,0.1

Type RM Length L Ch R = 1 ,80628.  ,325.53,251.41,128.32
XS GIS Cut Line= 4
 6447846.7466545 2048638.3025049 6447905.3344274 2048855.9141585
 6448189.9035494 2049324.6162472 6448039.2493167 2050906.4857375
#Sta/Elev= 30
       0  105.08   34.41  105.75  146.67  101.46  160.56     100  184.02   79.75
  186.53   77.58  190.12      75  202.62   65.37  217.24   56.98   220.7      55
   387.4      55  417.29   57.33  425.24   57.95  444.96      60  821.95      60
  1145.8   61.72  1425.5   64.93    1611      70 1690.33      75 1712.83   76.68
 1762.35      80 1882.66   83.98  1916.9      85 1974.02   87.89 2010.84      90
 2043.37      95 2079.35     100 2109.24     105 2137.45     110 2362.71  110.01
#Mann= 3 ,-1 , 0
       0     .06       0  184.02    .035       0 1882.66     .06       0
Bank Sta=217.24,417.29
Exp/Cntr=0.3,0.1

Type RM Length L Ch R = 1 ,80377.  ,516.77,799.69,219.65
XS GIS Cut Line= 5
  6447511.959455   2048738.73866 6447645.8743443 2049031.6774299
 6447913.7040755 2049199.0710533 6448064.3583555 2049550.5975962
 6447938.8131616 2050948.3341197
#Sta/Elev= 30
       0     100  114.55  100.19  135.22     100  164.27   86.65   200.2      75
   322.8   63.45  346.07   60.73  373.35   57.54  395.05      55  559.03      55
  611.93      58   643.9      60     927      60 1110.39   61.08  1286.4   63.13
 1371.31   63.07 1487.32    65.7  1626.2      70 1700.51      75 1781.03      80
 1889.74   84.17 1913.08      85 1929.27   86.02 1980.52      90 2013.71   93.66
 2045.56   97.66 2061.88     100 2092.26     105 2118.93     110 2423.75  110.01
#Mann= 3 ,-1 , 0
       0     .06       0  346.07    .035       0 1889.74     .06       0
Bank Sta=373.35,611.93
Exp/Cntr=0.3,0.1

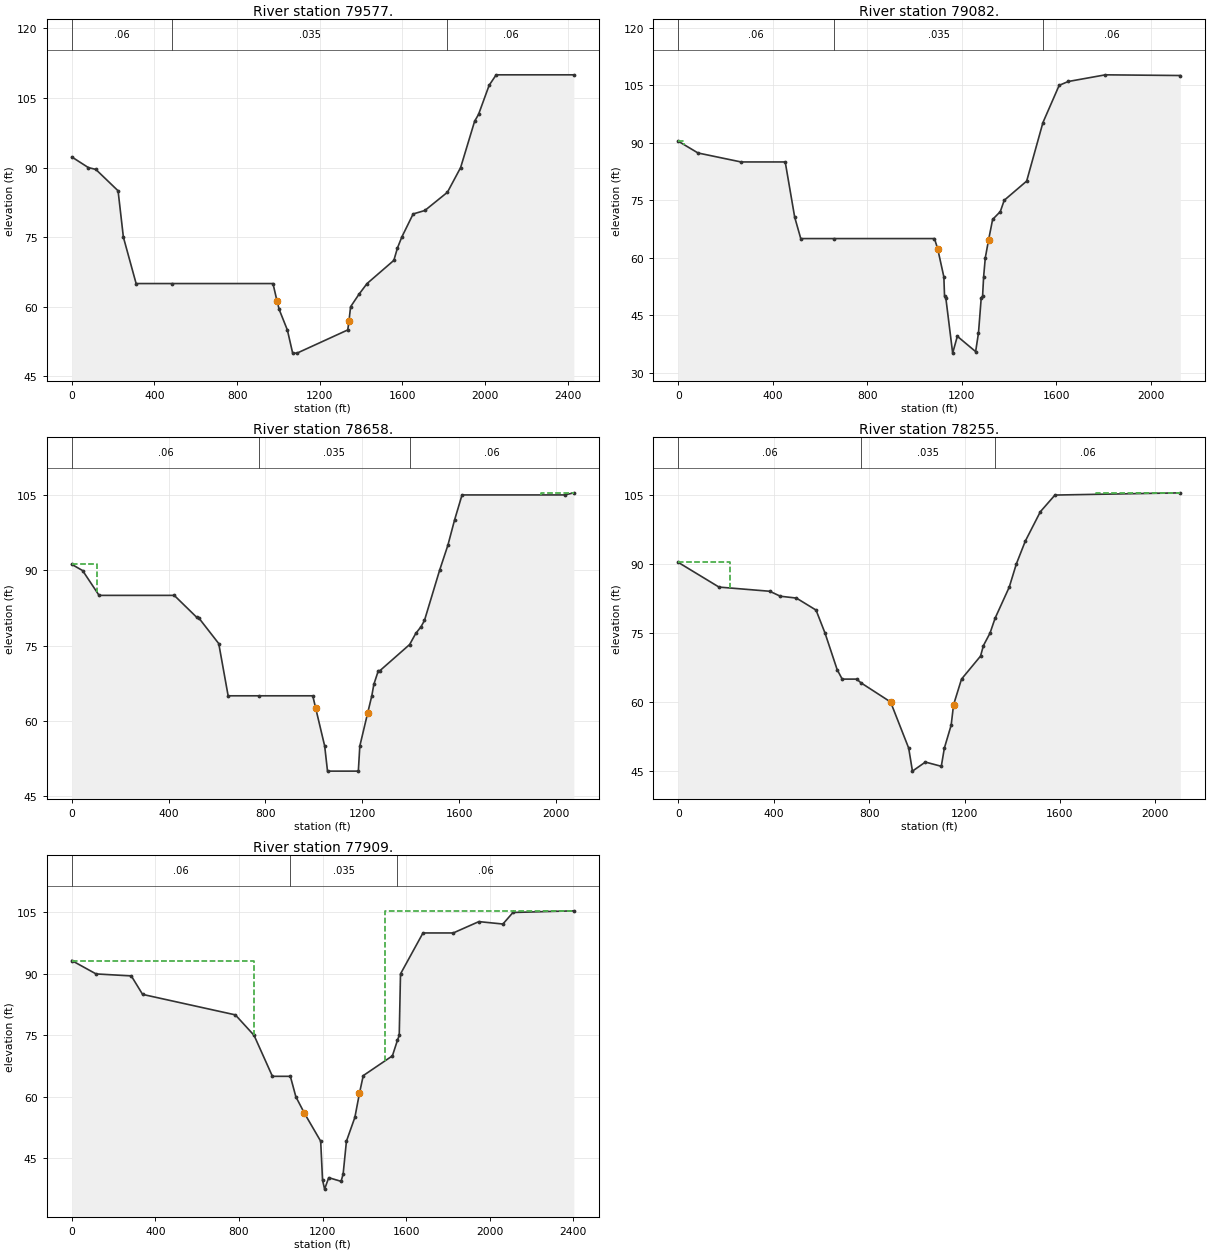
Type RM Length L Ch R = 1 ,79577.  ,278.49,494.98,712.96
XS GIS Cut Line= 4
 6447101.8451392 2048881.0231973 6447461.7413775 2049776.5789452
 6447863.4859979 2050010.9299896 6447779.7892335 2051006.9218926
#Sta/Elev= 30
       0    92.3   80.32      90  116.36   89.61  224.09      85  249.79      75
  311.41      65  484.96      65  973.72      65  992.95   61.31 1003.71   59.42
 1043.49   54.97 1068.99      50 1090.19      50 1335.59      55 1341.32   56.85
  1349.4      60 1389.59   62.67 1428.98      65 1558.74      70 1575.98   72.65
 1596.95      75 1651.93      80 1708.71   80.75 1817.95   84.68 1881.78      90
 1949.64     100 1968.45  101.46 2019.82  107.74 2053.84     110 2429.77     110
#Mann= 3 ,-1 , 0
       0     .06       0  484.96    .035       0 1817.95     .06       0
Bank Sta=992.95,1341.32
Exp/Cntr=0.3,0.1

Type RM Length L Ch R = 1 ,79082.  ,294.13,424.18,452.06
XS GIS Cut Line= 3
 6446836.2047607 2048847.3157912 6447219.0206851 2049818.4273274
 6447076.7361005 2050889.7463467
#Sta/Elev= 30
       0   90.42    83.7   87.34  265.65      85   452.7      85  492.79   70.59
  518.45      65  658.96      65 1084.34      65 1098.19   62.25    1124      55
 1126.88      50 1132.35    49.5 1161.25    35.1    1181    39.5 1258.46    35.5
 1270.54   40.37 1282.19   49.57 1287.89      50 1292.24      55 1299.38      60
 1313.51   64.73 1330.37      70 1362.85   72.04 1379.47      75 1474.37      80
 1543.29   95.29 1611.99     105 1650.42     106 1807.43  107.74 2124.57  107.56
#Mann= 3 ,-1 , 0
       0     .06       0  658.96    .035       0 1543.29     .06       0
#XS Ineff= 1 ,-1
       0   23.6290.41933
Permanent Ineff=
       F
Bank Sta=1098.19,1313.51
Exp/Cntr=0.3,0.1

Type RM Length L Ch R = 1 ,78658.  ,320.74,403.16,436.63
XS GIS Cut Line= 5
 6446671.2085714 2048795.2117264 6446817.2760647 2049492.0098233
 6446825.6457127 2049768.2092498  6446733.579253 2050052.7783717
 6446574.5553249 2050822.7889258
#Sta/Elev= 30
       0   91.18    44.9   89.93  112.79      85  423.17      85  516.52   80.61
  526.33    80.4  607.02    75.4  645.84      65   774.2      65  995.29      65
 1007.46   62.53 1044.53      55 1056.22      50 1183.56      50 1189.66      55
 1221.87   61.53 1239.19      65 1247.62   67.28 1266.11      70 1272.52      70
 1395.38   75.21 1420.73   77.42 1442.52   78.76 1456.64      80  1519.2      90
 1553.49      95 1580.94     100  1611.8     105 2035.27     105 2073.62  105.42
#Mann= 3 ,-1 , 0
       0     .06       0   774.2    .035       0 1395.38     .06       0
#XS Ineff= 2 ,-1
       0  102.5791.18344 1937.05 2073.62105.4164
Permanent Ineff=
       F       F
Bank Sta=1007.46,1221.87
Exp/Cntr=0.3,0.1

Type RM Length L Ch R = 1 ,78255.  ,371.53,345.87,293.02
XS GIS Cut Line= 6
 6446540.9484569 2048717.0556293 6446541.0765908 2049299.5072084
 6446474.1191698 2049634.2944079 6446356.9436713 2049835.1667181
  6446223.028782 2050153.2145268 6446080.7441974 2050739.0921141
#Sta/Elev= 30
       0   90.37  170.83      85  383.49   84.09  428.19   83.01  495.25   82.61
  577.63      80  615.27      75  666.07   67.06  687.19      65  748.15      65
  765.38   64.21  890.03   60.03  965.94      50  981.69      45 1035.82   46.97
 1102.62   46.05 1115.43      50 1144.02      55 1154.02   59.42 1187.34      65
 1267.06      70 1279.22   72.29 1306.82      75 1328.17   78.24 1387.46      85
 1416.97      90  1454.8      95 1517.79  101.38 1578.91     105 2104.42  105.48
#Mann= 3 ,-1 , 0
       0     .06       0  765.38    .035       0 1328.17     .06       0
#XS Ineff= 2 ,-1
       0  217.28 90.3664 1749.17 2104.42105.4847
Permanent Ineff=
       F       F
Bank Sta=890.03,1154.02
Exp/Cntr=0.3,0.1

Type RM Length L Ch R = 1 ,77909.  ,223.16,229.2,233.35
XS GIS Cut Line= 6
 6446531.4068593 2048445.6703834 6446341.9149889 2048655.0393395
 6446207.5434658 2049102.9444007 6446140.3577043 2049409.0128963
 6446028.3814508 2049909.1735866  6445838.023505 2050713.9830753
#Sta/Elev= 30
       0   93.27   116.2      90  284.95   89.51  339.02      85  782.96      80
  872.49      75   960.3      65 1046.17      65 1072.56      60 1113.82   55.96
 1191.33   49.16  1200.2   39.66 1210.06   37.46 1229.77   40.26 1288.92   39.36
 1298.77   41.16 1314.55   49.16 1355.03      55 1376.69   60.82 1395.01   65.17
 1534.57      70 1558.66    73.8 1567.25      75 1573.32      90 1680.99     100
 1825.76     100  1948.4  102.77  2063.4  102.18 2111.57     105 2402.93   105.4
#Mann= 3 ,-1 , 0
       0     .06       0 1046.17    .035       0 1558.66     .06       0
#XS Ineff= 2 ,-1
       0  872.4593.26781 1498.38 2402.93105.4026
Permanent Ineff=
       F       F
Bank Sta=1113.82,1376.69
Exp/Cntr=0.3,0.1