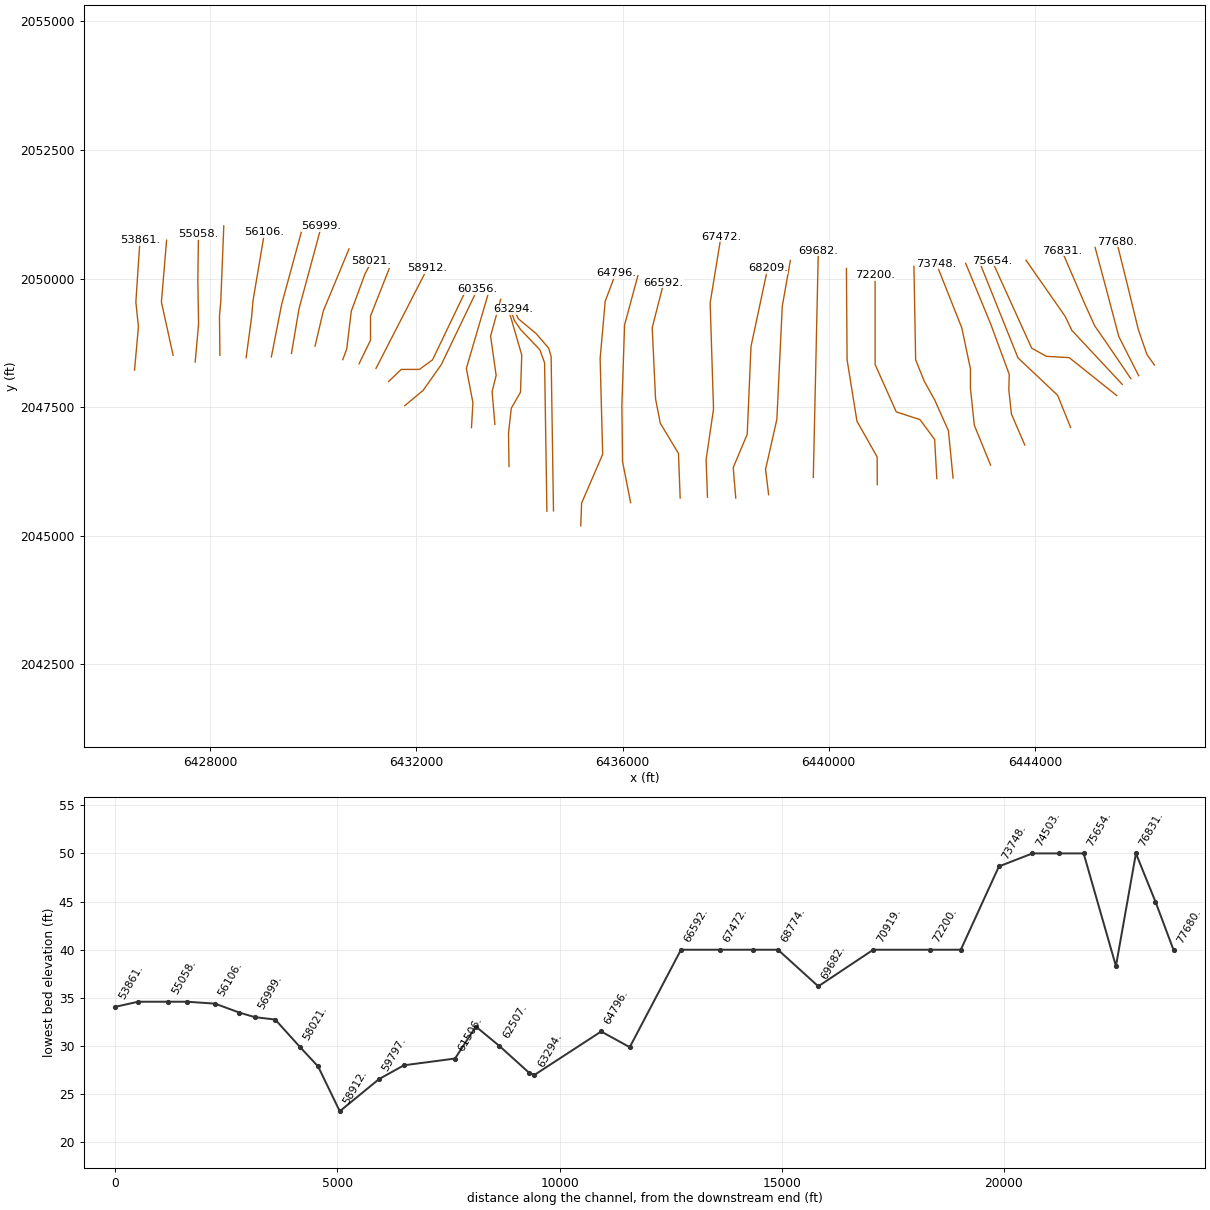
HEC-RAS study Baxter.prj: Baxter River GIS Example

--- Baxter.g01 (geometry) --- (continued)

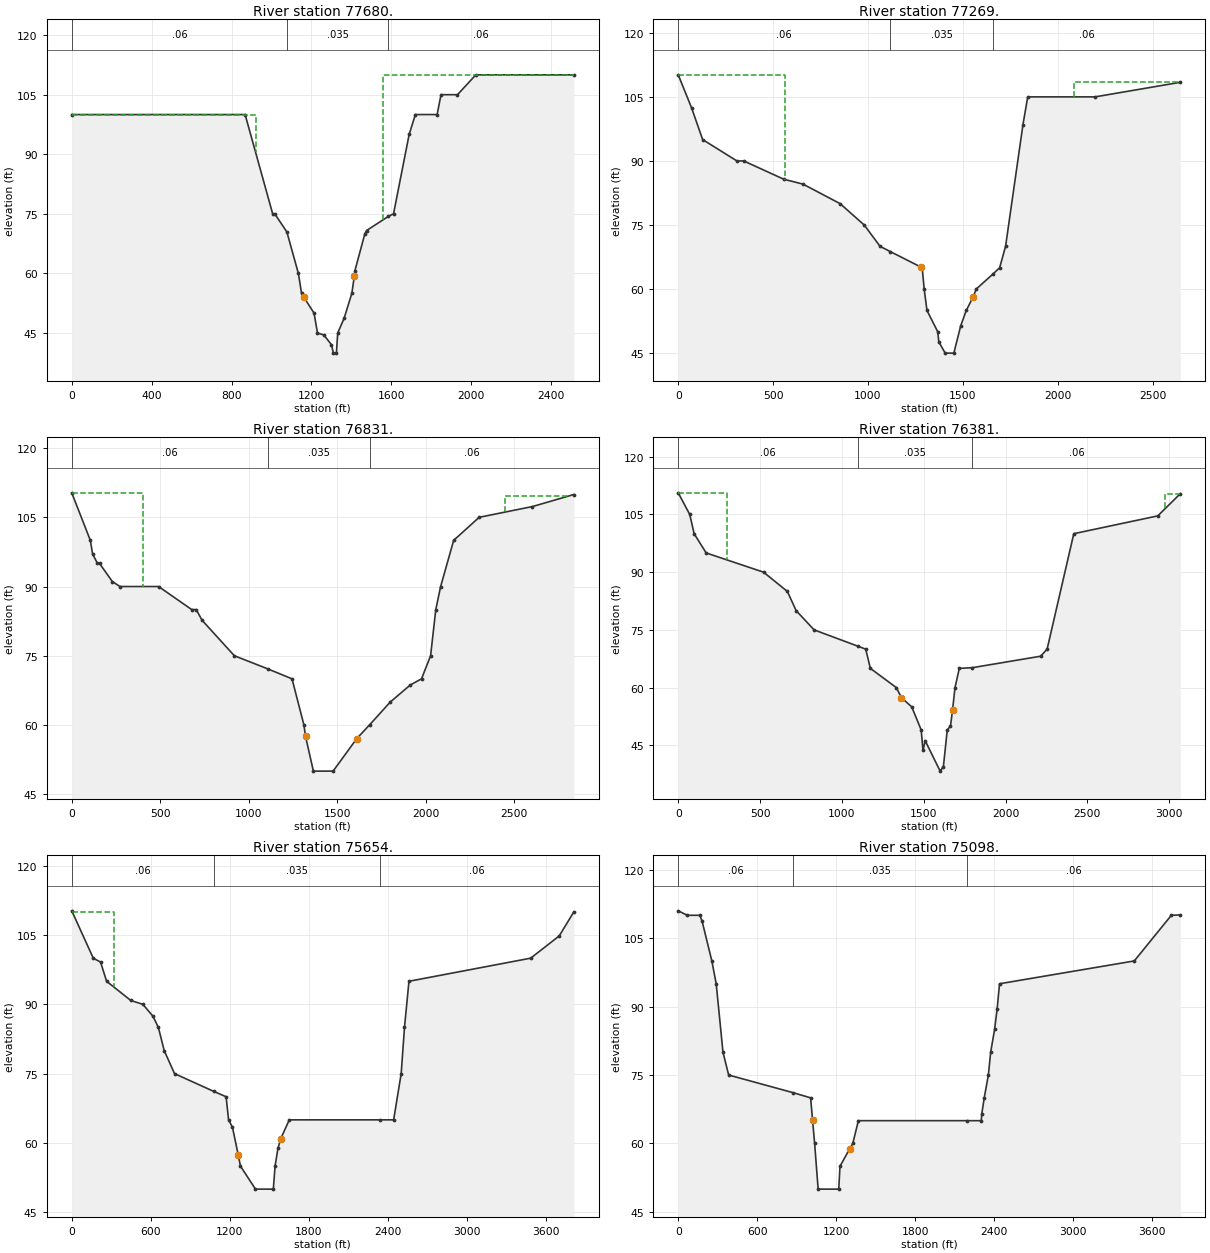
Type RM Length L Ch R = 1 ,77680.  ,408.31,410.92,414.55
XS GIS Cut Line= 5
 6446319.8612835 2048318.7430758 6446173.8418345 2048523.3930405
 6446005.9861812 2049013.3634169 6445796.9638067 2049871.8481846
 6445587.3130695 2050715.9878716
#Sta/Elev= 30
       0     100  867.88     100 1005.91      75 1016.29      75 1076.95   70.45
 1134.55      60 1150.43      55 1161.22   54.07 1213.08      50 1230.27      45
 1262.02   44.51 1300.26   42.05 1309.84   39.94 1324.93      40 1331.52      45
 1363.94   48.76 1402.25      55 1414.54   59.25 1417.52   60.68 1467.46      70
 1476.16   70.81 1585.57   74.38 1610.91      75 1689.22      95 1720.29     100
 1829.22     100 1848.79     105 1931.11     105  2023.1     110 2513.74     110
#Mann= 3 ,-1 , 0
       0     .06       0 1076.95    .035       0 1585.57     .06       0
#XS Ineff= 2 ,-1
 1560.05 2513.74     110       0  920.62     100
Permanent Ineff=
       F       F
Bank Sta=1161.22,1414.54
Exp/Cntr=0.3,0.1

Type RM Length L Ch R = 1 ,77269.  ,369.89,438.25,476.48
XS GIS Cut Line= 4
 6446013.7867765 2048111.0126432 6445628.7814994 2048872.6535492
  6445386.060807 2049793.3182886 6445168.4491061 2050605.1772722
#Sta/Elev= 30
       0  110.16   70.28  102.43  128.63      95  309.24      90   345.1      90
  556.11   85.72  657.66   84.57  853.12      80  980.13      75 1063.76      70
 1117.42   68.78 1281.96   65.08 1285.71      65 1296.19      60 1310.84      55
 1367.65      50 1373.26   47.64 1406.93      45 1452.49      45 1488.87   51.42
 1518.02      55 1554.06   58.16 1570.52      60  1661.1   63.62 1693.99      65
 1725.11      70 1816.77   98.49 1841.94     105 2196.92     105 2646.06  108.41
#Mann= 3 ,-1 , 0
       0     .06       0 1117.42    .035       0  1661.1     .06       0
#XS Ineff= 2 ,-1
 2087.16 2646.06108.4084       0   562.3110.1608
Permanent Ineff=
       F       F
Bank Sta=1281.96,1554.06
Exp/Cntr=0.3,0.1

Type RM Length L Ch R = 1 ,76831.  ,368.31,450.26,475.75
XS GIS Cut Line= 5
 6445863.1325438 2048052.4249176 6445402.8001504 2048730.3689646
  6445160.079458 2049081.8955075 6444967.5767959  2049508.749214
 6444523.9837459 2050538.2198039
#Sta/Elev= 30
       0   110.3  104.89     100  117.81   97.03  145.26      95   156.9      95
   229.7   91.05  272.69      90  490.42      90   677.7      85  702.71      85
  736.24   82.68  918.41      75 1108.13   72.14 1244.02      70 1311.25      60
 1320.31   57.52 1364.81      50 1476.01      50 1609.42   57.03  1683.7   60.09
 1799.68      65 1912.33   68.67 1975.43      70 2026.73      75 2056.09      85
 2083.41      90 2157.02     100 2301.11     105  2602.1  107.33 2835.87  109.94
#Mann= 3 ,-1 , 0
       0     .06       0 1108.13    .035       0  1683.7     .06       0
#XS Ineff= 2 ,-1
 2444.83 2805.08109.5799       0   401.2110.3032
Permanent Ineff=
       F       F
Bank Sta=1320.31,1609.42
Exp/Cntr=0.3,0.1

Type RM Length L Ch R = 1 ,76381.  ,406.22,726.54,924.94
XS GIS Cut Line= 5
 6445696.4249835 2047941.3983319 6444717.1232435 2048992.7959133
 6444590.9555565 2049257.1472846 6444542.8916622 2049329.2431261
 6443827.9413409  2050356.608713
#Sta/Elev= 30
       0  110.62   70.32     105   97.15     100  170.71      95   521.4      90
  666.67      85  720.62      80  830.46      75  1095.7    70.8  1145.6      70
 1174.11      65 1333.04      60 1363.52    57.4 1426.81      55 1484.67      49
 1495.53    43.7 1509.22    46.2 1600.39    38.3 1620.35    39.5 1643.98      49
 1663.59      50 1676.12   54.15 1691.28      60  1717.5      65 1797.02   65.18
  2214.4   68.16 2254.17      70 2417.06     100 2930.34  104.63 3068.04   110.4
#Mann= 3 ,-1 , 0
       0     .06       0  1095.7    .035       0 1797.02     .06       0
#XS Ineff= 2 ,-1
 2976.63 3068.04110.4028       0  300.03110.6171
Permanent Ineff=
       F       F
Bank Sta=1363.52,1676.12
Exp/Cntr=0.3,0.1

Type RM Length L Ch R = 1 ,75654.  ,702.34,556.08,316.91
XS GIS Cut Line= 5
 6445586.9331172 2047726.0074135 6444666.2683305 2048462.5392334
 6444222.6752806 2048487.6482722 6443938.1061587 2048646.6721529
  6443168.095652  2050345.717189
#Sta/Elev= 30
       0  110.25  163.41     100  218.79   99.15  264.58      95  448.24   90.85
  540.65      90  617.45   87.41  658.12      85  702.24      80  780.86      75
 1077.93   71.17 1172.71      70 1191.44      65 1220.93    63.4 1264.11   57.49
 1281.32      55 1395.81      50 1531.39      50 1544.69      55 1566.41    58.8
 1586.98   60.88 1652.69      65 2345.48      65 2445.57      65 2502.81      75
 2527.91      85 2562.02      95 3486.77     100  3704.1  104.83 3814.71  110.03
#Mann= 3 ,-1 , 0
       0     .06       0 1077.93    .035       0 2345.48     .06       0
#XS Ineff= 1 ,-1
    5.47  318.78 110.015
Permanent Ineff=
       F
Bank Sta=1264.11,1586.98
Exp/Cntr=0.3,0.1

Type RM Length L Ch R = 1 ,75098.  ,801.59,595.15,292.73
XS GIS Cut Line= 4
 6444693.0913437 2047106.2882748 6444440.7559223 2047731.1188535
 6443671.7337081 2048458.0851247 6442896.7034953 2050392.6566574
#Sta/Elev= 30
       0  110.98   69.08     110  163.78     110  181.12  108.75  255.36     100
  288.61      95  340.07      80  383.23      75  871.16   71.15 1006.11      70
 1020.87   65.16 1036.75      60 1063.44      50 1220.02      50 1229.41      55
 1303.79   58.88 1326.67      60 1369.29      65 2195.15      65 2303.14      65
 2307.06   66.48 2325.85      70 2357.21      75 2374.71      80 2404.58      85
 2424.08   89.53 2442.06      95  3466.2     100 3747.95     110 3816.14  110.09
#Mann= 3 ,-1 , 0
       0     .06       0  871.16    .035       0 2195.15     .06       0
Bank Sta=1020.87,1303.79
Exp/Cntr=0.3,0.1

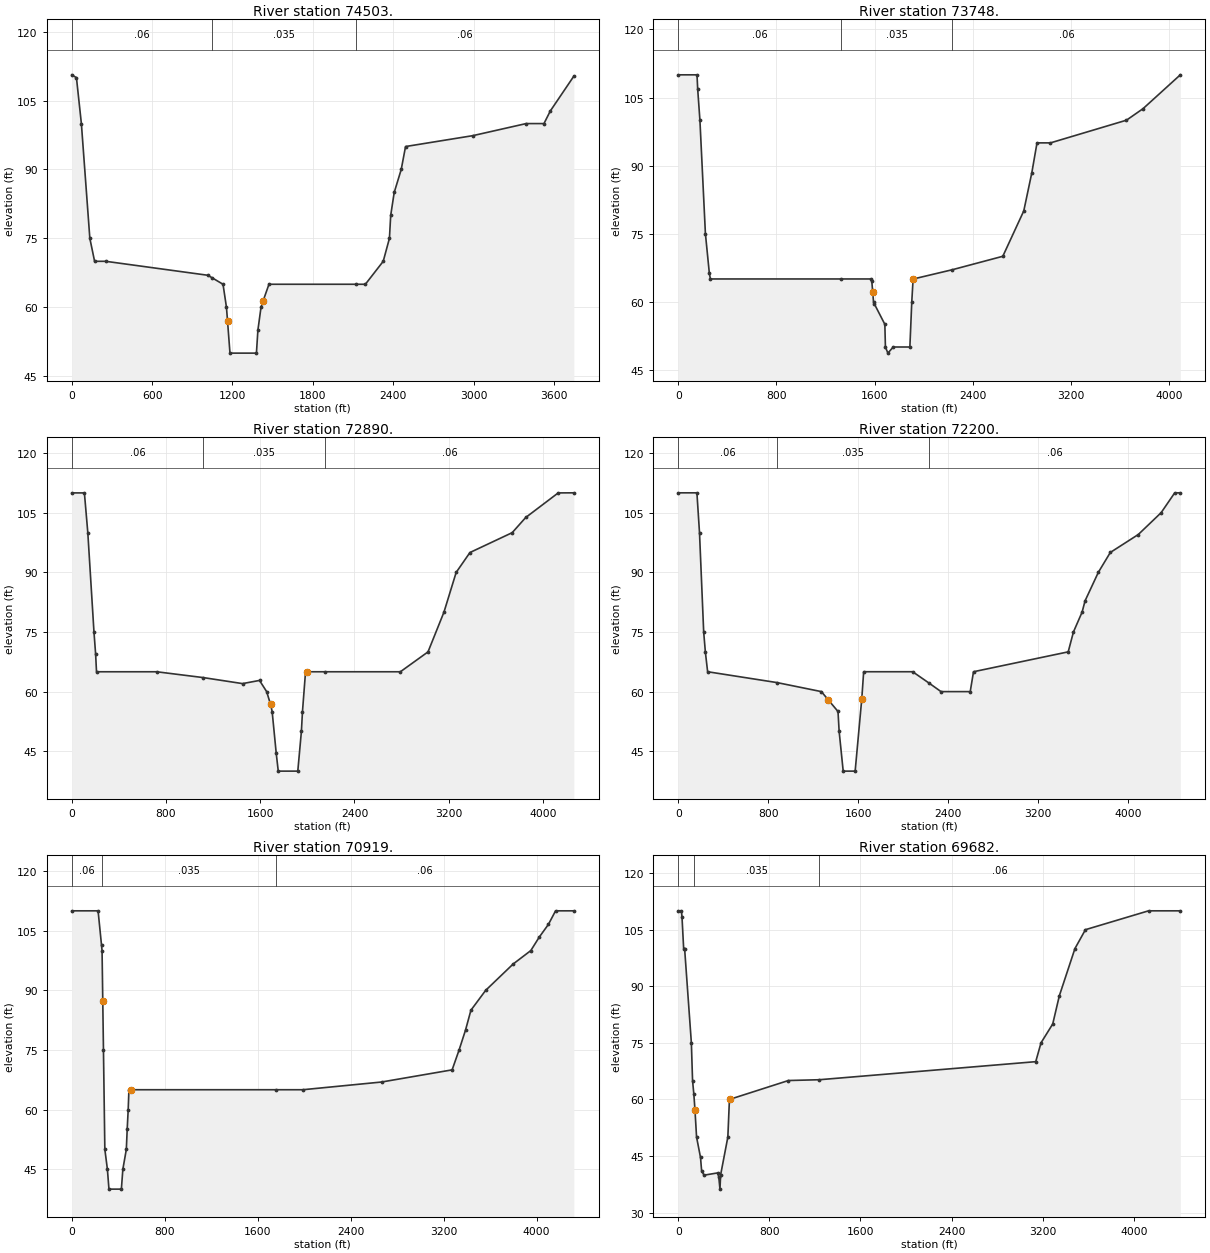
Type RM Length L Ch R = 1 ,74503.  ,743,755.24,661.95
XS GIS Cut Line= 6
 6443804.1913167 2046763.4941973 6443544.7312336 2047366.1111753
 6443494.5131561 2047834.8132167 6443502.8828514  2048136.121682
 6443142.9866132 2049115.3742416  6442657.545181 2050295.4991115
#Sta/Elev= 30
       0  110.62   34.94     110   71.73     100  134.92      75  170.45      70
  253.67      70 1015.89   66.96 1047.74   66.41 1129.35      65 1154.95      60
 1162.81   57.09 1181.29      50 1378.78      50 1389.74      55 1413.09      60
 1427.95   61.31  1472.4      65 2120.74      65 2192.33      65 2325.47      70
 2371.89      75 2381.34      80 2407.53      85 2459.91      90 2492.21      95
 2994.44   97.37 3392.48     100 3525.73     100 3572.98  102.74 3748.81  110.33
#Mann= 3 ,-1 , 0
       0     .06       0 1047.74    .035       0 2120.74     .06       0
Bank Sta=1162.81,1427.95
Exp/Cntr=0.3,0.1

Type RM Length L Ch R = 1 ,73748.  ,627.58,857.96,978.44
XS GIS Cut Line= 6
 6443140.0269424  2046373.314005 6442824.9387571 2047148.4994743
 6442749.6116408 2047868.2919508 6442749.6116408 2048244.9275325
 6442582.2180647 2049040.0471253 6442088.4069372 2050287.1294161
#Sta/Elev= 30
       0     110  152.91     110  158.55  106.84  176.66     100  221.38      75
  253.57   66.22  262.15      65 1326.93      65  1573.9      65 1577.15   64.53
 1584.31    62.2 1591.06      60  1597.2   59.54 1683.51      55 1688.16      50
 1708.25   48.65 1751.92      50 1887.42      50 1903.01      60 1913.76      65
 1916.01      65 2233.86   67.04 2644.76      70 2815.45      80 2880.94    88.4
 2923.35      95  3033.2      95 3652.25     100 3786.87  102.53 4090.98     110
#Mann= 3 ,-1 , 0
       0     .06       0 1326.93    .035       0 2233.86     .06       0
Bank Sta=1584.31,1916.01
Exp/Cntr=0.3,0.1

Type RM Length L Ch R = 1 ,72890.  ,381.6,689.77,765.41
XS GIS Cut Line= 6
 6442412.3854003 2046120.8723181 6442322.7579816 2047039.6936238
 6442054.9282031 2047642.3106018 6441854.0558928 2048002.2068401
 6441686.6623168 2048420.6908039 6441653.1835826 2050236.9113385
#Sta/Elev= 30
       0     110  107.22     110  136.15     100  188.47      75  202.35   69.51
  210.04      65  720.61      65 1117.46   63.53 1449.64   62.02 1593.74   62.82
 1654.41      60 1687.43   56.79 1701.02      55 1735.24   44.59 1752.87      40
 1918.72      40 1949.28      50 1958.44      55 1984.45      65 1993.74      65
 2151.03      65  2789.5      65 3024.01      70 3159.41      80 3263.12      90
 3380.03      95 3738.81     100  3853.7  103.82 4129.23     110 4262.05  110.02
#Mann= 3 ,-1 , 0
       0     .06       0 1117.46    .035       0 2151.03     .06       0
Bank Sta=1687.43,1993.74
Exp/Cntr=0.3,0.1

Type RM Length L Ch R = 1 ,72200.  ,1355.27,1280.43,700.89
XS GIS Cut Line= 6
 6442097.0854888 2046110.3623085 6442054.9282031 2046872.3000478
 6441770.3591285 2047257.3053248 6441310.0267351 2047407.9595574
 6440899.9124193 2048328.6243442 6440899.9124193 2050061.1480671
#Sta/Elev= 30
       0     110  166.13     110  189.17     100  226.38      75  241.51   69.91
  261.47      65  879.03   62.27 1273.71      60 1333.92   57.95 1421.38      55
 1431.42      50 1467.54      40  1573.9      40 1633.05   58.25 1649.63      65
 2085.48      65  2232.5   62.12 2337.79      60 2597.66      60 2626.83      65
 3469.34      70 3515.83      75 3592.92      80 3619.52   82.85 3737.34      90
 3843.94      95  4092.6   99.51 4295.84     105 4416.96     110 4466.62     110
#Mann= 3 ,-1 , 0
       0     .06       0  879.03    .035       0  2232.5     .06       0
Bank Sta=1333.92,1633.05
Exp/Cntr=0.3,0.1

Type RM Length L Ch R = 1 ,70919.  ,1242.43,1237.3,794.15
XS GIS Cut Line= 5
 6440941.7608015 2045993.4836906 6440939.6020742 2046531.0236493
 6440548.3858291 2047223.8265906 6440355.8832143 2048420.6908039
 6440343.3286949 2050195.0629564
#Sta/Elev= 30
       0     110   226.4     110     256  101.35  260.59     100   266.7   87.35
  272.68      75  284.57      50  306.53      45  319.95      40  426.82      40
  439.55      45   469.5      50  476.79      55   485.5      60   491.8      65
  512.41      65 1759.38      65 1988.03      65 2665.31   66.94 3272.63      70
 3332.51      75 3387.76      80 3434.35      85  3561.2      90 3797.51   96.62
 3949.46     100 4022.04  103.38 4101.08  106.59 4162.66     110 4319.84     110
#Mann= 3 ,-1 , 0
       0     .06       0     256    .035       0 1759.38     .06       0
Bank Sta=266.7,512.41
Exp/Cntr=0.3,0.1

Type RM Length L Ch R = 1 ,69682.  ,919.69,907.93,730.11
XS GIS Cut Line= 2
   6439700.45495 2046132.9945808 6439798.0847028 2050541.3542801
#Sta/Elev= 30
       0     110   27.99     110   33.09  108.34   47.55     100   56.02     100
  115.28      75  125.73      65  137.06    61.4  146.72   57.31  160.98      50
  195.64    44.6   205.2    41.1   226.4    39.9  346.43    40.5  356.11    39.4
  366.44    36.2  372.38      40  435.69      50  449.67      60  451.53      60
  967.64      65 1239.22   65.21 3139.72      70 3186.18      75 3289.02      80
 3346.89   87.46  3484.1     100 3576.18     105 4130.34     110 4409.44     110
#Mann= 3 ,-1 , 0
       0     .06       0  137.06    .035       0 1239.22     .06       0
Bank Sta=146.72,451.53
Exp/Cntr=0.3,0.1

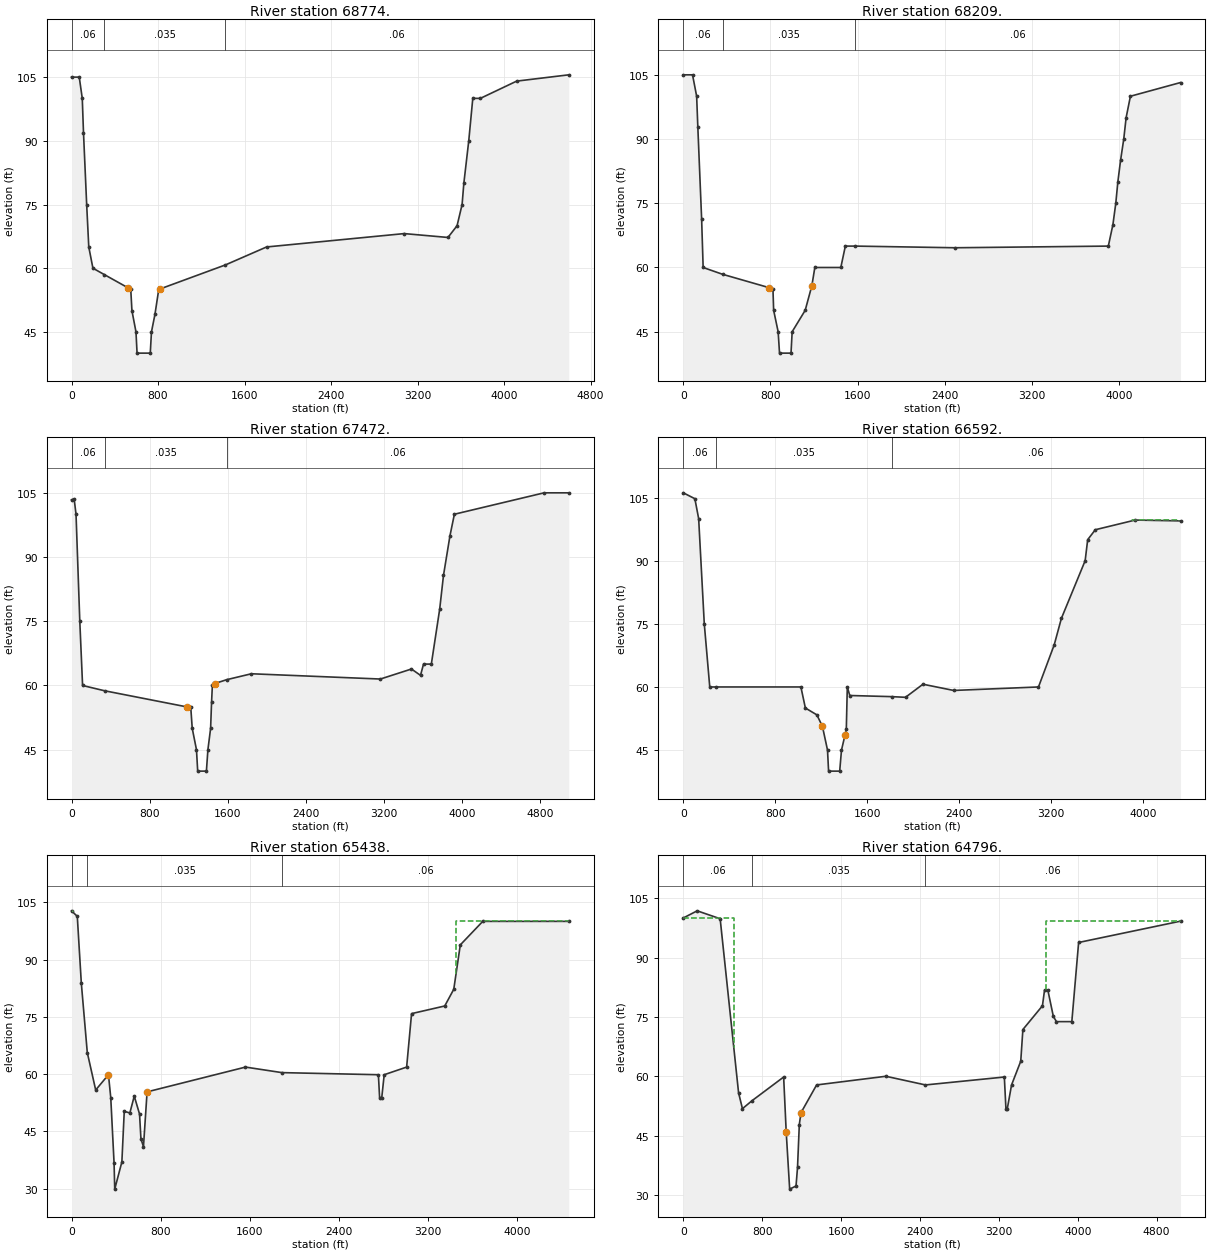
Type RM Length L Ch R = 1 ,68774.  ,628.2,565.13,569.31
XS GIS Cut Line= 6
  6438833.516942 2045797.7116494  6438774.013724 2046292.6997439
 6438836.7863209 2046564.7142991 6438993.7178369 2047265.6750202
 6439098.3388161 2049462.7159605 6439255.2703321  2050351.994425
#Sta/Elev= 30
       0     105   71.38     105   99.34     100  110.64   91.94  140.05      75
  159.52      65  197.91      60  302.31   58.51  517.75   55.45   547.8      55
  558.65      50  596.08      45  606.06      40   728.3      40  739.29      45
  771.36    49.1  806.64      55  814.09   55.07 1423.92   60.78 1803.84      65
 3076.82   68.15 3481.45   67.24 3565.58      70  3612.2      75 3628.32      80
 3673.75      90 3711.14     100 3781.48     100 4117.08  104.06 4598.58  105.54
#Mann= 3 ,-1 , 0
       0     .06       0  302.31    .035       0 1423.92     .06       0
Bank Sta=517.75,814.09
Exp/Cntr=0.3,0.1

Type RM Length L Ch R = 1 ,68209.  ,565.52,737.02,720.25
XS GIS Cut Line= 5
 6438195.9826936  2045732.323502 6438146.2877546 2046324.0860187
 6438418.3023571 2046972.7362029 6438491.5370141  2048678.058475
 6438815.8621062 2050205.5250637
#Sta/Elev= 30
       0     105   84.56     105  122.31     100  133.16   92.79  167.93   71.38
  181.96      60  360.73   58.41  789.09   55.28     823      55  829.26      50
  870.65      45   883.3      40  988.78      40  999.33      45 1119.03      50
 1180.18   55.74 1207.51      60    1446      60 1487.69      65 1578.91      65
 2494.92   64.61  3902.4      65 3944.46      70 3970.97      75 3989.87      80
 4014.71      85 4044.07      90 4065.91      95 4105.27     100 4565.63   103.2
#Mann= 3 ,-1 , 0
       0     .06       0  360.73    .035       0 1578.91     .06       0
Bank Sta=789.09,1180.18
Exp/Cntr=0.3,0.1

Type RM Length L Ch R = 1 ,67472.  ,534.71,879.77,1109.86
XS GIS Cut Line= 5
 6437646.7224822 2045748.6705388 6437620.5672137 2046481.0175347
 6437764.4211192 2047461.8393679 6437699.0329718 2049528.1040606
 6437908.2749773 2050809.7113152
#Sta/Elev= 30
       0  103.38   27.01  103.55   46.07     100   84.65      75  113.16      60
  338.23   58.77 1181.41      55 1220.25      55 1235.57      50 1279.08      45
 1291.53      40 1380.76      40 1396.07      45 1423.83      50 1433.46   56.06
  1441.8      60 1463.68   60.44 1588.71   61.36 1841.15   62.74 3161.65   61.51
 3479.73   63.85 3572.55   62.37 3603.36      65 3683.28      65 3768.72   77.82
 3807.64   85.71  3874.2      95 3919.15     100 4837.47     105    5090     105
#Mann= 3 ,-1 , 0
       0     .06       0  338.23    .035       0 1588.71     .06       0
Bank Sta=1181.41,1463.68
Exp/Cntr=0.3,0.1

Type RM Length L Ch R = 1 ,66592.  ,1087.81,1153.74,752.73
XS GIS Cut Line= 6
 6437117.0786866  2045732.323502 6437084.3846129 2046598.7161244
 6436731.2887492 2047187.2092621 6436639.7453806 2047658.0037629
 6436574.3572332 2049044.2319493 6436798.3247924 2049920.6601026
#Sta/Elev= 30
       0  106.13  100.33  104.73  133.36     100  182.27      75  229.92      60
  285.34      60 1022.66      60 1061.63      55  1162.1   53.36 1210.17   50.61
 1254.26      45 1263.53      40 1360.22      40 1375.82      45 1407.05   48.63
 1417.82      50 1426.41      60  1447.9   57.97 1812.97    57.7 1932.81   57.54
 2084.37   60.65 2351.79   59.17 3089.54      60 3226.19      70  3288.6   76.29
 3495.37      90 3517.51      95 3583.77   97.36 3930.59   99.66 4325.28   99.46
#Mann= 3 ,-1 , 0
       0     .06       0  285.34    .035       0 1812.97     .06       0
#XS Ineff= 1 ,-1
 3905.43 4315.0799.58437
Permanent Ineff=
       F
Bank Sta=1210.17,1407.05
Exp/Cntr=0.3,0.1

Type RM Length L Ch R = 1 ,65438.  ,808.34,642.22,407.65
XS GIS Cut Line= 5
 6436155.8732693 2045644.0495124 6435998.9417533 2046441.7846557
 6435985.8641427 2047527.2275153 6436038.1746323 2049096.5424862
 6436296.2783515 2050055.3554868
#Sta/Elev= 30
       0  102.76   51.73  101.31   87.81   83.84  141.41   65.64  216.78   55.84
  331.36   59.84     352   53.84  381.76    36.7   387.7   29.88  451.71      37
   473.1   50.24  523.51   49.84   562.9   54.24  610.25   49.55  622.89   43.04
  645.53      41  678.02   55.35 1561.04   61.84  1888.2   60.39 2753.52   59.84
  2764.5   53.84 2783.72   53.84 2805.65   59.84 3006.99   61.84 3051.23   75.84
 3348.82   77.84 3429.95   82.22  3488.6   93.84 3690.07     100 4461.68     100
#Mann= 3 ,-1 , 0
       0     .06       0  141.41    .035       0  1888.2     .06       0
#XS Ineff= 2 ,-1
       0   14.98102.7593 3450.41 4461.68     100
Permanent Ineff=
       F       F
Bank Sta=331.36,678.02
Exp/Cntr=0.3,0.1

Type RM Length L Ch R = 1 ,64796.  ,1335.46,1502.43,1016.55
XS GIS Cut Line= 6
 6435188.1290467 2045192.8714748 6435204.4760363 2045634.2413281
 6435613.1518158 2046582.3690875 6435564.1107526 2048445.9306273
 6435662.1929264 2049557.5287554 6435867.7021031 2050104.3356308
#Sta/Elev= 30
       0  100.04  140.64  101.84  373.46   99.84  560.32   55.84  599.44   51.84
  695.74   53.84 1017.35   59.84 1043.37   45.89 1078.27   31.51 1142.83    32.3
 1157.99      37 1176.17   47.84  1193.1   50.82 1351.52   57.84 2054.08   60.03
 2455.56   57.84 3255.17   59.84 3271.39   51.84 3285.29   51.84 3328.41   57.84
 3421.66   63.84 3443.28   71.84 3641.58   77.84 3663.05   81.84 3696.08   81.84
 3752.25   75.15 3783.79   73.84 3939.56   73.84 4008.51   93.84 5042.14   99.23
#Mann= 3 ,-1 , 0
       0     .06       0  695.74    .035       0 2455.56     .06       0
#XS Ineff= 2 ,-1
       0  511.96100.0435 3681.43 5042.1499.22931
Permanent Ineff=
       F       F
Bank Sta=1043.37,1193.1
Exp/Cntr=0.3,0.1

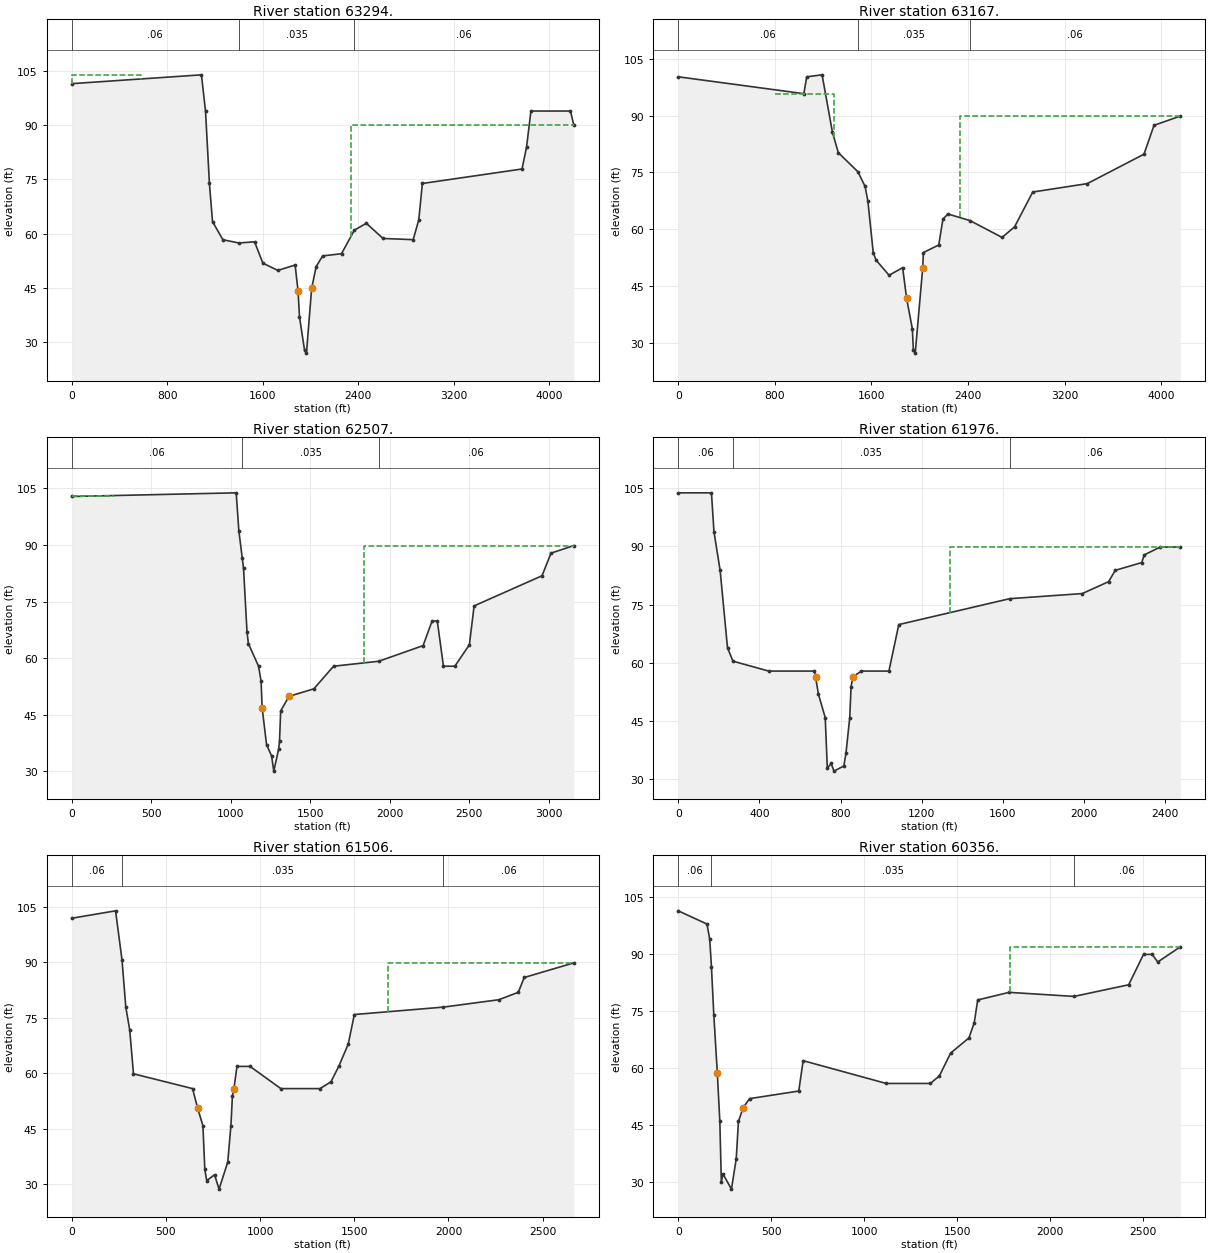
Type RM Length L Ch R = 1 ,63294.  ,146.23,126.59,127.85
XS GIS Cut Line= 6
 6434658.9310454 2045482.6597695 6434612.8921591 2048484.6236115
 6434566.0549328  2048644.421313 6434322.6433492 2048929.7315952
 6433975.6552647  2049219.010289 6433885.7071562 2049405.3313777
#Sta/Elev= 30
       0   101.4 1086.07  103.84 1120.13   93.84 1152.78   73.84 1178.82   63.32
 1265.55   58.31 1399.21   57.41  1530.9   57.74 1600.43   51.84  1726.2   49.84
  1870.6   51.33 1895.35   44.05  1907.2      37 1949.65   27.76 1965.43      27
 2008.85   44.85  2046.8   50.88 2101.13   53.84 2259.03   54.45  2366.7   60.95
 2467.27   62.85 2606.77   58.66 2859.26   58.33 2906.53   63.84 2936.13   73.84
 3770.96   77.84 3808.58   83.84 3845.47   93.84 4176.74   93.84 4204.85   89.92
#Mann= 3 ,-1 , 0
       0     .06       0 1399.21    .035       0  2366.7     .06       0
#XS Ineff= 2 ,-1
       0  578.52  103.84 2337.68 4204.8589.92156
Permanent Ineff=
       F       F
Bank Sta=1895.35,2008.85
Exp/Cntr=0.3,0.1

Type RM Length L Ch R = 1 ,63167.  ,743.18,660.33,577.69
XS GIS Cut Line= 6
  6434531.034095 2045476.2022372  6434486.156082 2048360.6426263
  6434395.236674 2048614.1148752 6434020.9971537 2049008.5339473
 6433898.5568995  2049186.885978 6433821.4585343  2049418.181121
#Sta/Elev= 30
       0   100.3 1040.58   95.84 1064.27  100.29 1191.62  100.82  1277.5    85.6
 1326.15   80.23 1487.86   75.22 1547.72   71.33 1571.08   67.41  1615.3   53.84
 1638.92   51.84 1746.44   47.84 1858.93   49.84 1891.68   41.74 1939.21    33.7
    1948      28 1963.15   27.25 2024.95   49.68  2030.7   53.84    2158   55.84
 2192.77   62.68 2233.92   64.03 2417.06   62.28 2682.68   57.84 2786.04   60.63
  2936.6   69.84 3388.29   72.06 3858.26   79.84 3941.25   87.47 4159.06   89.92
#Mann= 3 ,-1 , 0
       0     .06       0 1487.86    .035       0 2417.06     .06       0
#XS Ineff= 2 ,-1
  799.29 1288.68   95.84 2330.72 4159.0689.92002
Permanent Ineff=
       F       F
Bank Sta=1891.68,2024.95
Exp/Cntr=0.3,0.1

Type RM Length L Ch R = 1 ,62507.  ,394.8,530.9,564.51
XS GIS Cut Line= 6
  6433795.743238 2046345.3534543 6433786.0461947 2046994.0967451
 6433839.9243484 2047479.0001284  6434018.701867 2047790.0240028
 6434043.1919153 2048512.4810681 6433782.9093517 2049411.7562494
#Sta/Elev= 30
       0  102.87 1033.73  103.84 1050.23   93.84 1071.87   86.51 1079.75   83.84
 1101.56   67.03 1110.36   63.84 1174.28   57.84 1190.34   53.84 1196.72   46.88
 1224.53      37 1256.19   34.07    1270      30 1300.76   35.88 1306.09      38
 1313.48      46 1365.98   49.84 1522.02   51.84 1646.07   57.84  1929.7   59.15
 2208.78    63.3 2265.42   69.84 2298.06   69.84 2336.64   57.84 2408.44   57.84
 2499.72   63.53  2529.5   73.84 2956.54   81.84 3012.86   87.84 3156.51   89.84
#Mann= 3 ,-1 , 0
       0     .06       0 1071.87    .035       0  1929.7     .06       0
#XS Ineff= 2 ,-1
       0  263.44 103.031 1834.19 3156.51   89.84
Permanent Ineff=
       F       F
Bank Sta=1196.72,1365.98
Exp/Cntr=0.3,0.1

Type RM Length L Ch R = 1 ,61976.  ,394.49,469.55,582.71
XS GIS Cut Line= 5
 6433522.0861832  2047165.499819 6433467.6752821 2047802.2690506
 6433546.0434842 2048115.7419535 6433438.2871768 2048879.8321247
 6433634.2077529 2049594.9421518
#Sta/Elev= 30
       0  103.84  163.81  103.84  176.03   93.84  206.48   83.84  242.93   63.84
  269.74    60.4  445.97   57.84  671.79   57.84  676.94   56.31  691.39   51.84
  724.66   45.84  735.01   32.76  753.92      34  767.84   32.02  816.39   33.35
     827   36.67  845.58   45.84  852.11   53.84  861.75   56.38  902.97   57.84
  1038.7   57.84 1087.33   69.84 1633.97   76.52 1991.83   77.84 2121.84   80.91
 2154.65   83.84 2285.05   85.84  2297.6   87.84  2376.5   89.84 2475.32   89.84
#Mann= 3 ,-1 , 0
       0     .06       0  269.74    .035       0 1633.97     .06       0
#XS Ineff= 1 ,-1
 1341.06 2475.32   89.84
Permanent Ineff=
       F
Bank Sta=676.94,861.75
Exp/Cntr=0.3,0.1

Type RM Length L Ch R = 1 ,61506.  ,1271.35,1150.01,496.74
XS GIS Cut Line= 4
 6433067.5283831 2047100.5391948 6433095.4262159 2047586.7564358
 6432968.0778698 2048252.8863189 6433389.3070801 2049692.9024399
#Sta/Elev= 30
       0  101.84  232.54  103.84  266.81   90.53  286.89   77.85  307.54   71.73
  327.62   59.84  641.33   55.84  668.15   50.56  696.26   45.84  706.38      34
  716.51      31  757.94   32.58  782.02    28.7  828.05      36  844.94   45.84
  852.86   53.84  861.01   55.85  877.12   61.84  946.36   61.84 1110.03   55.84
 1318.09   55.84 1375.85   57.67 1417.34   61.84 1467.69   67.84 1500.18   75.84
 1972.46   77.84 2267.45   79.84 2370.73   81.84 2402.03   85.84 2665.57   89.79
#Mann= 3 ,-1 , 0
       0     .06       0  266.81    .035       0 1972.46     .06       0
#XS Ineff= 1 ,-1
 1680.55 2665.57 89.7892
Permanent Ineff=
       F
Bank Sta=668.15,861.01
Exp/Cntr=0.3,0.1

Type RM Length L Ch R = 1 ,60356.  ,617.68,559.05,204.03
XS GIS Cut Line= 4
  6431772.962469 2047527.9802724 6432128.6324184 2047825.5568555
 6432480.6628347 2048324.2666553 6433183.5904846  2049790.862728
#Sta/Elev= 30
       0  101.32  154.56   97.84  169.41   93.84  178.57   86.59  191.38   73.84
  210.11   58.71  223.72   45.84  231.77      30  240.57      32  286.21      28
     312      36  323.83   45.84  349.44   49.49  383.85   51.84  648.22   53.84
  671.83   61.84 1118.95   55.84 1356.37   55.84 1404.76   57.84  1465.2   63.84
 1563.58   67.84 1592.15   71.84 1610.82   77.84 1779.58   79.84 2128.66   78.77
 2422.88   81.84 2502.71   89.84 2549.11   89.84 2579.22   87.84 2700.53   91.84
#Mann= 3 ,-1 , 0
       0     .06       0  178.57    .035       0 2128.66     .06       0
#XS Ineff= 1 ,-1
 1786.18 2700.53   91.84
Permanent Ineff=
       F
Bank Sta=210.11,349.44
Exp/Cntr=0.3,0.1

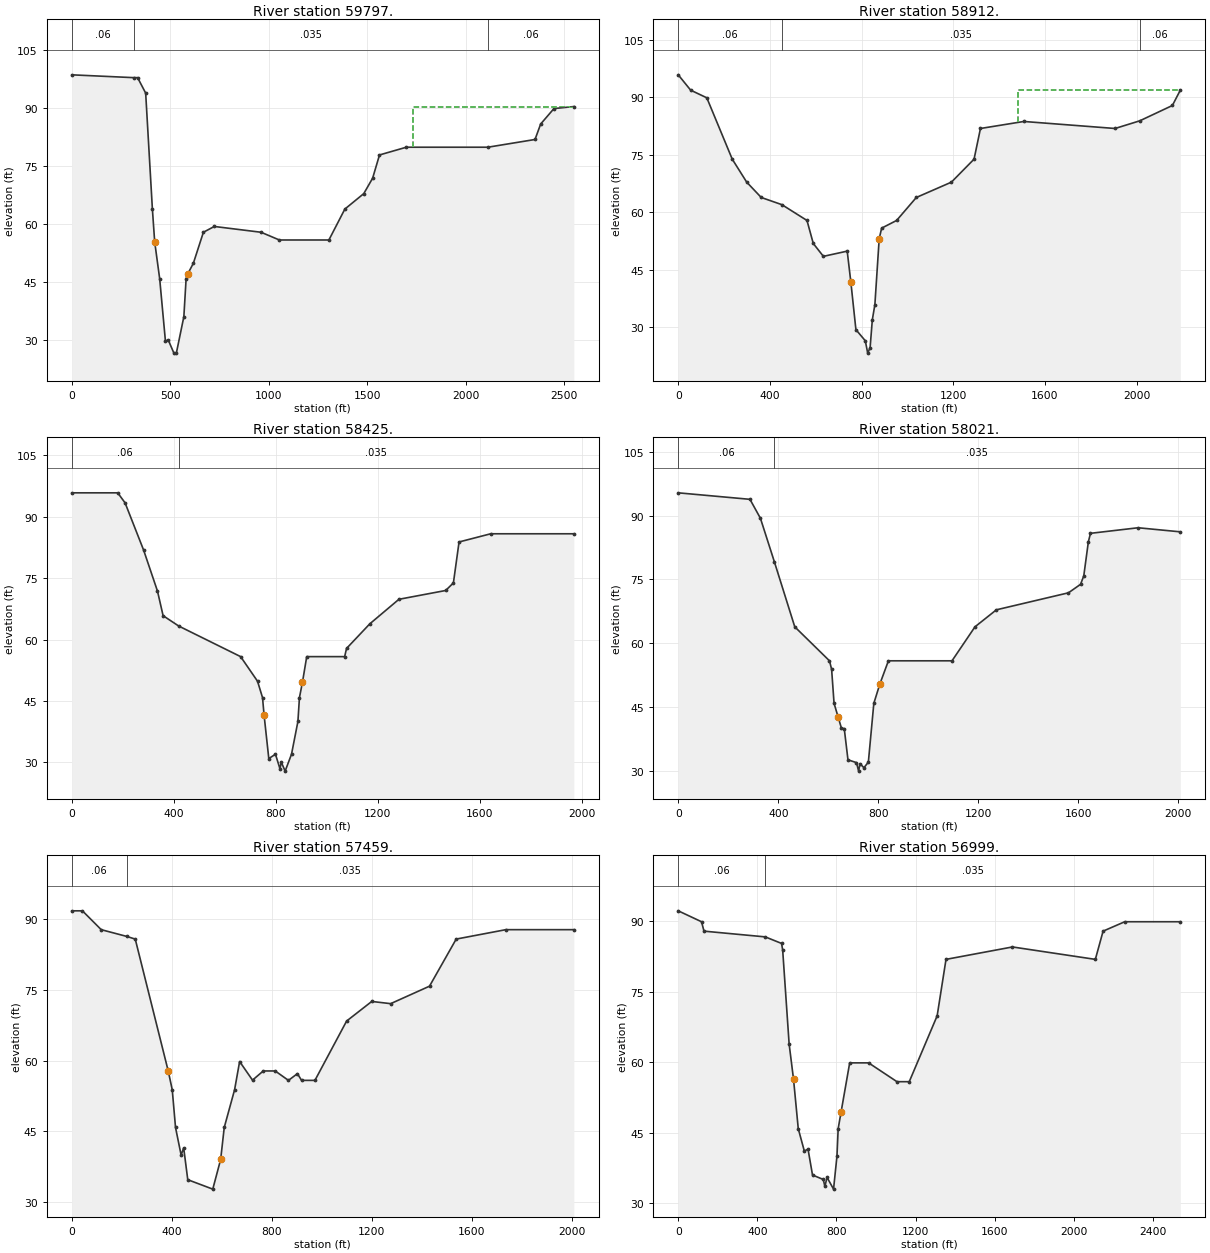
Type RM Length L Ch R = 1 ,59797.  ,527.79,884.89,991.41
XS GIS Cut Line= 5
 6431459.4895661 2047998.1896267 6431704.3902389 2048233.2942802
 6432057.0472665 2048233.2942802  6432311.744006 2048419.4187897
 6432977.8738891 2049810.4547666
#Sta/Elev= 30
       0   98.57  314.06   97.84  334.39   97.84  375.32   93.84  409.45   63.84
  421.13   55.34  446.43   45.84  475.71   29.67  489.74      30  517.98   26.66
  531.13   26.57  569.25      36  580.74   45.84  589.99   47.14   617.7   49.84
  668.43   57.84  723.92   59.34   961.3   57.84 1054.44   55.84 1305.89   55.84
 1386.96   63.84 1483.06   67.84  1528.1   71.84 1562.85   77.84  1699.1   79.84
  2112.9   79.84 2352.69   81.84 2381.35   85.84 2448.86   89.84 2549.91   90.36
#Mann= 3 ,-1 , 0
       0     .06       0  314.06    .035       0  2112.9     .06       0
#XS Ineff= 1 ,-1
 1735.39 2549.9190.35913
Permanent Ineff=
       F
Bank Sta=421.13,589.99
Exp/Cntr=0.3,0.1

Type RM Length L Ch R = 1 ,58912.  ,352.75,487.76,567.47
XS GIS Cut Line= 2
 6431214.5888459 2048252.8863189 6432213.7837179 2050202.2958716
#Sta/Elev= 30
       0   95.84   54.17   91.84  124.72   89.84  235.63   73.84  298.73   67.84
  362.12   63.84  452.46   61.96  561.75   57.84  589.17   51.84  633.27   48.48
  737.23   49.84  753.25   41.69   775.2   29.36  816.18   26.45  826.68   23.23
  837.19   24.69  846.82   31.93  857.97   35.89  876.78   53.06  887.47   55.84
  952.72   57.84 1038.75   63.84 1191.91   67.84 1290.67   73.84 1318.62   81.84
 1507.85   83.67 1905.78   81.84  2013.7   83.84 2155.96   87.84 2190.57   91.84
#Mann= 3 ,-1 , 0
       0     .06       0  452.46    .035       0  2013.7     .06       0
#XS Ineff= 1 ,-1
 1482.24 2190.57   91.84
Permanent Ineff=
       F
Bank Sta=753.25,876.78
Exp/Cntr=0.3,0.1

Type RM Length L Ch R = 1 ,58425.  ,441.7,403.69,386.57
XS GIS Cut Line= 4
 6430885.8606241 2048342.2654694 6431107.8318126 2048799.6605337
 6431107.8318126 2049270.5084276 6431471.0573077  2050192.025042
#Sta/Elev= 30
       0   95.84  180.18   95.84  209.07    93.4  281.95   81.84  336.27   71.84
  358.34   65.84  419.35   63.32  662.45   55.84  728.69   49.84  748.38   45.84
  754.36   41.64  772.99   30.95  799.19      32  816.85   28.44  821.98   30.08
  837.09   27.88  862.08      32  887.22      40  893.23   45.84  904.94   49.54
   921.8   55.84 1070.59   55.84 1078.01   57.84 1169.13   63.84 1283.51   69.84
 1466.82   71.99 1497.26   73.84 1519.44   83.84 1643.57   85.84 1969.78   85.84
#Mann= 2 ,-1 , 0
       0     .06       0  419.35    .035       0
Bank Sta=754.36,904.94
Exp/Cntr=0.3,0.1

Type RM Length L Ch R = 1 ,58021.  ,581.56,561.67,525.46
XS GIS Cut Line= 5
 6430569.7199136 2048422.9822092 6430647.1710139 2048632.2932755
 6430735.1786535 2049365.6900038 6430999.2014303 2050084.4187843
 6431128.0109857 2050333.2794433
#Sta/Elev= 30
       0   95.37  286.88   93.84  328.65   89.38  384.76   79.08  465.98   63.84
  604.81   55.84  613.37   53.84  623.11   45.84  639.46   42.59  652.59      40
  663.92   39.88  678.75   32.54  712.84   31.88  721.37   29.88  726.76   31.64
   742.6   30.68  760.29      32  782.19   45.84  805.81    50.3  840.43   55.84
 1094.79   55.84 1186.69   63.84 1272.21   67.84 1560.37   71.84 1608.86   73.84
 1621.76   75.84 1640.04   83.84 1648.53   85.84 1839.01   87.15 2007.75   86.19
#Mann= 2 ,-1 , 0
       0     .06       0  384.76    .035       0
Bank Sta=639.46,805.81
Exp/Cntr=0.3,0.1

Type RM Length L Ch R = 1 ,57459.  ,448.27,460.04,476.86
XS GIS Cut Line= 3
 6430031.6080147 2048685.3117913 6430193.0415891 2049371.4044352
 6430690.7950945 2050575.4297576
#Sta/Elev= 30
       0   91.84   42.61   91.84  117.75   87.84  219.53   86.41  253.81   85.84
  385.87    57.8   401.8   53.84  414.88   45.84  437.24      40  447.55    41.5
  463.86   34.75  563.85   32.75  595.38   39.05   609.7   45.84  651.05   53.84
  671.21   59.84  722.72   55.89  765.75   57.84  813.51   57.84  866.43   55.84
  902.41   57.27  918.85   55.84  972.33   55.84  1099.1   68.44 1199.57    72.6
 1275.18   72.13  1430.5   75.84 1537.21   85.84 1735.71   87.84 2007.69   87.84
#Mann= 2 ,-1 , 0
       0     .06       0  219.53    .035       0
Bank Sta=385.87,595.38
Exp/Cntr=0.3,0.1

Type RM Length L Ch R = 1 ,56999.  ,356.17,351.22,350.04
XS GIS Cut Line= 3
  6429574.212903   2048544.05739 6429722.1936953 2049418.4892199
 6430152.6831955 2051012.6456962
#Sta/Elev= 30
       0   92.16  117.73   89.84  130.22   87.84  440.07   86.62  522.27   85.23
  527.97   83.84  560.63   63.84  582.94   56.32  606.77   45.84   637.4    41.1
  656.14    41.5   678.8      36  733.24   35.05   741.4   33.57  752.17    35.5
  785.16      33  802.36      40  808.48   45.84  822.89   49.31  866.74   59.84
  962.29   59.84 1105.69   55.84 1167.87   55.84 1308.92   69.84 1353.67   81.84
 1689.62   84.48 2108.58   81.84 2147.78   87.84 2257.19   89.84 2538.12   89.84
#Mann= 2 ,-1 , 0
       0     .06       0  440.07    .035       0
Bank Sta=582.94,822.89
Exp/Cntr=0.3,0.1

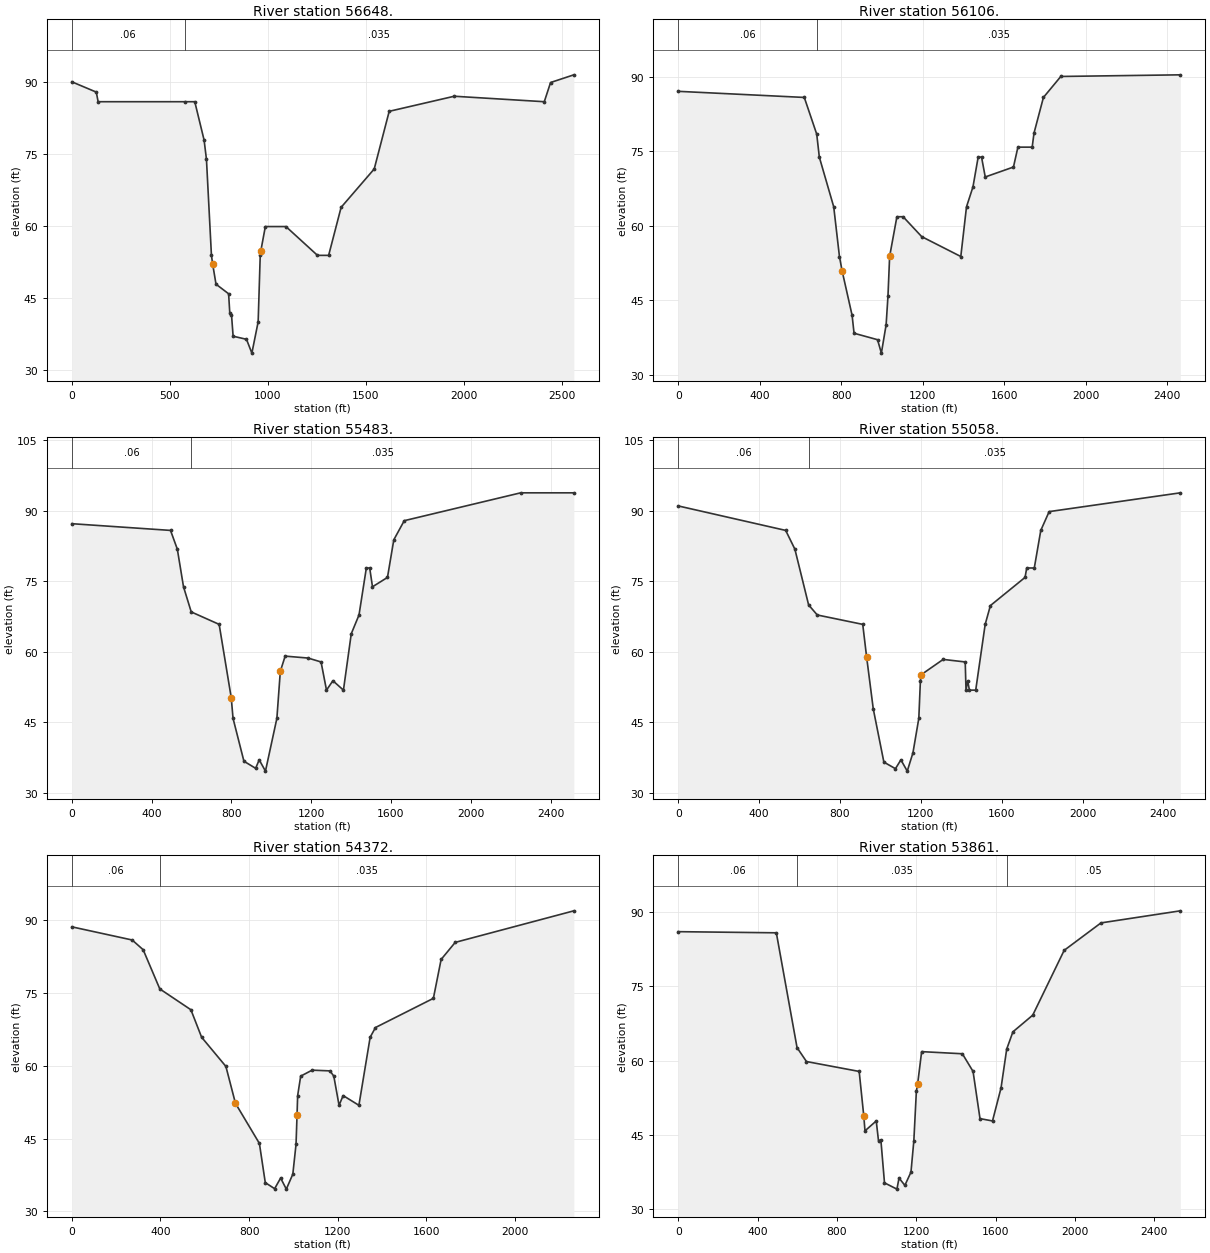
Type RM Length L Ch R = 1 ,56648.  ,522.44,542.07,563.75
XS GIS Cut Line= 3
 6429184.0817964 2048476.7934323 6429385.8737644 2049505.9323981
 6429782.7312621 2050965.5609115
#Sta/Elev= 30
       0   89.99   125.1   87.84  134.44   85.84  576.06   85.84  627.48   85.84
  675.12   77.84  687.12   73.84  712.53   53.84  718.93      52  735.79   47.84
  800.15   45.84  806.04   41.87  814.84    41.5  823.13      37  891.33   36.36
  918.78   33.48  950.85      40  961.44   53.84  964.46   54.76  987.51   59.84
 1092.56   59.84 1253.54   53.84 1310.42   53.84 1374.04   63.84 1543.04   71.84
 1619.37   83.84 1951.18   86.98 2410.53   85.84 2442.68   89.84 2561.35   91.44
#Mann= 2 ,-1 , 0
       0     .06       0  576.06    .035       0
Bank Sta=718.93,964.46
Exp/Cntr=0.3,0.1

Type RM Length L Ch R = 1 ,56106.  ,617.86,622.85,632.88
XS GIS Cut Line= 4
 6428694.3159041 2048460.8182062 6428799.0112454 2049233.6785681
  6428828.347141  2049571.041084  6429051.655807 2050899.1377053
#Sta/Elev= 30
       0   87.07  618.97   85.84  680.03   78.45  692.74   73.84  763.45   63.84
  791.55   53.84  804.58   50.96  853.73      42   863.3    38.4  978.63    37.1
  997.44    34.4 1020.76    40.1 1029.79   45.84 1038.03   53.87 1073.71   61.84
 1104.26   61.84 1195.37   57.84 1387.46   53.84 1415.45   63.84 1447.15   67.84
 1472.72   73.84  1489.3   73.84 1507.49   69.84 1646.03   71.84 1667.86   75.84
 1737.95   75.84 1746.94   78.67 1793.12   85.84 1878.53   90.06 2465.29   90.39
#Mann= 2 ,-1 , 0
       0     .06       0  680.03    .035       0
Bank Sta=804.58,1038.03
Exp/Cntr=0.3,0.1

Type RM Length L Ch R = 1 ,55483.  ,407.38,425.15,445.81
XS GIS Cut Line= 4
 6428185.6320133 2048509.1642128 6428177.2240245 2049265.8840574
  6428202.447991 2049551.7560081 6428261.3040073 2051023.1556585
#Sta/Elev= 30
       0   87.27  494.97   85.84  529.07   81.84  560.01   73.84  598.71   68.49
  738.65   65.84  799.25   50.23  808.22   45.84  862.81   36.71  921.46    35.2
  939.41      37  970.78    34.6 1028.01   45.84  1045.2   55.84 1069.46   59.08
  1184.1   58.67 1249.41   57.84 1276.65   51.84 1308.76   53.84 1361.57   51.84
 1400.79   63.84 1439.62   67.84 1476.34   77.84 1493.15   77.84 1507.18   73.84
 1582.19   75.83 1613.99   83.84 1666.29   87.91 2249.73   93.84 2516.33   93.84
#Mann= 2 ,-1 , 0
       0     .06       0  598.71    .035       0
Bank Sta=799.25,1045.2
Exp/Cntr=0.3,0.1

Type RM Length L Ch R = 1 ,55058.  ,629.67,685.71,707.67
XS GIS Cut Line= 4
 6427706.3761307 2048376.7382235 6427772.2558447 2049116.3351276
 6427757.5878969 2049952.4073959 6427769.4360941 2050857.0977139
#Sta/Elev= 30
       0   91.05  531.51   85.84  577.05   81.84  644.92   69.98  687.67   67.84
  912.63   65.84  931.52      59  964.66   47.86 1017.19   36.52 1074.43   35.12
 1101.38      37 1132.86    34.6 1161.01    38.5 1190.01   45.84 1197.86   53.84
 1201.91   55.13 1310.51   58.38 1419.55   57.84 1423.46   51.84 1431.69   53.84
 1440.35   51.84 1471.48   51.84  1518.3   65.84 1544.11   69.84 1715.57   75.84
 1723.74   77.84 1761.21   77.84 1793.37   85.84 1834.66   89.84 2483.49   93.84
#Mann= 2 ,-1 , 0
       0     .06       0  644.92    .035       0
Bank Sta=931.52,1201.91
Exp/Cntr=0.3,0.1

Type RM Length L Ch R = 1 ,54372.  ,546.44,511.64,507.83
XS GIS Cut Line= 3
 6427277.5682283 2048509.1642128 6427050.5522465  2049543.347972
 6427151.4482542 2050745.6917439
#Sta/Elev= 30
       0   88.55   272.5   85.84  322.13   83.84  397.18   75.78  537.56   71.49
  585.86   65.84   695.4   59.84  738.57   52.25  846.59      44   873.1   35.94
  915.26   34.69  942.39   36.88  968.06    34.6   997.4   37.68 1011.91   43.84
 1016.43   49.84 1019.17   53.84  1032.9   57.84 1084.48   59.07 1165.01   58.92
  1182.3   57.84 1205.99   51.84 1224.45   53.84 1295.57   51.84 1346.32   65.84
 1370.43   67.84 1631.64   73.84 1666.55   81.84  1730.1   85.35 2265.38   91.84
#Mann= 2 ,-1 , 0
       0     .06       0  397.18    .035       0
Bank Sta=738.57,1016.43
Exp/Cntr=0.3,0.1

Type RM Length L Ch R = 1 ,53861.  ,555.89,594.15,591.83
XS GIS Cut Line= 4
 6426529.2563725 2048219.0882677 6426604.9283665 2049064.0920894
 6426554.8172644 2049541.7052357 6426634.3563273 2050741.4877495
#Sta/Elev= 30
       0   86.07  494.54   85.84  598.96   62.65  646.41   59.84  912.15   57.84
  935.49    48.8  941.42   45.84  998.17   47.84 1009.56   43.84 1021.54      44
 1039.78   35.34 1102.46   34.07 1113.04   36.31 1142.53   34.83 1173.21    37.5
 1187.73   43.84 1200.46   53.84 1207.03   55.36 1227.04   61.84 1432.39   61.41
 1486.23   57.84 1521.25   48.31 1584.26   47.84 1627.34   54.52  1655.9   62.36
 1687.22   65.84 1787.13   69.21 1945.54    82.3 2131.05   87.84 2531.04   90.28
#Mann= 3 ,-1 , 0
       0     .06       0  598.96    .035       0  1655.9     .05       0
Bank Sta=935.49,1207.03
Exp/Cntr=0.3,0.1