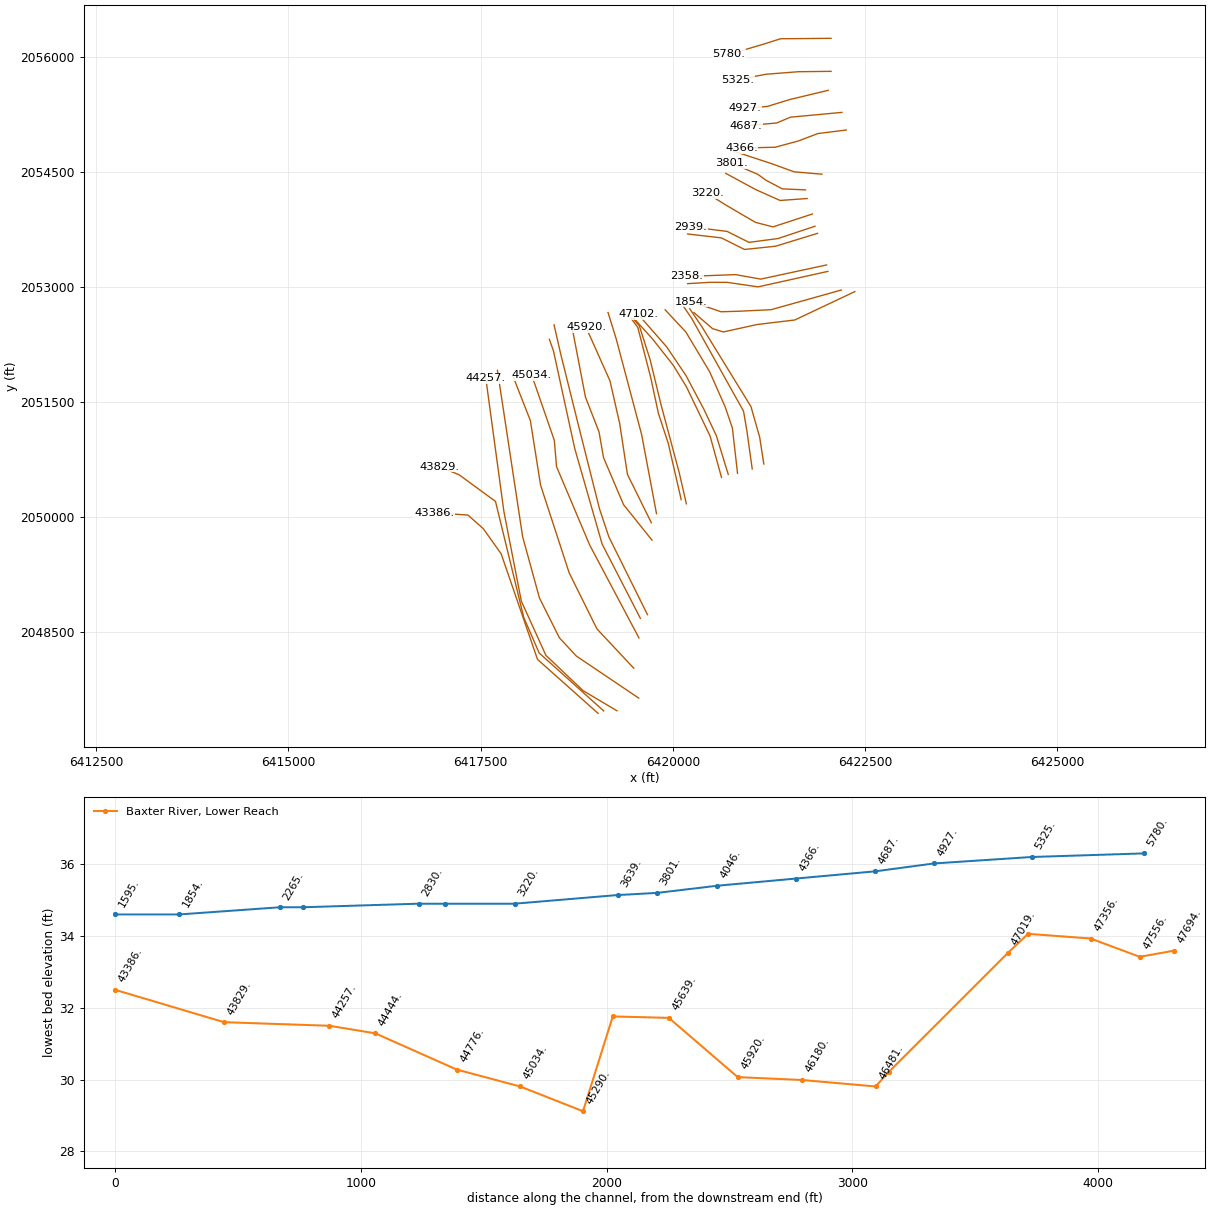
HEC-RAS study Baxter.prj: Baxter River GIS Example

--- Baxter.g01 (geometry) --- (continued)

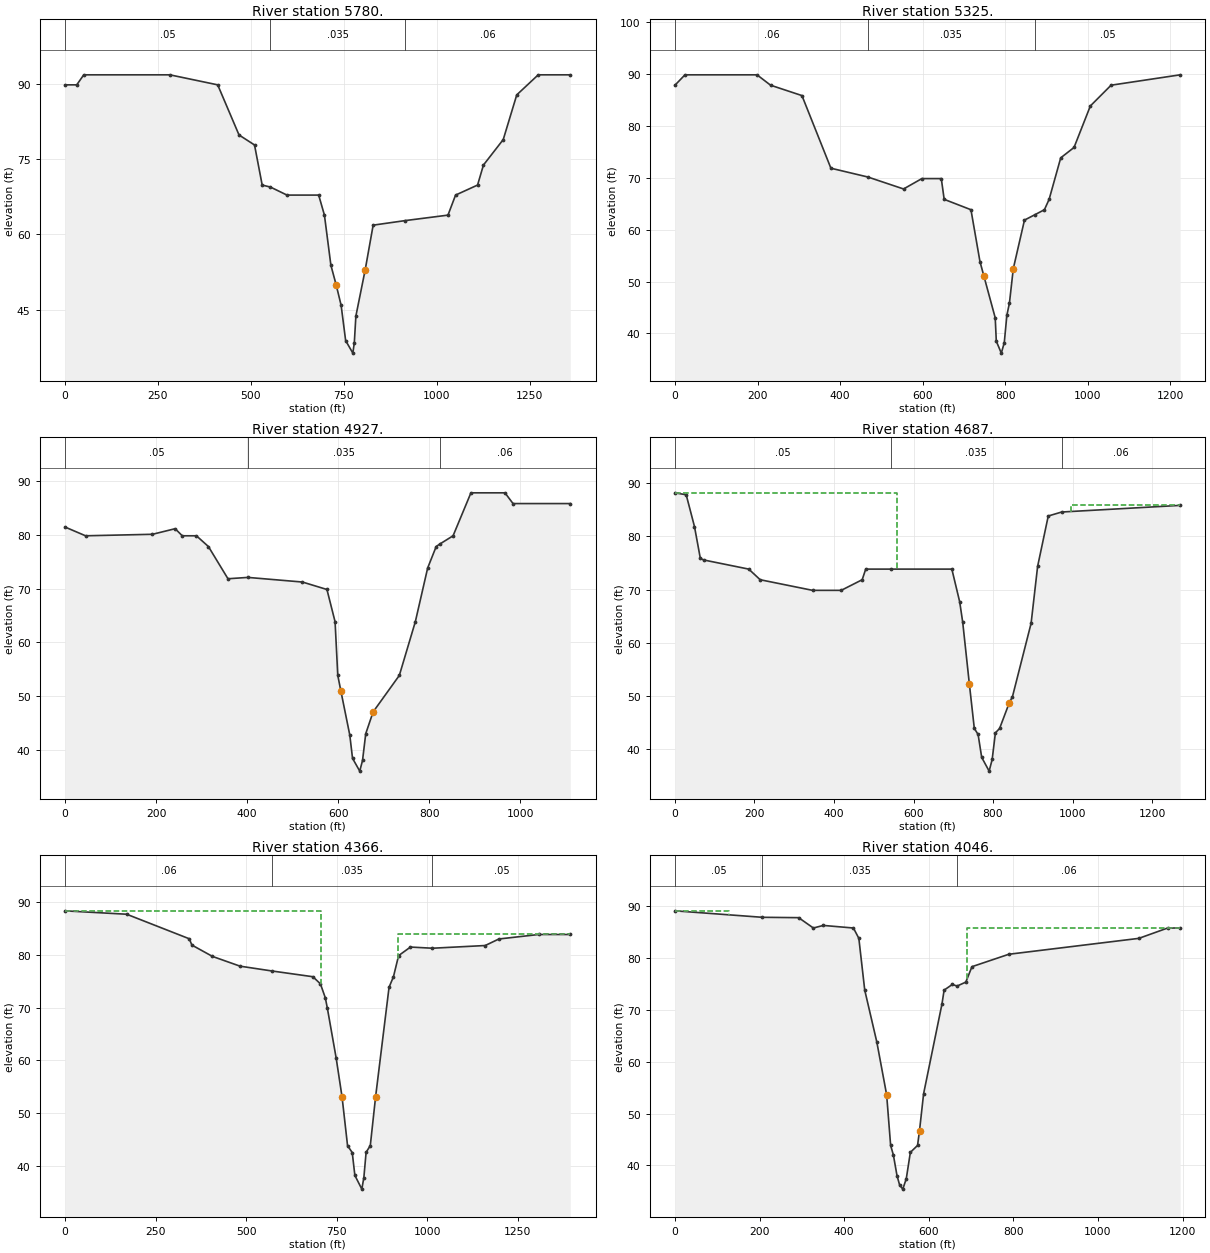
Type RM Length L Ch R = 1 ,5780.   ,445.59,455.6,394.01
XS GIS Cut Line= 4
 6422059.7326846 2056246.1201085 6421403.2361802 2056240.7389578
 6421182.6102794 2056170.7844247 6420730.5963184 2056036.2564618
#Sta/Elev= 30
       0   89.84   31.47   89.84   50.35   91.84  282.07   91.84  410.79   89.84
  468.16   79.84  509.92   77.84  530.53   69.84  552.72   69.44  597.29   67.84
  682.58   67.84  698.03   63.84  715.42   53.84  729.83   49.86  742.97   45.84
  755.13    38.8  774.53    36.3  778.48    38.4  782.68    43.7  807.72   52.92
  829.14   61.84  915.52   62.75 1030.52   63.84 1050.95   67.84 1110.13   69.84
 1125.99   73.84 1179.24   78.92 1215.62   87.84 1273.36   91.84 1359.58   91.84
#Mann= 3 ,-1 , 0
       0     .05       0  552.72    .035       0  915.52     .06       0
Bank Sta=729.83,807.72
Exp/Cntr=0.3,0.1

Type RM Length L Ch R = 1 ,5325.   ,360.91,397.41,407.35
XS GIS Cut Line= 4
 6422059.7326846 2055815.6306083 6421636.7911093 2055810.9909965
 6421214.8969943 2055777.9627427 6420843.5998205 2055708.0082096
#Sta/Elev= 30
       0   87.84   24.29   89.84  198.86   89.84  231.66   87.84  307.65   85.84
  377.82   71.84  467.17   70.15  553.86   67.84  598.21   69.84  645.27   69.84
  652.27   65.84  717.13   63.84  738.97   53.84   748.5   51.05  775.94      43
  778.55    38.5  790.67    36.2  797.84    38.2  804.14    43.5  810.36   45.84
  819.71   52.48  846.79   61.84  871.32   62.85  895.11   63.84  906.51   65.84
  934.64   73.84  966.88   75.84 1006.41   83.84 1056.62   87.84 1223.98   89.84
#Mann= 3 ,-1 , 0
       0     .06       0  467.17    .035       0  871.32     .05       0
Bank Sta=748.5,819.71
Exp/Cntr=0.3,0.1

Type RM Length L Ch R = 1 ,4927.   ,232.92,240.23,246.74
XS GIS Cut Line= 4
  6422022.064819  2055568.099096 6421518.9302103 2055447.0239625
 6421231.0403517 2055358.2354966 6420940.4599651 2055336.7109884
#Sta/Elev= 30
       0   81.47      45   79.84  192.14   80.12  241.93   81.16  257.56   79.84
   288.7   79.84  315.02   77.84  358.01   71.84  401.72   72.09  521.59   71.23
  575.49   69.84  593.36   63.84   599.3   53.84  605.98   50.99   625.7   42.73
   631.7   38.41  647.57   36.02  653.69   38.01  660.77      43  676.98   47.05
  734.55   53.84  769.72   63.84   796.8   73.84  815.56   77.84  822.85   78.27
  852.67   79.84  891.89   87.84  966.67   87.84  984.41   85.84 1110.14   85.84
#Mann= 3 ,-1 , 0
       0     .05       0  401.72    .035       0  822.85     .06       0
Bank Sta=605.98,676.98
Exp/Cntr=0.3,0.1

Type RM Length L Ch R = 1 ,4687.   ,327.57,321.23,302.9
XS GIS Cut Line= 4
 6422200.8209899   2055280.37131 6421532.3830398  2055218.326383
 6421353.3866947 2055142.5356273 6420950.0896518 2055106.8004206
#Sta/Elev= 30
       0    88.2   28.26   87.84   49.14   81.84   63.88   75.84   73.04   75.55
   185.6   73.84  214.33   71.84  346.22   69.84  418.14   69.84  470.88   71.84
  479.78   73.84  543.29   73.84  696.38   73.84   716.1   67.68  723.69   63.84
  740.47   52.18  752.87   43.84  762.43    42.7   771.4    38.4  790.17    35.8
   797.8      38  805.88      43  816.49   43.84  840.93   48.68  848.88   49.84
   895.7   63.63  912.08   74.35  938.84   83.84  972.61   84.59 1270.57   85.84
#Mann= 3 ,-1 , 0
       0     .05       0  543.29    .035       0  972.61     .06       0
#XS Ineff= 2 ,-1
       0  557.2788.20372   995.1 1270.57   85.84
Permanent Ineff=
       F       F
Bank Sta=740.47,840.93
Exp/Cntr=0.3,0.1

Type RM Length L Ch R = 1 ,4366.   ,356.48,320.19,265.47
XS GIS Cut Line= 5
  6422256.976254 2055050.6451565 6421889.4144178 2055004.6998974
 6421634.1631098  2054907.704424 6421332.9665901 2054826.0240055
 6420893.9343877 2054815.8139531
#Sta/Elev= 30
       0   88.32   170.1   87.68  342.96   83.03  350.11   81.84  406.91   79.69
  483.13   77.84  572.02   76.92  684.19   75.84     705   74.49  718.53   71.84
  724.26   69.84  748.43   60.45  764.81   53.03  779.88   43.84  792.85   42.53
   800.1    38.2  819.32    35.6  824.94    37.8  831.13   42.58  842.68   43.84
  857.29   53.07  894.48   73.84  906.64   75.84  920.82   79.84  953.56   81.46
 1014.32   81.24 1159.86   81.75 1197.76   82.99 1307.48   83.84 1394.71   83.84
#Mann= 3 ,-1 , 0
       0     .06       0  572.02    .035       0 1014.32     .05       0
#XS Ineff= 2 ,-1
       0  706.5688.32453  918.78 1394.71   83.84
Permanent Ineff=
       F       F
Bank Sta=764.81,857.29
Exp/Cntr=0.3,0.1

Type RM Length L Ch R = 1 ,4046.   ,256.61,245.09,234.47
XS GIS Cut Line= 4
  6421940.591346 2054474.6389447 6421579.4678244 2054505.3281276
 6421283.5062871 2054612.9505263 6420792.4791728 2054774.3841007
#Sta/Elev= 30
       0   89.16  206.55   87.91  292.39   87.84  327.19   85.84  350.65   86.34
  421.91   85.84   434.7   83.84  448.62   73.84  477.12   63.84   500.4   53.63
  509.84   43.84  516.31      42  524.92      38  531.08    36.2  538.55    35.4
   546.8    37.4  556.46    42.5  573.47   43.84  578.09    46.7   587.8   53.84
  631.25   71.19  636.24   73.84  655.63   74.94  666.93   74.63  687.56   75.39
  702.05   78.37  789.23   80.77 1096.53   83.84 1164.68   85.84 1194.23   85.84
#Mann= 3 ,-1 , 0
       0     .05       0  206.55    .035       0  666.93     .06       0
#XS Ineff= 2 ,-1
       0  128.5289.16025  690.55 1194.23   85.84
Permanent Ineff=
       F       F
Bank Sta=500.4,578.09
Exp/Cntr=0.3,0.1

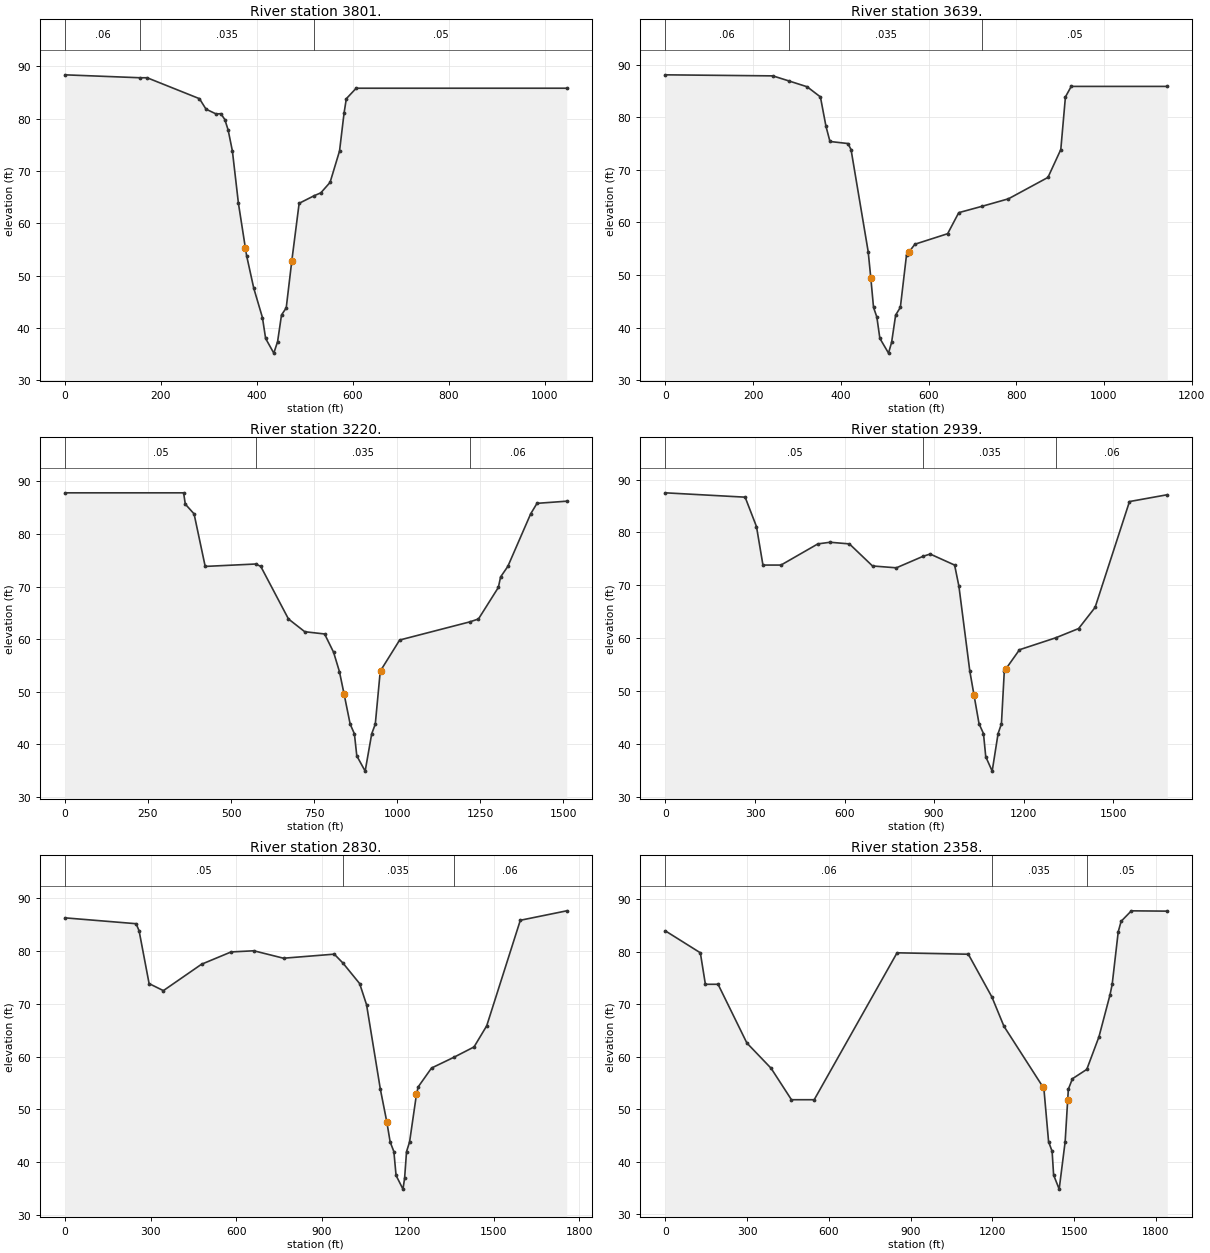
Type RM Length L Ch R = 1 ,3801.   ,152.9,161.27,167.29
XS GIS Cut Line= 5
 6421727.4485694 2054269.9042043  6421424.760641 2054283.3569864
 6421209.5158909 2054397.7057762 6421108.6199306 2054471.6961723
 6420765.5735613 2054619.6769173
#Sta/Elev= 30
       0    88.4  156.83   87.84  171.37   87.84  280.35   83.84  294.02   81.84
  315.03   80.92  324.96   80.97  333.26   79.84  340.13   77.84  348.97   73.84
  361.53   63.84  376.08   55.27  378.57   53.84  393.48   47.61  411.55      42
  418.21      38  435.23    35.2  443.14    37.4  451.28    42.5  461.11   43.84
  472.71   52.83  488.02   63.84  519.55    65.3  533.19   65.84  552.46   67.84
  572.17   73.84  581.68   81.14  586.34   83.84  606.87   85.84 1045.44   85.84
#Mann= 3 ,-1 , 0
       0     .06       0  156.83    .035       0  519.55     .05       0
Bank Sta=376.08,472.71
Exp/Cntr=0.3,0.1

Type RM Length L Ch R = 1 ,3639.   ,393.56,418.86,402.11
XS GIS Cut Line= 4
 6421749.3093876 2054157.2370123 6421396.1734318 2054132.0129986
 6421076.6695258 2054274.9489976 6420689.9016147 2054485.1489544
#Sta/Elev= 30
       0   88.04   244.9   87.84   280.7    86.9  323.07   85.77  353.36   83.84
  366.09   78.23  375.14   75.37  416.05   74.98  423.19   73.84  462.27   54.44
  468.33   49.37  474.46   43.84  482.02      42   488.9   37.95  508.66   35.14
   515.7    37.2  524.91   42.38  535.64   43.84  549.71   53.84  555.12   54.33
  568.74   55.84  643.46   57.84  668.78   61.84  722.76   63.07     782   64.47
  872.17   68.54  901.47   73.84  912.01   83.84  925.22   85.84 1144.25   85.84
#Mann= 3 ,-1 , 0
       0     .06       0   280.7    .035       0  722.76     .05       0
Bank Sta=468.33,555.12
Exp/Cntr=0.3,0.1

Type RM Length L Ch R = 1 ,3220.   ,287.29,281.67,325.5
XS GIS Cut Line= 6
 6421816.5733454 2053955.4450443 6421303.6854602 2053787.2850788
 6421076.6695258 2053846.1410952 6420874.8775578 2053963.8530804
 6420689.9016147 2054073.1570296 6420446.0696553 2054224.5010174
#Sta/Elev= 30
       0   87.84  357.18   87.84  362.28   85.69  388.63   83.84  422.13   73.84
   574.3    74.3  589.33   73.84  672.67   63.84  721.64   61.42  781.37   60.99
  808.41   57.51  825.93   53.84  840.03   49.54  858.28   43.84     871      42
  878.22    37.8  903.36    34.9  923.07      42  933.83   43.84  948.66   53.84
  949.93   54.03 1007.19   59.84  1217.5   63.28 1244.21   63.84 1304.04   69.84
 1310.82   71.84 1332.54   73.84 1401.29   83.84 1420.33   85.84 1509.73   86.25
#Mann= 3 ,-1 , 0
       0     .05       0   574.3    .035       0  1217.5     .06       0
Bank Sta=840.03,949.93
Exp/Cntr=0.3,0.1

Type RM Length L Ch R = 1 ,2939.   ,109.06,109.27,98.98
XS GIS Cut Line= 5
  6421850.205348  2053795.693115 6421370.9494653 2053635.9411383
 6420992.5895431 2053585.4931582 6420706.7175923 2053728.4291099
 6420235.8696985 2053787.2850788
#Sta/Elev= 30
       0   87.49  266.92   86.67  304.99   81.11  326.61   73.84   387.1   73.84
  510.58   77.84  551.54   78.15  616.21   77.84  693.63   73.67  773.47   73.32
  863.74   75.51  886.89   75.92  968.65   73.84  983.07   69.84 1019.46   53.84
  1033.5   49.31 1050.53   43.84 1065.35      42 1072.97   37.62  1094.5    34.9
 1114.29      42 1125.47   43.84 1135.11   53.84 1140.83   54.25 1185.96   57.84
 1307.19   60.09 1383.95   61.84 1439.25   65.84 1554.41   85.84 1681.02   87.13
#Mann= 3 ,-1 , 0
       0     .05       0  863.74    .035       0 1307.19     .06       0
Bank Sta=1033.5,1140.83
Exp/Cntr=0.3,0.1

Type RM Length L Ch R = 1 ,2830.   ,397.69,471.43,505.66
XS GIS Cut Line= 5
 6421883.8373505 2053703.2050961 6421337.3174628 2053535.0451307
 6420933.7335268 2053493.0051393 6420631.0455984 2053644.3491271
 6420193.8297072 2053694.7971073
#Sta/Elev= 30
       0    86.3  249.24   85.19  259.71   83.84  294.73   73.84   344.7   72.51
  478.23   77.51  581.64   79.84  661.09   80.06  765.06   78.65  942.67   79.42
  972.62   77.76 1031.55   73.84 1055.67   69.84 1103.94   53.84 1126.53   47.65
 1138.26   43.84 1151.32      42 1158.91    37.5 1183.13    34.9 1188.88      37
 1195.55      42 1206.24   43.84 1230.26   52.83 1236.34   54.27 1282.96   57.84
 1360.13   59.85 1431.77   61.84 1476.11   65.84 1593.73   85.84 1756.11   87.63
#Mann= 3 ,-1 , 0
       0     .05       0  972.62    .035       0 1360.13     .06       0
Bank Sta=1126.53,1230.26
Exp/Cntr=0.3,0.1

Type RM Length L Ch R = 1 ,2358.   ,103.59,92.62,89.23
XS GIS Cut Line= 5
 6422001.5493358 2053291.2132186 6421143.9334836 2053106.2372282
 6420816.0215888 2053165.0932445 6420370.3976614 2053148.2772196
 6420185.4217184 2053148.2772196
#Sta/Elev= 30
       0   84.01  128.06   79.84  146.57   73.84  193.09   73.84  298.79   62.65
  387.57   57.84  462.39   51.84  545.86   51.84   849.9   79.84 1111.41   79.57
 1197.87   71.42 1242.09   65.84 1384.42   54.33 1388.86   53.84  1405.9   43.84
 1418.87      42 1424.33    37.5 1444.74    34.8 1466.68   43.84 1476.03   51.83
  1478.4   53.84 1493.38   55.84 1546.04   57.62 1590.76   63.84 1631.35   71.84
 1639.27   73.84 1661.44   83.84 1672.04   85.84 1709.67   87.84 1841.41   87.78
#Mann= 3 ,-1 , 0
       0     .06       0 1197.87    .035       0 1546.04     .05       0
Bank Sta=1384.42,1476.03
Exp/Cntr=0.3,0.1

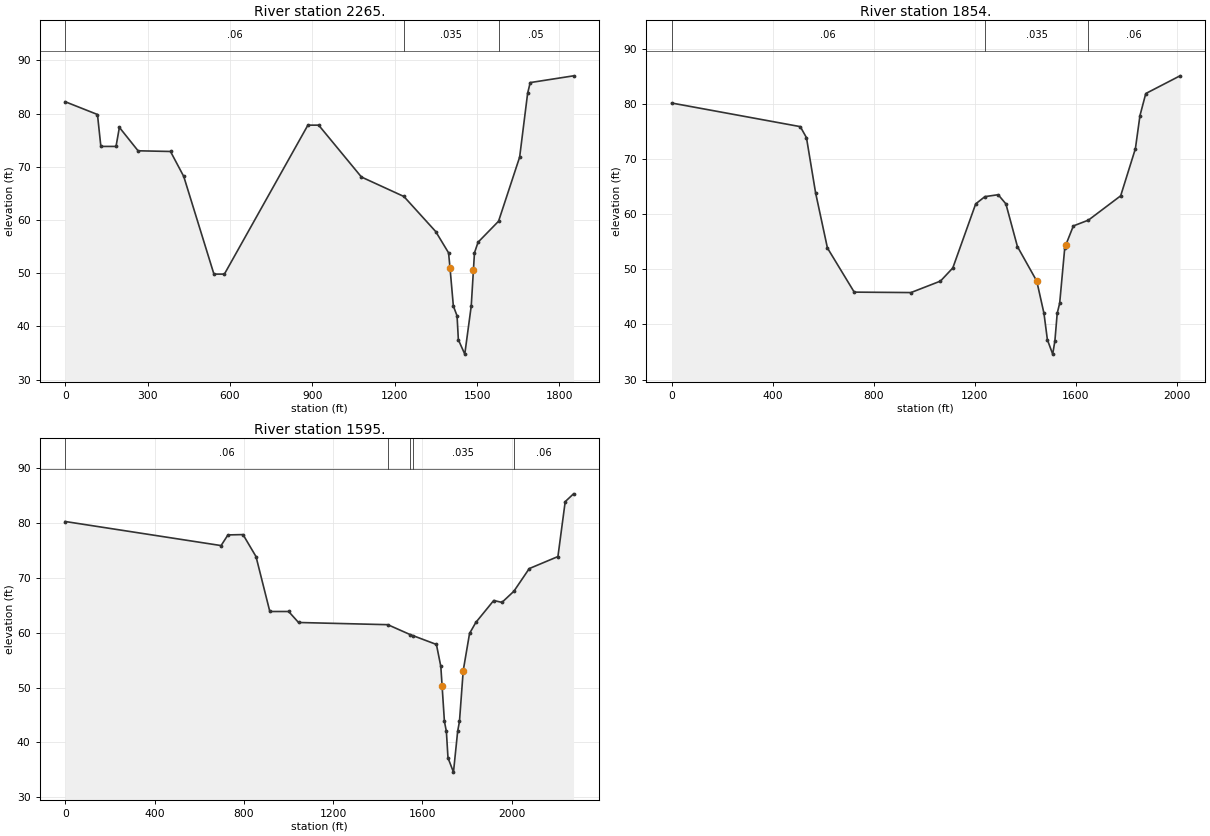
Type RM Length L Ch R = 1 ,2265.   ,411.11,411.57,375.33
XS GIS Cut Line= 5
 6422018.3653134 2053207.1332359 6421110.3015284 2053005.3412679
 6420706.7175923 2053064.1972369 6420479.7016579 2053064.1972369
 6420193.8297072 2053047.3812592
#Sta/Elev= 30
       0   82.24   117.5   79.84  129.87   73.84  185.08   73.84  197.33   77.42
  265.39   73.02  383.52   72.89  431.73    68.2  541.69   49.84   579.8   49.84
  883.91   77.84  923.15   77.84 1078.96   68.09 1233.65   64.43 1349.47   57.84
 1396.29   53.84 1401.68   50.94 1413.73   43.84  1427.2      42 1431.98    37.5
 1455.34    34.8 1478.85   43.84 1486.94   50.69 1490.62   53.84  1503.8   55.84
 1578.37   59.78 1655.21   71.84 1684.27   83.84 1693.68   85.84 1851.45   87.11
#Mann= 3 ,-1 , 0
       0     .06       0 1233.65    .035       0 1578.37     .05       0
Bank Sta=1401.68,1486.94
Exp/Cntr=0.3,0.1

Type RM Length L Ch R = 1 ,1854.   ,227.51,258.79,268.52
XS GIS Cut Line= 5
 6422192.0691175 2052963.7118541 6421280.1430916 2052707.6981328
 6420863.1063735 2052687.5189123 6420627.6824029 2052680.7925213
 6420237.9717194 2052814.0593095
#Sta/Elev= 30
       0   80.12   509.1   75.84  533.55   73.84  569.68   63.84  616.54   53.84
  722.57   45.84  947.18   45.76  1063.9   47.84 1112.78   50.22 1203.43   61.84
 1239.84   63.15  1292.4    63.5 1322.94   61.84 1368.57    54.1 1445.12   47.84
 1473.63      42 1487.22    37.2  1508.2    34.6  1516.9      37 1526.04      42
 1535.84   43.84 1555.87   53.84  1560.2    54.4 1589.92   57.84 1649.54   58.89
 1777.26    63.3 1835.51   71.84 1853.62   77.84  1876.6   81.84 2012.09   85.05
#Mann= 3 ,-1 , 0
       0     .06       0 1239.84    .035       0 1649.54     .06       0
Bank Sta=1445.12,1560.2
Exp/Cntr=0.3,0.1

Type RM Length L Ch R = 1 ,1595.   ,601.62,1595.1,597.12
XS GIS Cut Line= 6
 6422369.1971783 2052943.6596315 6421588.0439919   2052573.50648
 6421098.3621653 2052514.3141536  6420657.110411  2052417.454009
 6420517.2012974 2052460.5029779 6420275.0509832 2052670.3666247
#Sta/Elev= 30
       0   80.22  698.06   75.84  728.81   77.78  796.33   77.84   854.5   73.84
  916.37   63.84 1000.66   63.84 1044.95   61.84 1444.73   61.44 1544.12   59.65
 1555.94   59.47 1662.48   57.84 1682.15   53.84 1687.87    50.3 1698.27   43.84
 1707.09      42 1714.27    37.2 1738.86    34.6 1757.49      42 1765.68   43.84
 1782.52   53.09 1810.81   59.84  1838.8   61.84 1919.01   65.84 1956.07    65.5
 2009.48   67.53 2078.08   71.65 2206.63   73.84 2239.24   83.84 2276.51   85.26
#Mann= 5 ,-1 , 0
       0     .06       0 1444.73    .035       0 1544.12     .05       0
 1555.94    .035       0 2009.48     .06       0
Bank Sta=1687.87,1782.52
Exp/Cntr=0.3,0.1

River Reach=Baxter River    ,Lower Reach

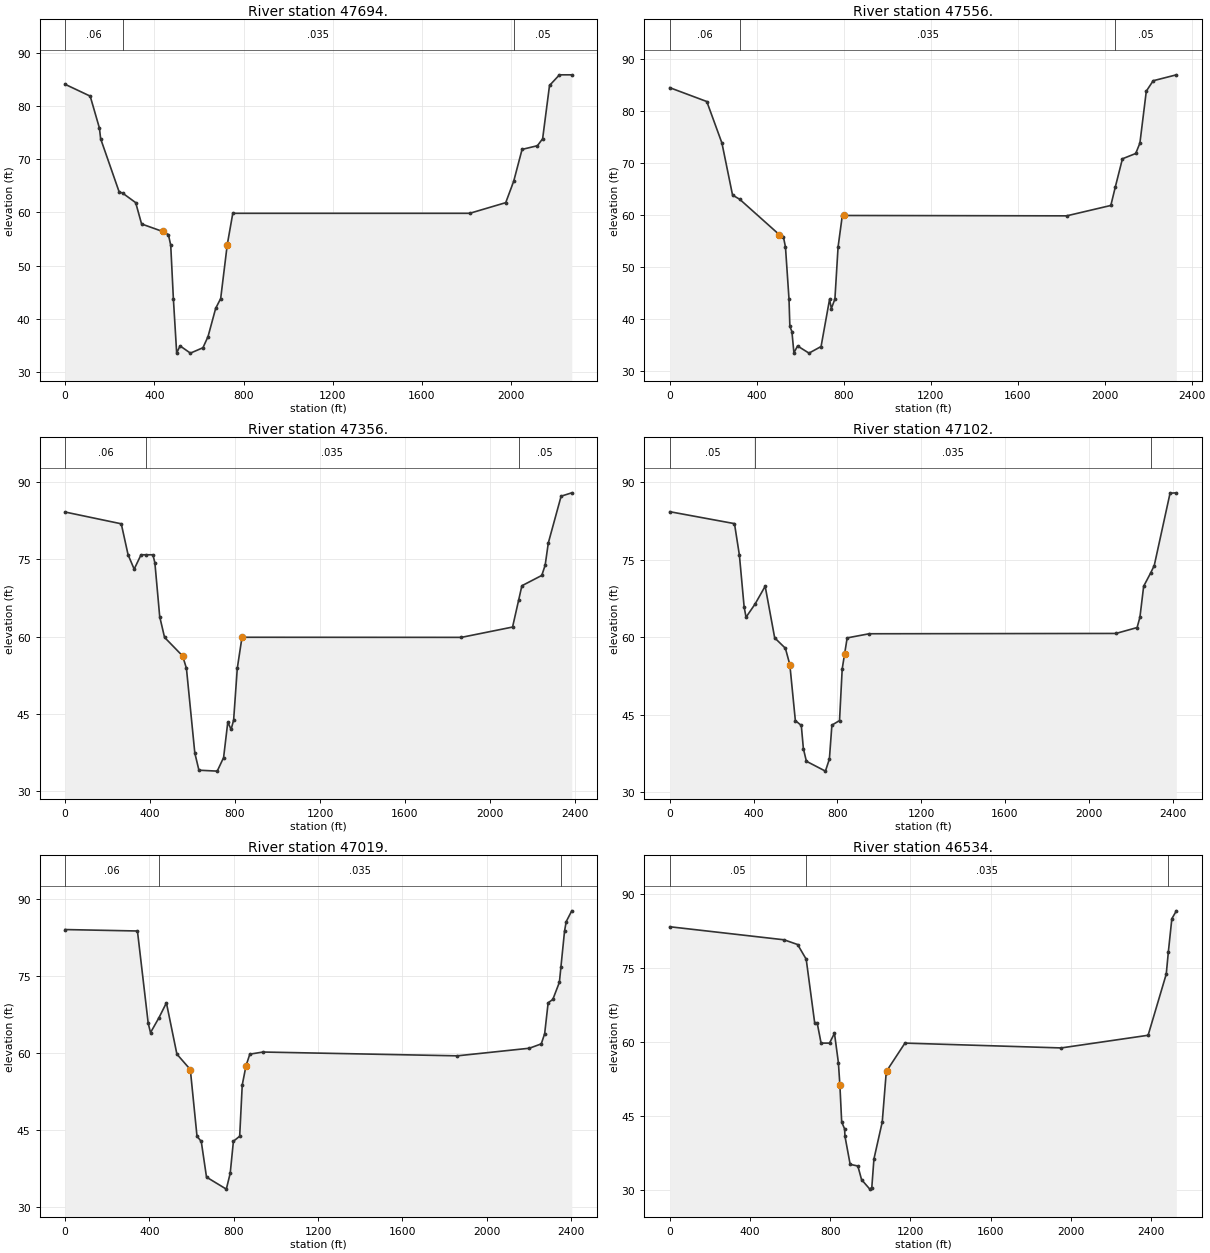
Type RM Length L Ch R = 1 ,47694.  ,157.08,138.01,115.25
XS GIS Cut Line= 5
 6421184.4600559 2050695.4960081 6421130.6488802 2051045.2687211
 6421017.6453781 2051443.4715065 6420377.2922312 2052487.4085894
 6420221.2397601  2052718.796697
#Sta/Elev= 30
       0   84.06   112.4   81.84   153.8   75.84  159.25   73.84   242.4   63.84
  257.29   63.65  316.39   61.84  342.82   57.84  437.24   56.43   463.1   55.84
  473.52   53.84  485.34   43.84  500.14   33.61  515.31   34.95  561.66   33.59
  617.94    34.6  640.78    36.7  675.05      42  697.49   43.84  726.89   53.93
   751.8   59.84 1813.96   59.84 1975.51   61.84 2011.29   65.86 2048.83   71.84
 2117.59   72.53 2141.02   73.84 2171.88   83.84 2216.45   85.84 2271.59   85.84
#Mann= 3 ,-1 , 0
       0     .06       0  257.29    .035       0 2011.29     .05       0
Bank Sta=437.24,726.89
Exp/Cntr=0.3,0.1

Type RM Length L Ch R = 1 ,47556.  ,188.27,200.04,182.63
XS GIS Cut Line= 5
 6421033.7887356 2050630.9225784 6420963.8342024 2051131.3666117
 6420920.7852335 2051384.2791801 6420242.7642683 2052600.4120442
  6420143.381727 2052744.6933309
#Sta/Elev= 30
       0   84.51   170.5   81.84  240.09   73.84  288.82   63.84  321.97   63.02
  503.05   56.25  522.49   55.84  532.18   53.84   548.4   43.84  552.39   38.55
  561.81   37.57  571.01   33.47  587.71    34.8  640.31   33.42  695.86   34.69
  734.97   43.79  743.14      42  759.52   43.84  774.03   53.84  793.31   59.84
  802.17   59.91 1824.94   59.84 2028.16   61.84 2048.34   65.33 2081.48   70.82
 2142.51   71.84 2161.82   73.84 2191.25   83.84 2222.82   85.84 2329.43   86.98
#Mann= 3 ,-1 , 0
       0     .06       0  321.97    .035       0 2048.34     .05       0
Bank Sta=503.05,802.17
Exp/Cntr=0.3,0.1

Type RM Length L Ch R = 1 ,47356.  ,211.15,254.47,293.61
XS GIS Cut Line= 6
 6420842.7590216 2050573.7481598 6420775.4950165 2051165.6712344
 6420681.3254472 2051441.4535986 6420479.5334792 2051898.8487103
 6420170.1191598 2052416.7813888 6419901.0631867 2052706.0165351
#Sta/Elev= 30
       0   84.12  264.36   81.84  296.46   75.84  325.14   73.06  357.39   75.84
  378.46   75.84  413.35   75.84  422.63   74.28  445.42   63.84  468.13   59.84
  553.43   56.23  571.18   53.84  610.69   37.43  629.99   34.11   716.2   33.93
  746.18   36.56   765.9   43.43  781.56      42  793.41   43.84  810.59   53.84
  832.77   59.86 1865.78   59.84 2106.71   61.84 2135.66    67.1 2150.59   69.84
 2244.34   71.84 2260.29   73.84 2275.09   78.14 2335.37   87.19 2385.43   87.84
#Mann= 3 ,-1 , 0
       0     .06       0  378.46    .035       0 2135.66     .05       0
Bank Sta=553.43,832.77
Exp/Cntr=0.3,0.1

Type RM Length L Ch R = 1 ,47102.  ,82.86,82.14,76.88
XS GIS Cut Line= 6
 6420721.6838408 2050560.2953777 6420566.9766574 2051064.7752741
  6420405.543083 2051407.8215961 6420170.1191598 2051851.7639257
 6419921.2424071 2052221.7158118 6419551.2904737  2052645.478921
#Sta/Elev= 30
       0   84.26  309.01   81.95   332.5   75.84  355.06   65.84  364.13   63.84
   407.4    66.4  455.47   69.84  500.91   59.84  551.91   57.84  573.15   54.67
   599.5   43.84  627.88    42.9  637.85    38.4  652.16   35.97  743.02   34.06
  761.92    36.4  773.85   42.96  810.29   43.84  823.08   53.84  834.65   56.78
  846.78   59.84  951.73   60.64 2129.45    60.7 2230.38   61.84 2243.86   63.84
 2261.69   69.84 2295.07   72.41 2312.19   73.84 2387.62   87.84 2417.71   87.91
#Mann= 3 ,-1 , 0
       0     .05       0   407.4    .035       0 2295.07     .06       0
Bank Sta=573.15,834.65
Exp/Cntr=0.3,0.1

Type RM Length L Ch R = 1 ,47019.  ,509.62,485.71,411.41
XS GIS Cut Line= 6
 6420634.2406626 2050519.9369841 6420486.2598702 2051058.0488831
 6420176.8455508 2051703.7831334 6420008.6855854 2051979.5654975
 6419739.6296596 2052322.6118195 6419490.7529069 2052598.3941363
#Sta/Elev= 30
       0   84.12  343.26   83.84  394.41   65.84   405.3   64.03  445.81   66.97
  480.71   69.84  530.51   59.84   594.2   56.84  625.94   43.84  646.19   42.82
  671.04   35.87  765.09   33.53  783.54   36.62  798.74   42.86  828.47   43.84
  840.67   53.84  858.71   57.59  876.68   59.84  939.86   60.25 1861.47   59.51
 2203.31   60.99 2259.95   61.84 2276.08   63.84 2292.52   69.84 2314.85   70.51
  2345.9   73.84  2353.4    76.9 2370.43   83.84  2378.3   85.67 2404.61   87.77
#Mann= 3 ,-1 , 0
       0     .06       0  445.81    .035       0  2353.4     .05       0
Bank Sta=594.2,858.71
Exp/Cntr=0.3,0.1

Type RM Length L Ch R = 1 ,46534.  ,45.43,52.85,56.5
XS GIS Cut Line= 6
 6420177.1145989 2050176.0834706 6420082.9450296 2050586.3937977
  6419847.521059 2051467.5520186  6419705.997657 2052053.5558464
 6419564.7432558  2052497.498176 6419484.0265159 2052591.6677453
#Sta/Elev= 30
       0   83.45  570.23    80.8  637.64   79.84  680.43   76.86  723.04   63.84
   735.6   63.84  754.61   59.84  796.69   59.84  821.32   61.84  840.98   55.84
  848.43   51.25  857.27   43.84  871.81   42.43  873.72   40.92  899.55   35.24
  937.89    34.9  956.43   32.13  997.52   30.21 1007.45   30.51 1018.07   36.32
 1059.53   43.84 1079.29   53.84 1082.58   54.25 1172.73   59.84  1951.7   58.86
 2385.03   61.43 2475.45   73.84 2486.01   78.38 2503.37   85.08 2525.86   86.68
#Mann= 3 ,-1 , 0
       0     .05       0  680.43    .035       0 2486.01     .06       0
Bank Sta=848.43,1082.58
Exp/Cntr=0.3,0.1

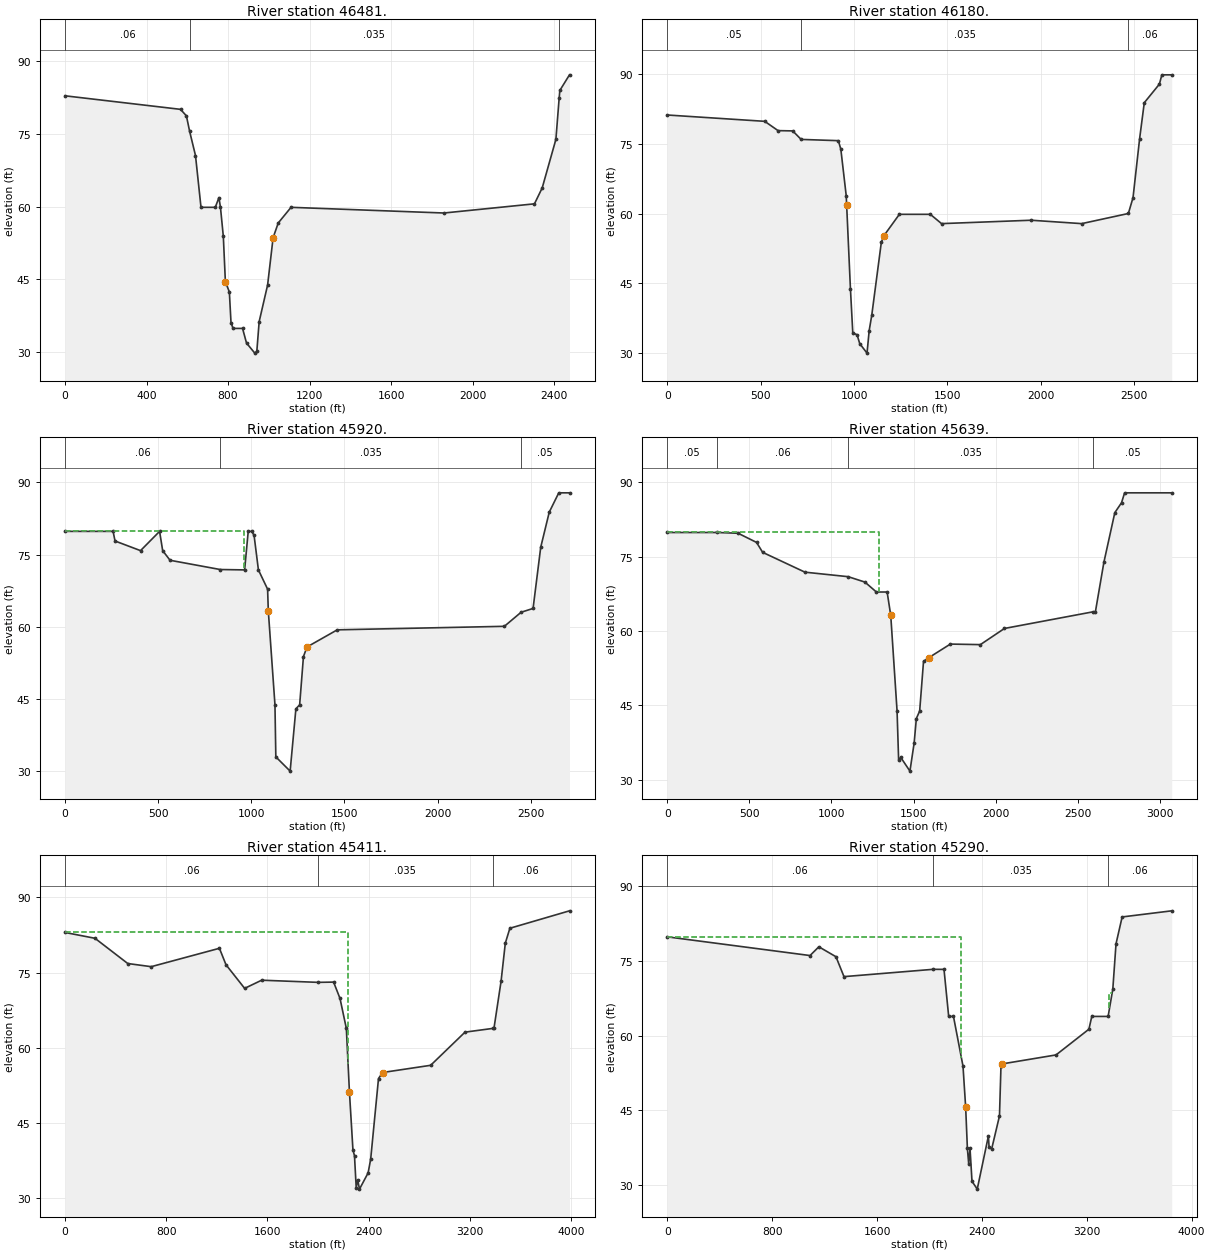
Type RM Length L Ch R = 1 ,46481.  ,322.97,300.51,288.13
XS GIS Cut Line= 6
 6420109.5815457 2050230.7018379 6419941.4215803 2050963.8793138
 6419813.6200084 2051354.0104204 6419712.7240481 2051824.8583142
 6419544.8331307 2052476.5118113 6419450.6635614 2052604.3133832
#Sta/Elev= 30
       0   82.81  566.93   80.02  595.79   78.68  611.67   75.48  640.38   70.51
   667.4   59.84  737.51   59.84  755.38   61.84  762.91   59.84  776.99   53.84
  787.08   44.51  806.59    42.4  814.62    36.1  824.66    34.9  871.34    34.9
  890.75   31.89  931.35   29.81  941.34   30.16  952.85    36.3  994.29   43.84
 1021.34   53.59 1046.56   56.62 1109.28   59.84 1859.92   58.67 2304.04   60.56
    2342   63.84  2409.2   73.84 2425.14   82.29 2428.61   83.92 2475.96   87.13
#Mann= 3 ,-1 , 0
       0     .06       0  611.67    .035       0 2425.14     .05       0
Bank Sta=787.08,1021.34
Exp/Cntr=0.3,0.1

Type RM Length L Ch R = 1 ,46180.  ,272.51,260.8,234.04
XS GIS Cut Line= 4
  6419788.396042 2050047.4074926 6419594.9166842  2051078.469319
 6419263.6276303  2052327.902325 6419157.7961715 2052670.7029347
#Sta/Elev= 30
       0    81.2  521.74   79.84  593.11   77.84   671.5   77.78  716.64   75.95
  915.77   75.68  929.14   73.84  957.99   63.84  960.33   61.79   980.5   43.84
  993.16   34.32 1015.99   33.95 1030.33   32.03 1069.34   29.99 1080.89   34.85
 1094.53    38.1 1145.98   53.84 1160.22   55.27  1242.4   59.84 1408.12   59.84
 1468.29   57.84 1948.09   58.57 2218.38   57.84 2468.27   60.02  2493.2   63.43
 2528.53   76.12 2553.42   83.84 2634.34   87.84 2647.54   89.84 2700.43   89.84
#Mann= 3 ,-1 , 0
       0     .05       0  716.64    .035       0 2468.27     .06       0
Bank Sta=960.33,1160.22
Exp/Cntr=0.3,0.1

Type RM Length L Ch R = 1 ,45920.  ,250.93,280.31,313.43
XS GIS Cut Line= 5
 6419721.1320369 2049929.6955073 6419410.0361197 2050560.2953777
 6419309.1401121 2051224.5272508  6419183.020138 2051779.4551273
 6418871.9242208 2052477.3189555
#Sta/Elev= 30
       0   79.84  258.04   79.84  268.54   77.84  405.42   75.84   507.7   79.84
  524.26   75.84  563.85   73.84  833.05   71.92  964.15   71.84   983.5   79.84
 1001.95   79.84 1014.85   79.03 1038.18   71.84 1087.53   67.84 1091.28   63.34
 1127.02   43.84 1131.69   33.03 1208.51   30.07 1239.39      43 1259.61   43.84
 1279.91   53.84 1298.97   55.84 1461.41    59.4 2358.49   60.13 2448.39   63.05
 2512.62   63.84 2553.71   76.55 2599.58   83.84 2650.59   87.84 2708.16   87.84
#Mann= 3 ,-1 , 0
       0     .06       0  833.05    .035       0 2448.39     .05       0
#XS Ineff= 1 ,-1
       0  959.21   79.84
Permanent Ineff=
       F
Bank Sta=1091.28,1298.97
Exp/Cntr=0.3,0.1

Type RM Length L Ch R = 1 ,45639.  ,229.21,228.25,215.91
XS GIS Cut Line= 6
 6419729.5400257 2049702.6795729 6419359.5881396 2050165.1194779
 6419098.9401552 2050778.9033234 6419040.0841863 2051115.2232543
  6418863.516232 2051569.2551705 6418678.5402889 2052536.1749718
#Sta/Elev= 30
       0   79.84  301.97   79.84  431.23   79.69   543.9   77.84  580.83   75.84
   838.6   71.84 1101.74   70.93  1203.7   69.84 1273.48   67.84 1338.98   67.84
 1360.94   63.13 1399.43   43.84 1408.89   34.02 1422.21   34.47 1477.81   31.72
 1503.48    37.4  1516.9   42.33 1537.07   43.84 1560.54   53.84 1590.89   54.56
 1724.03   57.34 1906.83   57.23 2053.42   60.49 2591.92   63.84  2607.2   63.84
 2658.93   73.84 2725.41   83.84 2766.29   85.84 2785.05   87.84 3072.09   87.84
#Mann= 4 ,-1 , 0
       0     .05       0  301.97     .06       0 1101.74    .035       0
 2591.92     .05       0
#XS Ineff= 1 ,-1
       0 1292.18   79.84
Permanent Ineff=
       F
Bank Sta=1360.94,1590.89
Exp/Cntr=0.3,0.1

Type RM Length L Ch R = 1 ,45411.  ,111.19,121.08,110.37
XS GIS Cut Line= 6
 6419670.6398938 2048731.0497263 6419168.9735946  2049743.847714
 6419047.0796254 2050108.8195129 6418778.0236996 2051178.3168723
  6418542.599729 2052126.7390983 6418455.1565508 2052510.1438139
#Sta/Elev= 30
       0      83  236.64   81.84  496.12    76.8   681.3   76.17 1220.72   79.84
 1272.56   76.56 1420.03   71.84 1554.57   73.47 1999.99   73.04  2123.4   73.09
 2173.97   69.83 2224.13   63.84 2248.73   51.08 2276.11   39.65 2288.58    38.4
 2302.14      32 2313.56   33.64 2327.94   31.76  2396.2      35 2416.41   37.73
 2478.35   53.84 2510.43   55.04 2890.56   56.48 3162.29    63.1 3380.07   63.84
 3391.05   63.84 3447.18   73.23 3480.91   80.87 3516.95   83.84  3988.3   87.32
#Mann= 3 ,-1 , 0
       0     .06       0 1999.99    .035       0 3380.07     .06       0
#XS Ineff= 1 ,-1
       0 2237.8983.00406
Permanent Ineff=
       F
Bank Sta=2248.73,2510.43
Exp/Cntr=0.3,0.1

Type RM Length L Ch R = 1 ,45290.  ,274.1,256.23,255.57
XS GIS Cut Line= 5
 6419578.4651333  2048682.823002 6419080.7116279 2049651.4244011
 6418724.0997263 2050898.6266844 6418448.4301597 2052167.0974919
  6418394.618984  2052321.804628
#Sta/Elev= 30
       0   79.84 1089.01   76.08 1156.34   77.84 1286.91   75.84 1348.02   71.84
 2027.72   73.31 2110.97    73.3 2146.65   63.84  2183.2   63.84 2255.88   53.84
 2276.17   45.59 2289.32    37.3 2299.36    34.2 2309.38    37.3 2324.41    30.7
 2364.53   29.12 2449.58    39.8 2454.58    37.6 2474.58    37.2 2534.14   43.84
  2545.5   53.84 2550.79   54.28 2965.46    56.1 3216.19   61.27 3238.34   63.84
 3362.69   63.84 3398.55   69.32 3423.05   78.44 3469.73   83.84 3848.07   85.07
#Mann= 3 ,-1 , 0
       0     .06       0 2027.72    .035       0 3362.69     .06       0
#XS Ineff= 2 ,-1
 3373.29 3394.0668.53513       0 2243.64   79.84
Permanent Ineff=
       F       F
Bank Sta=2276.17,2550.79
Exp/Cntr=0.3,0.1

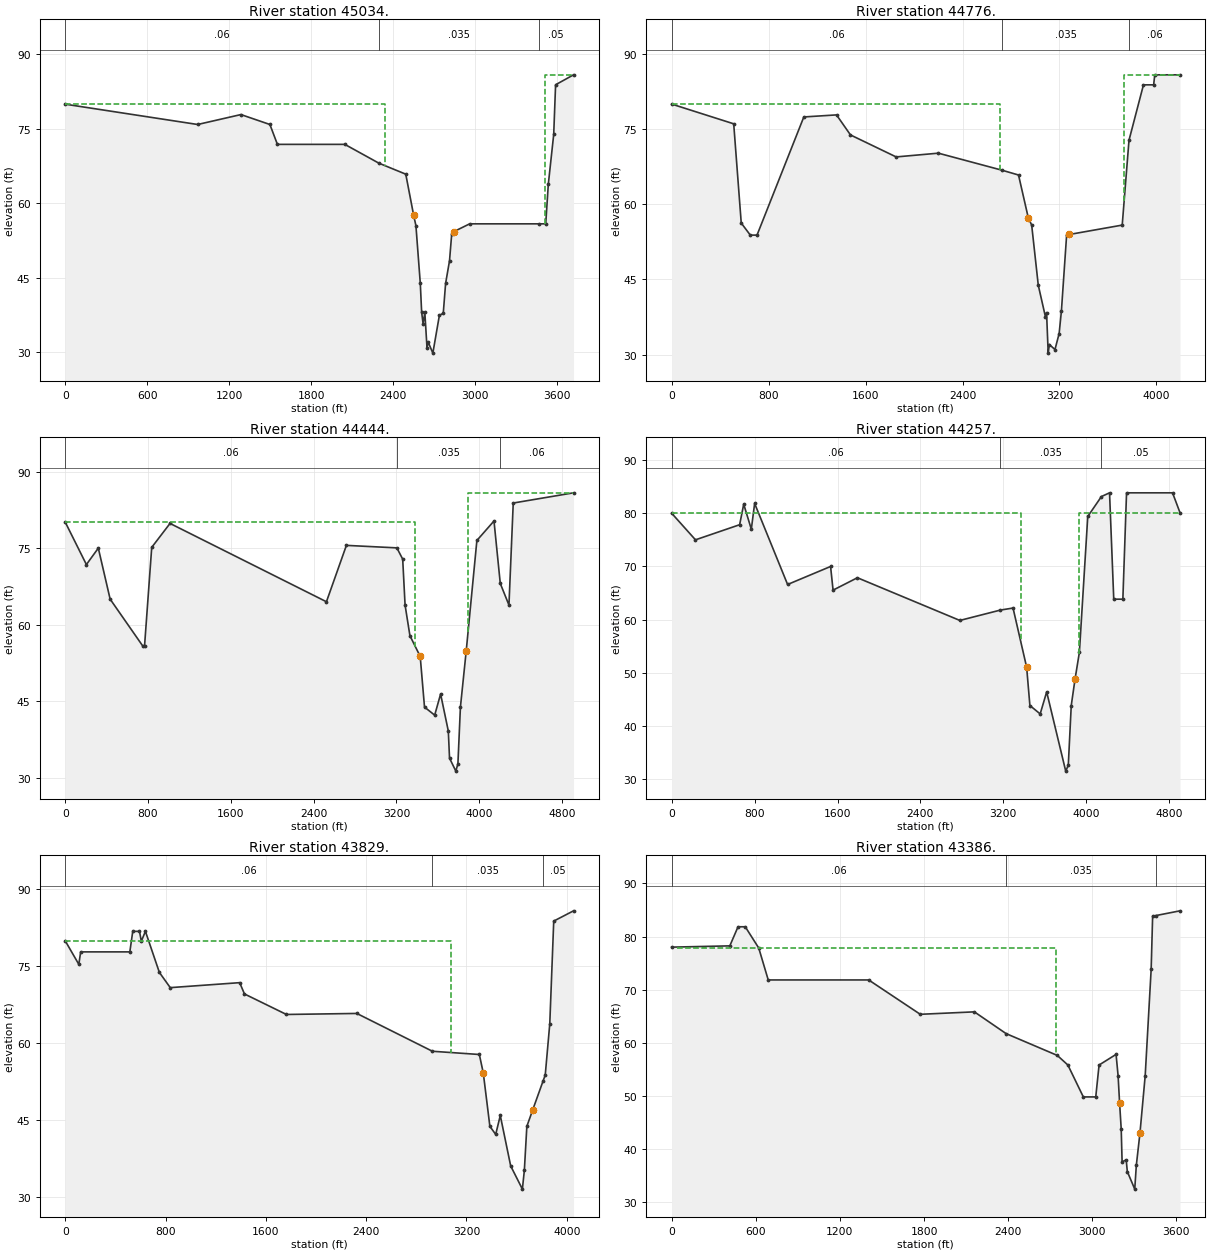
Type RM Length L Ch R = 1 ,45034.  ,282.79,257.86,241.35
XS GIS Cut Line= 5
 6419559.9675579 2048427.2198583 6418919.2780535 2049637.9716191
 6418487.4647081 2050661.9916188 6418459.0684926 2051002.7461094
 6418165.9214518 2051850.9567342
#Sta/Elev= 30
       0   79.93   969.5   75.84 1286.17   77.84 1498.23   75.84 1553.07   71.84
 2046.48   71.84 2296.12   68.05 2492.63   65.84  2550.5   57.54 2566.92   55.48
    2599   43.84 2608.83   38.04  2619.4   35.73 2632.17   38.02    2648   30.92
 2657.21      32 2690.82   29.81 2738.85   37.44 2767.05   37.82 2784.18   43.84
 2812.88   48.41 2828.98   53.84 2843.64   54.26 2960.33   55.84 3468.07   55.84
 3517.02   55.84 3536.07   63.84 3575.45   73.84 3589.23   83.84 3720.54   85.84
#Mann= 3 ,-1 , 0
       0     .06       0 2296.12    .035       0 3468.07     .05       0
#XS Ineff= 2 ,-1
 3512.78 3720.54   85.84       0 2337.5379.93319
Permanent Ineff=
       F       F
Bank Sta=2550.5,2843.64
Exp/Cntr=0.3,0.1

Type RM Length L Ch R = 1 ,44776.  ,335.08,331.39,355.75
XS GIS Cut Line= 6
 6419492.7035528 2048032.0439584 6419013.4476701 2048544.9318436
 6418651.9037255 2049276.4276744 6418279.5685582 2050420.8633937
 6418147.4238291 2051260.7152573 6417920.4078947 2051840.8671476
#Sta/Elev= 30
       0      80   511.9   76.06  574.06   56.25  648.81   53.84  704.26   53.84
 1090.47   77.43  1360.2   77.84 1475.49   73.84 1852.28   69.45 2200.47    70.2
 2725.53    66.8 2862.07   65.84 2942.31   57.34 2970.68   55.84  3025.1   43.84
 3084.01   37.55 3093.49   38.38 3106.96   30.28 3116.21      32  3162.9      31
 3197.25   34.19 3215.93   38.67 3259.04   53.84 3282.24   53.97 3717.74   55.84
 3773.75   72.78 3893.12   83.84 3977.12   83.84 3986.27   85.84 4194.57   85.84
#Mann= 3 ,-1 , 0
       0     .06       0 2725.53    .035       0 3773.75     .06       0
#XS Ineff= 2 ,-1
 3733.94 4194.57   85.84       0 2713.19      80
Permanent Ineff=
       F       F
Bank Sta=2942.31,3282.24
Exp/Cntr=0.3,0.1

Type RM Length L Ch R = 1 ,44444.  ,191.29,187.6,190.02
XS GIS Cut Line= 6
 6419557.0550794 2047642.5285289  6418744.391697 2048191.7959351
 6418525.3263129 2048428.1568878 6418265.1358144 2048948.5157323
 6418046.5278688 2049747.2755682 6417718.6159267 2051916.5391415
#Sta/Elev= 30
       0   80.11  204.65   71.78  319.73      75  434.03      65  748.38   55.84
  766.43   55.84   835.7   75.15 1012.49   79.84 2523.31   64.49 2716.12   75.54
 3203.58   75.05 3259.91   72.84 3282.83   63.84 3329.68   57.84 3429.03   53.77
 3470.57   43.84 3568.94   42.26 3625.99    46.4 3700.55   39.15 3712.25   33.84
 3773.14   31.29 3793.21   32.73 3817.45   43.84 3873.88   54.93 3976.44    76.5
 4141.73   80.32 4202.48   68.07 4286.28   63.84 4327.64   83.84 4910.04   85.84
#Mann= 3 ,-1 , 0
       0     .06       0 3203.58    .035       0 4202.48     .06       0
#XS Ineff= 2 ,-1
    3891 4908.64   85.84       0 3381.6980.11321
Permanent Ineff=
       F       F
Bank Sta=3429.03,3873.88
Exp/Cntr=0.3,0.1

Type RM Length L Ch R = 1 ,44257.  ,119.44,428.14,566.78
XS GIS Cut Line= 6
 6419274.0956071 2047477.1160819 6418834.7329641 2047738.3947009
 6418349.2157971 2048200.2039239 6418029.7118438 2048906.4757409
 6417802.6959094 2050075.1875103 6417567.2719388 2051815.6431338
#Sta/Elev= 30
       0      80  229.64      75  655.66   77.84  695.03    81.7  768.38      77
  800.43   81.84 1118.44    66.6 1533.08   69.99 1557.11   65.54 1791.89   67.87
 2780.24   59.84 3171.67   61.79 3293.47   62.17 3424.79   51.03 3456.03   43.84
  3555.2   42.26 3617.95    46.4 3801.71    31.5 3826.52    32.6 3855.05   43.84
  3891.9   48.84 3933.55   53.84 4014.33   79.39 4146.06   83.14 4224.48   83.84
 4265.14   63.84 4352.99   63.84 4388.53   83.84 4832.35   83.84 4904.25   80.11
#Mann= 3 ,-1 , 0
       0     .06       0 3171.67    .035       0 4146.06     .05       0
#XS Ineff= 2 ,-1
 3931.17 4904.2580.10934       0  3368.6      80
Permanent Ineff=
       F       F
Bank Sta=3424.79,3891.9
Exp/Cntr=0.3,0.1

Type RM Length L Ch R = 1 ,43829.  ,414.85,442.62,553.77
XS GIS Cut Line= 6
 6419101.7316473  2047475.014061   6418260.93182 2048231.7339056
 6418061.2418729 2048694.1738106 6417693.3919129 2050207.6134997
 6417220.4420456 2050554.4433929 6416968.2020974  2050659.543395
#Sta/Elev= 30
       0      80  108.54   75.41  123.35   77.84  515.48   77.84  538.75   81.84
  592.47   81.84  606.99   79.92  639.79   81.84  750.93   73.84  837.85   70.87
 1391.42   71.84 1429.65   69.64 1764.35   65.64 2325.82   65.84 2928.65   58.47
 3302.98   57.84 3334.48   54.23 3386.99   43.84  3433.5   42.26 3469.99   45.95
 3552.93   36.12 3646.22    31.6 3661.97   35.25 3681.89   43.84 3728.17   47.01
 3811.36   52.68 3828.57   53.84 3864.81   63.84 3896.35   83.84 4054.22   85.84
#Mann= 3 ,-1 , 0
       0     .06       0 2928.65    .035       0 3811.36     .05       0
#XS Ineff= 2 ,-1
 3988.09 4052.97               0 3073.36      80
Permanent Ineff=
       F       F
Bank Sta=3334.48,3728.17
Exp/Cntr=0.3,0.1

Type RM Length L Ch R = 1 ,43386.  ,462.42,634.69,621.98
XS GIS Cut Line= 6
 6419028.1616269 2047443.4840793 6418239.9118007 2048147.6539228
 6417766.9619333 2049524.4636282 6417535.7419571 2049850.2735494
   6417336.05201 2050028.9435245  6416894.632077 2050060.4735062
#Sta/Elev= 30
       0   78.01  414.74   78.25  473.23   81.84  524.92   81.84  621.09   77.84
  688.73   71.84 1405.14   71.84 1773.03   65.38    2159   65.84 2385.14   61.75
  2750.2   57.65 2825.95   55.84 2936.09   49.84 3024.69   49.84 3048.46   55.84
 3169.64   57.84 3184.06   53.84 3194.76    48.7 3206.24   43.84 3212.62   37.63
 3242.01      38 3249.85    35.8 3302.87    32.5  3314.2      37 3340.03   43.04
  3377.4   53.84 3419.95   73.84 3430.44   83.84 3451.88   83.94 3625.61   84.84
#Mann= 3 ,-1 , 0
       0     .06       0 2385.14    .035       0 3451.88     .05       0
#XS Ineff= 1 ,-1
   37.42 2743.48   77.84
Permanent Ineff=
       F
Bank Sta=3194.76,3340.03
Exp/Cntr=0.3,0.1