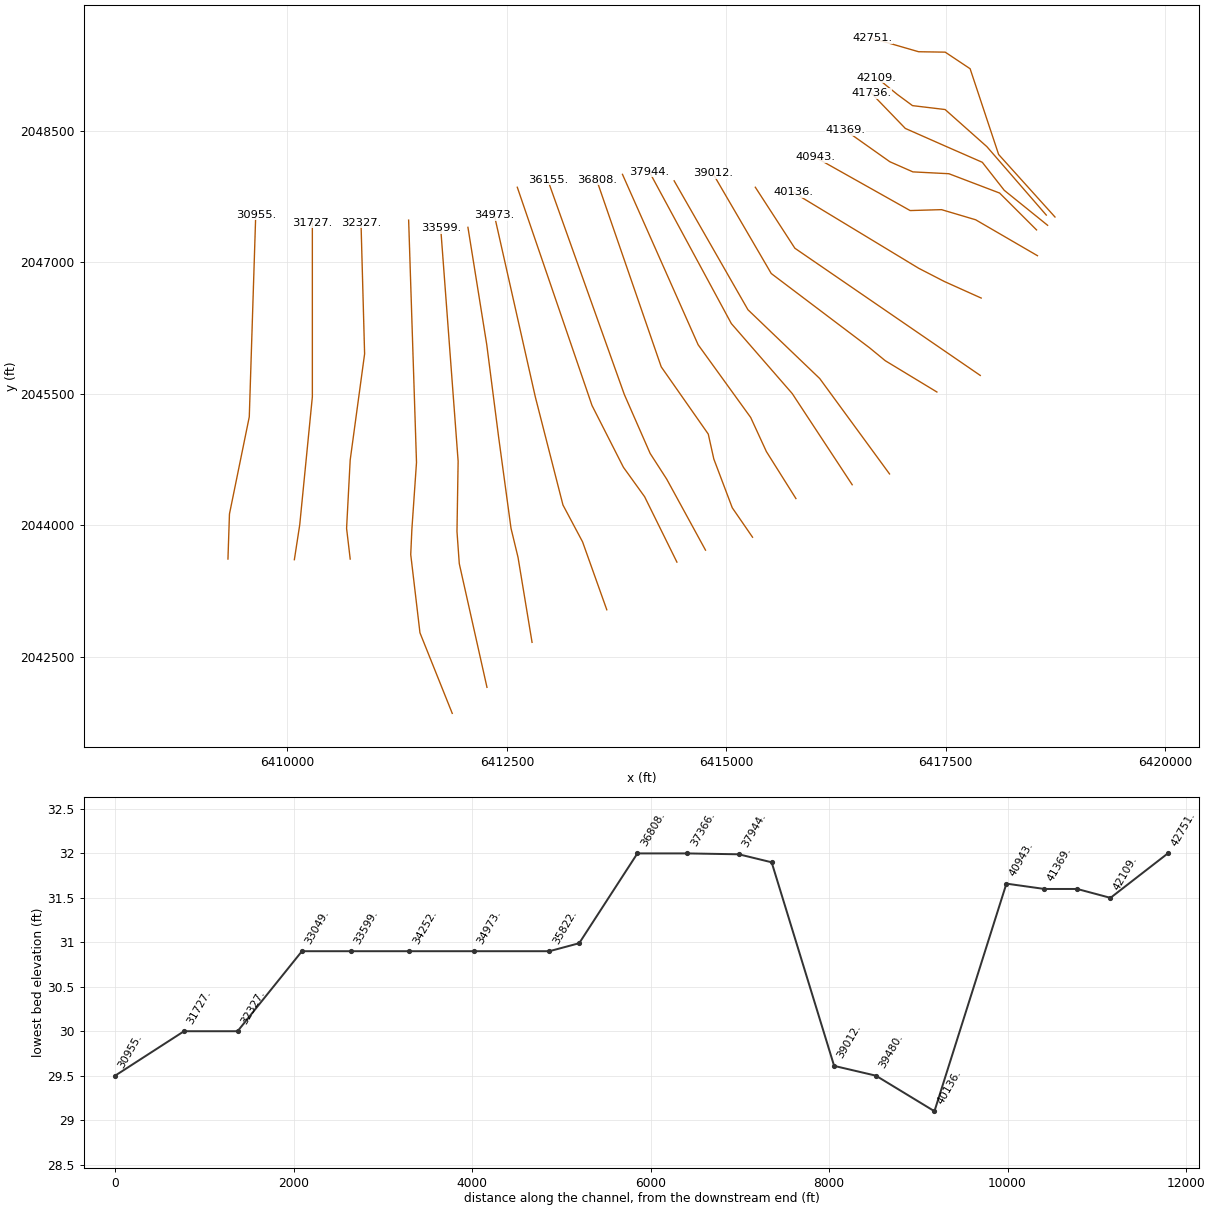
HEC-RAS study Baxter.prj: Baxter River GIS Example

--- Baxter.g01 (geometry) --- (continued)

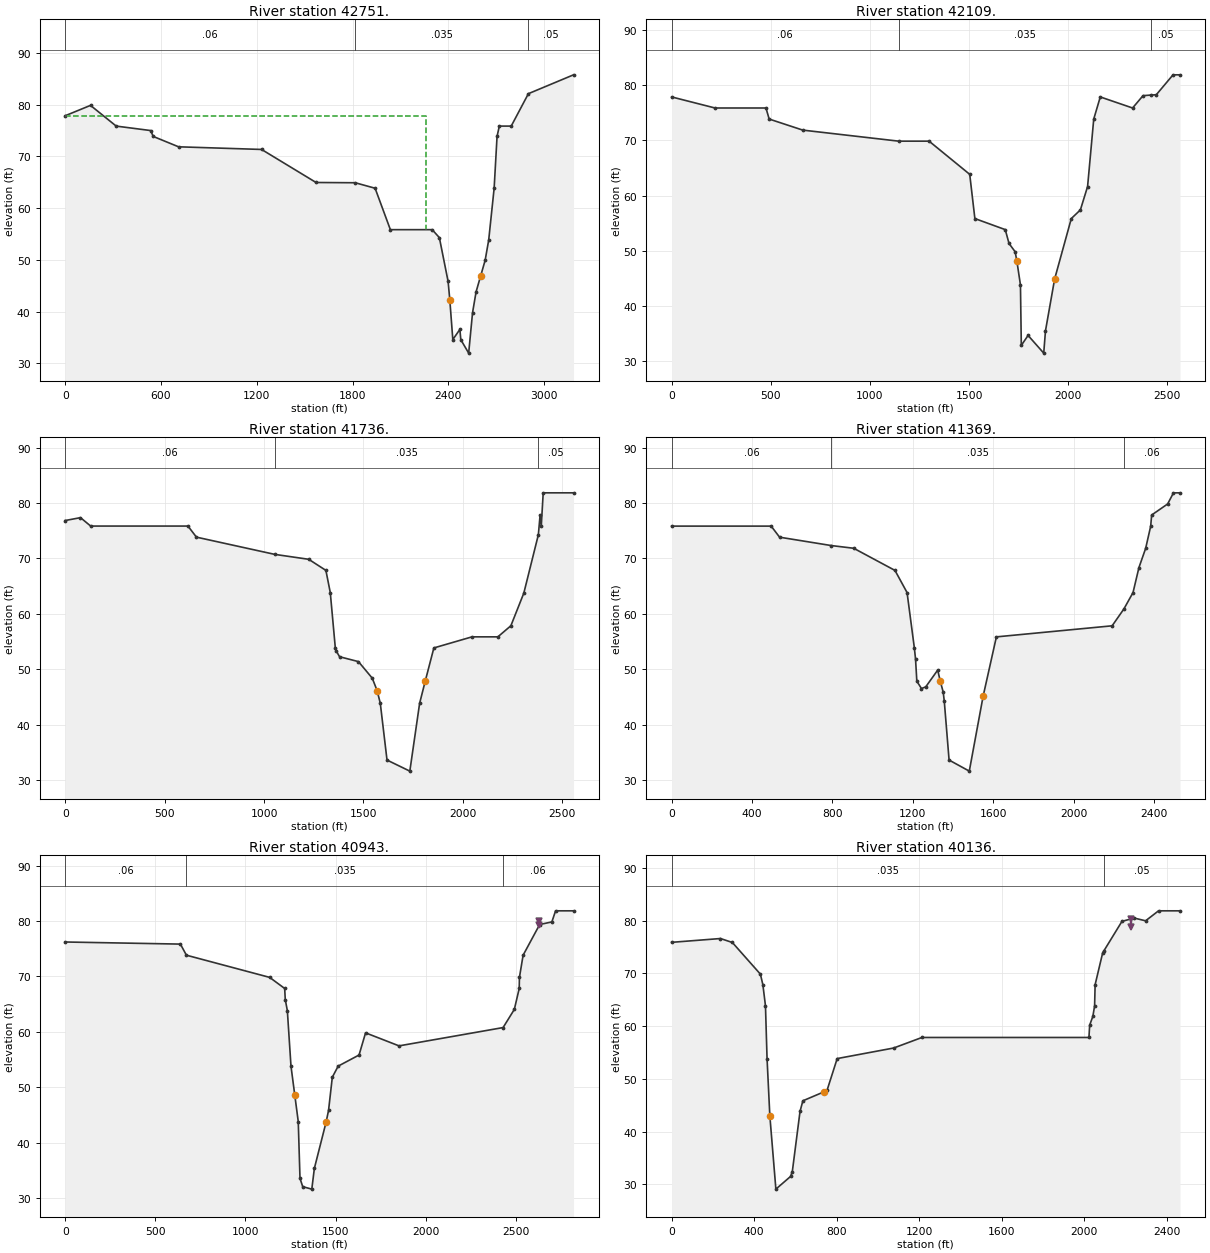
Type RM Length L Ch R = 1 ,42751.  ,688.21,642.75,621.09
XS GIS Cut Line= 6
  6418744.391697 2047517.0540524 6418102.2664965 2048230.6398683
 6417777.4718957 2049209.1637166 6417493.7019658 2049398.3436541
 6417190.7047079 2049403.0932234 6416663.4121482 2049555.9936099
#Sta/Elev= 30
       0   77.84  158.46   79.84  319.42   75.84  535.09   74.98  551.55   73.84
  710.17   71.84 1230.07   71.33 1571.26   64.95 1816.74    64.9 1941.13   63.84
 2036.78   55.84 2298.77   55.84 2343.69    54.3 2398.43   45.84 2408.96   42.33
  2427.9   34.62 2472.18   36.58 2477.97    34.6 2527.27      32  2551.5    39.8
 2573.71   43.84 2601.59   46.83 2630.43   49.92 2652.72   53.84 2686.81   63.84
 2705.01   73.84 2719.29   75.84 2793.73   75.84  2901.3    82.1 3184.08   85.74
#Mann= 3 ,-1 , 0
       0     .06       0 1816.74    .035       0  2901.3     .05       0
#XS Ineff= 1 ,-1
       0 2262.99   77.84
Permanent Ineff=
       F
Bank Sta=2408.96,2601.59
Exp/Cntr=0.3,0.1

Type RM Length L Ch R = 1 ,42109.  ,377.39,372.57,283.73
XS GIS Cut Line= 6
 6418644.9204513 2047539.3136146 6417968.4614228 2048319.8432665
 6417492.7100285 2048743.5593254 6417121.0292104 2048788.1610482
 6416950.0560738 2048914.5325093 6416712.1803766 2049107.8064837
#Sta/Elev= 30
       0   77.84  218.66   75.84  475.47   75.84  491.66   73.84  661.11   71.84
 1145.17   69.84 1298.19   69.84    1503   63.84    1529   55.84 1682.18   53.84
 1701.27   51.33 1731.97   49.84  1740.4   48.24 1758.81   43.84 1763.15    32.9
 1797.26    34.7 1876.22    31.5 1885.06   35.54 1931.17    44.9 2015.23   55.84
 2061.12   57.41 2097.39   61.64 2128.42   73.84 2161.39   77.84 2324.26   75.84
  2376.9   78.07 2416.94   78.18 2443.89   78.24 2528.25   81.84  2563.4   81.84
#Mann= 3 ,-1 , 0
       0     .06       0 1145.17    .035       0 2416.94     .05       0
Bank Sta=1740.4,1931.17
Exp/Cntr=0.3,0.1

Type RM Length L Ch R = 1 ,41736.  ,287.7,367.05,432.26
XS GIS Cut Line= 6
 6418660.3117143   2047422.46406 6418166.3418276 2047821.8440016
 6417916.4260874   2048141.43647 6417492.7100285 2048327.2768791
  6417039.259472  2048527.984466 6416652.7114287 2048929.3997345
#Sta/Elev= 30
       0   76.84   76.91   77.36  128.07   75.84  617.34   75.84  660.06   73.84
  1053.9   70.73 1224.79   69.84 1311.19   67.84 1333.25   63.84 1358.61   53.84
  1363.4   53.28 1379.98   52.25 1474.92   51.37 1544.41   48.38 1569.29   46.09
 1584.85   43.84 1618.61    33.6 1733.36    31.6 1782.62   43.84 1811.24    47.9
 1854.23   53.84 2046.02   55.84 2176.11   55.84 2241.57   57.84 2306.77   63.74
 2379.89   74.28 2388.59   77.84 2394.49   75.84 2404.24   81.84 2556.77   81.84
#Mann= 3 ,-1 , 0
       0     .06       0  1053.9    .035       0 2379.89     .05       0
Bank Sta=1569.29,1811.24
Exp/Cntr=0.3,0.1

Type RM Length L Ch R = 1 ,41369.  ,425.26,426.3,407.56
XS GIS Cut Line= 6
 6418534.1917402 2047369.9141063 6418113.7918266 2047790.3140199
 6417535.7419571 2048011.0239391 6417125.8520532 2048032.0439584
 6416863.1020953 2048147.6539228  6416358.622199 2048504.9938258
#Sta/Elev= 30
       0   75.84     495   75.84   536.9   73.84  793.95   72.33  905.69   71.84
 1111.02   67.84 1171.12   63.84 1207.39   53.84 1213.27   51.84 1219.68   47.84
 1242.79   46.51 1264.13   46.82  1323.5   49.84 1335.74   47.94 1351.06   45.84
 1356.33    44.2 1380.14    33.6 1480.71    31.6 1549.43   45.11  1615.5   55.84
 2191.38   57.84 2249.83   60.88 2295.26   63.84 2324.67   68.35 2358.28   71.84
 2383.23   75.84 2387.86   77.84 2467.55   79.84 2496.43   81.84 2528.99   81.85
#Mann= 3 ,-1 , 0
       0     .06       0  793.95    .035       0 2249.83     .06       0
Bank Sta=1335.74,1549.43
Exp/Cntr=0.3,0.1

Type RM Length L Ch R = 1 ,40943.  ,826.24,806.49,525.17
XS GIS Cut Line= 5
 6418544.7017499 2047075.6341667 6417840.5319064 2047485.5240707
 6417451.6619744 2047601.1340351 6417094.3220715 2047590.6240254
 6416011.7923057 2048200.2039239
#Sta/Elev= 30
       0   76.22  639.15   75.84   672.5   73.84 1134.23   69.84  1217.7   67.84
 1220.96   65.84 1232.53   63.84 1252.65   53.84 1273.64   48.64 1292.99   43.84
 1302.66    33.6 1317.89    32.1 1368.19   31.66 1382.38    35.4 1447.09   43.69
 1461.05   45.84    1482   51.84  1514.5   53.84 1630.27   55.84 1666.52   59.84
 1852.17   57.49 2429.48   60.79 2491.93   64.07 2518.97   67.84 2520.22   69.84
 2540.59   73.84 2632.38   79.37 2700.12   79.84 2720.74   81.84 2820.33   81.84
#Mann= 3 ,-1 , 0
       0     .06       0   672.5    .035       0 2429.48     .06       0
Levee=0,,,-1,2630.25,79.95625,,	380
Bank Sta=1273.64,1447.09
Exp/Cntr=0.3,0.1

Type RM Length L Ch R = 1 ,40136.  ,661.44,655.91,599.95
XS GIS Cut Line= 4
 6417903.5918697 2046592.1742424  6417484.132157 2046781.1770076
 6417190.7047079 2046932.6234269 6415759.5523575 2047800.8239823
#Sta/Elev= 30
       0   75.87  236.55   76.59  294.15   75.84  430.11   69.84  442.09   67.84
  454.69   63.84  462.37   53.84  475.83   43.01  505.14    29.1  576.25    31.5
  584.74    32.4  622.26   43.84  636.05   45.84  736.07    47.5  753.33   47.84
  802.34   53.84 1076.03   55.84 1213.27   57.84 2022.79   57.84 2026.26   60.17
 2041.79   61.84 2050.26   63.84 2052.71   67.84  2089.1   73.84 2096.25   74.32
 2182.76   79.84 2242.23   80.47  2297.4   79.95 2360.19   81.84 2464.19   81.84
#Mann= 2 ,-1 , 0
       0    .035       0 2096.25     .05       0
Levee=0,,,-1,2226.55,78.70036,,	380
Bank Sta=475.83,736.07
Exp/Cntr=0.3,0.1

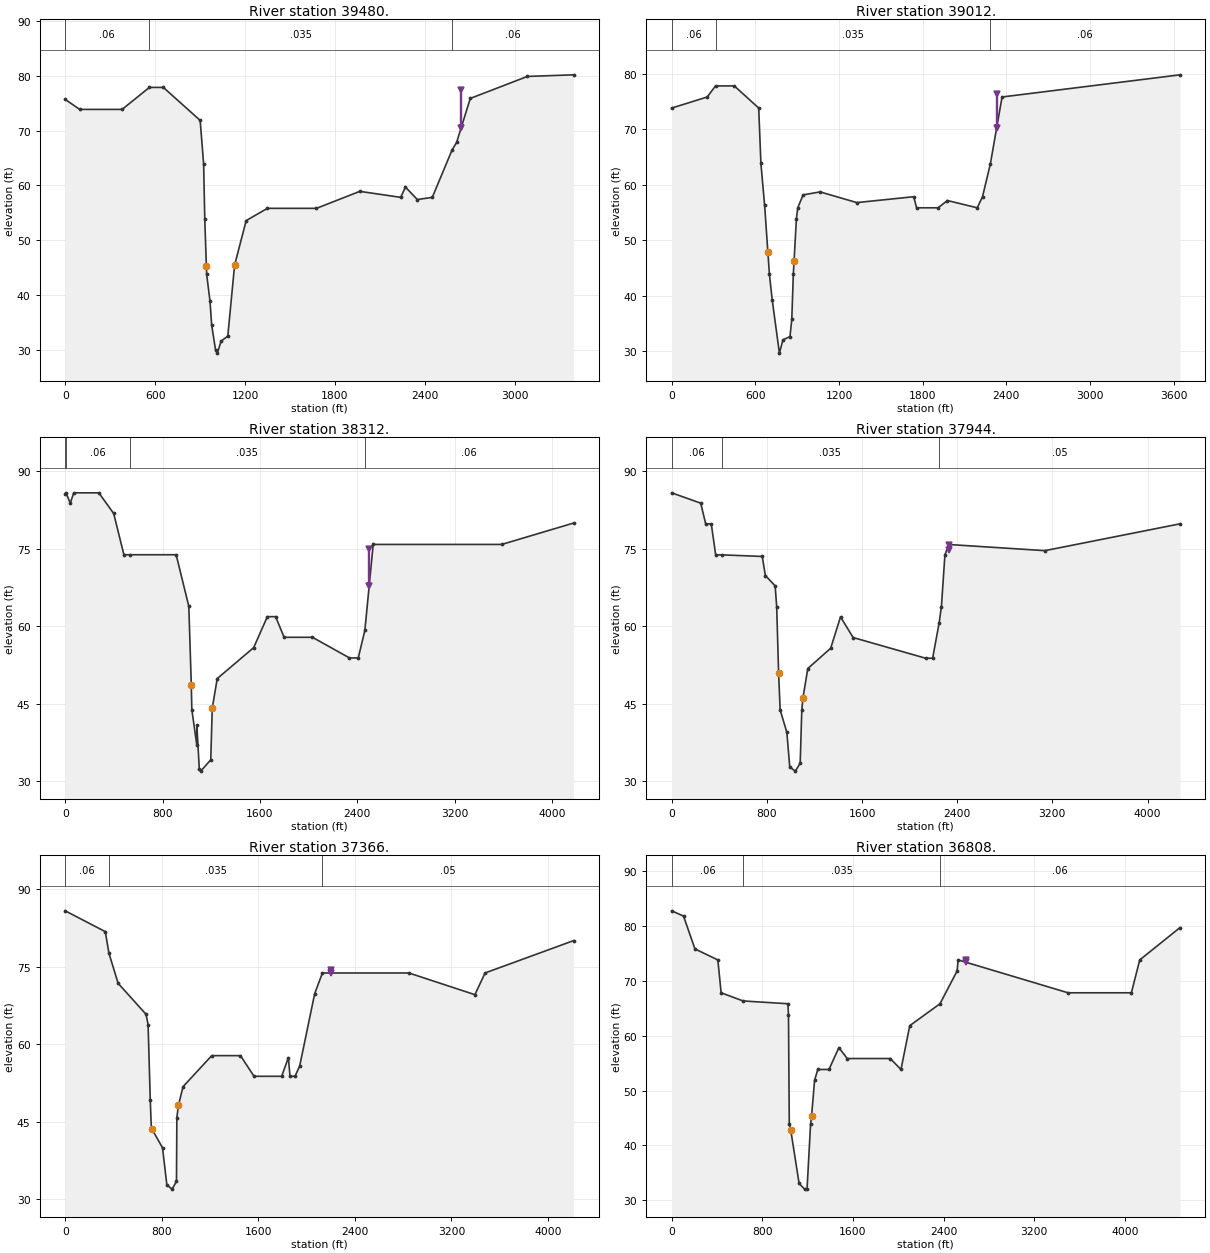
Type RM Length L Ch R = 1 ,39480.  ,474.01,468.09,436.4
XS GIS Cut Line= 3
 6417893.0819074 2045709.3344237 6415781.0439683 2047160.8173223
 6415330.6130551 2047856.6583672
#Sta/Elev= 30
       0   75.66   96.61   73.84  379.71   73.84  561.59   77.84  654.78   77.84
  900.46   71.84  923.73   63.84  931.22   53.84  941.88   45.31   943.7   43.84
  966.28   38.92  977.12   34.62 1003.42   30.02 1015.09    29.5  1040.2   31.68
 1084.75    32.6 1130.21   45.51 1207.42   53.61 1348.98   55.84  1676.3   55.84
 1965.59   58.93 2238.46   57.84 2270.31   59.71 2349.15   57.44  2449.3   57.84
 2580.91   66.44 2611.63   67.84 2702.79   75.84 3084.13   79.84 3391.62   80.13
#Mann= 3 ,-1 , 0
       0     .06       0  561.59    .035       0 2580.91     .06       0
Levee=0,,,-1,2642.34,77.38441,,	380
Bank Sta=941.88,1130.21
Exp/Cntr=0.3,0.1

Type RM Length L Ch R = 1 ,39012.  ,742.69,700.15,609.51
XS GIS Cut Line= 5
 6417399.1119734 2045520.1544863 6416810.5521416 2045877.4943892
 6416631.8821665 2046024.6343826 6415512.0072129 2046872.3175141
 6414847.1531781  2048014.308323
#Sta/Elev= 30
       0   73.84  254.94   75.84  314.61   77.84  449.27   77.84  624.32   73.84
     640   63.84  666.56   56.33  690.09   47.81  701.08   43.84  721.17    39.2
  772.72   29.61  798.12      32  848.65    32.6  861.46    35.7  872.52   43.84
  877.88   46.27  894.55   53.84  904.32   55.84  942.79   58.17 1064.65   58.71
 1327.75   56.78 1736.01   57.84 1756.62   55.84 1910.57   55.84 1978.27   57.15
 2191.68   55.84 2229.53   57.84 2285.94   63.78 2369.72   75.84 3645.96   79.84
#Mann= 3 ,-1 , 0
       0     .06       0  314.61    .035       0 2285.94     .06       0
Levee=0,,,-1,2330.43,76.28944,,	380
Bank Sta=690.09,877.88
Exp/Cntr=0.3,0.1

Type RM Length L Ch R = 1 ,38312.  ,374.38,367.97,323.69
XS GIS Cut Line= 4
  6416859.415654 2044585.2038341 6416064.3219057 2045673.7250315
 6415246.5330724 2046458.8286426 6414405.7332451 2047930.2283403
#Sta/Elev= 30
       0   85.65    7.24   85.79   41.85   83.84   70.01   85.84  276.11   85.84
   398.3   81.84  482.18   73.84     531   73.84  911.56   73.84 1015.52   63.84
 1035.88   48.65 1040.27   43.84 1080.99      37 1081.52    40.8 1101.68    32.3
 1113.67    31.9 1195.81    34.1 1208.17    44.1 1249.02   49.84 1548.48   55.84
 1660.85   61.84 1728.69   61.84 1798.53   57.84 2031.24   57.84 2335.57   53.84
 2407.72   53.84  2461.9   59.17 2530.41   75.84  3587.1   75.84 4176.32   79.98
#Mann= 4 ,-1 , 0
       0     .06       0    7.24     .06       0     531    .035       0
  2461.9     .06       0
Levee=0,,,-1,2497.03,75.01536,,	380
Bank Sta=1035.88,1208.17
Exp/Cntr=0.3,0.1

Type RM Length L Ch R = 1 ,37944.  ,606.16,578.05,519.9
XS GIS Cut Line= 5
 6416434.1628402 2044461.9290764 6415971.7229352   2045166.09892
 6415751.0129688 2045502.4188509 6415057.3531349 2046301.1786868
 6414121.9633152 2048035.3283424
#Sta/Elev= 30
       0   85.84  244.26   83.84  285.92   79.84  332.83   79.84  369.94   73.84
  418.97   73.84   761.4   73.53  787.53   69.84  869.79   67.84  882.67   63.84
  898.95      51  911.77   43.84  968.36   39.47  992.51    32.8 1038.87   31.99
  1080.3    33.5 1093.83   43.84 1103.96   46.21 1144.27   51.84 1336.67   55.77
 1419.25   61.84 1525.21   57.84 2134.18   53.84 2193.73   53.84 2248.61   60.72
 2267.59   63.84 2296.83   73.84 2331.18   75.84 3137.03   74.65 4272.96   79.84
#Mann= 3 ,-1 , 0
       0     .06       0  418.97    .035       0 2248.61     .05       0
Levee=0,,,-1,2330.57,74.77473,,	380
Bank Sta=898.95,1103.96
Exp/Cntr=0.3,0.1

Type RM Length L Ch R = 1 ,37366.  ,589.97,558.31,507.96
XS GIS Cut Line= 5
 6415793.0529601 2044304.2791207 6415456.7330292 2044840.2889987
 6415278.0630541 2045229.1589307 6414678.9932126 2046059.4487483
  6413817.173366 2048003.7983133
#Sta/Elev= 30
       0   85.87  332.34   81.84  362.04   77.68  438.32   71.84  669.63   65.84
  686.69   63.84  704.62   49.32  713.45   43.84  717.84   43.66  806.15      40
  842.34    32.8  885.71      32  921.86    33.5  924.98   45.84  938.07   48.23
  976.46   51.84 1214.05   57.84 1452.13   57.84 1564.35   53.84 1793.01   53.84
 1849.03   57.45 1862.29   53.84 1903.78   53.84 1942.65   55.84 2066.85   69.84
  2130.9   73.84 2847.47   73.84  3394.2   69.64 3478.39   73.84 4211.37    80.1
#Mann= 3 ,-1 , 0
       0     .06       0  362.04    .035       0  2130.9     .05       0
Levee=0,,,-1,2202.75,74.34217,,	380
Bank Sta=717.84,938.07
Exp/Cntr=0.3,0.1

Type RM Length L Ch R = 1 ,36808.  ,564.92,652.32,662.06
XS GIS Cut Line= 6
 6415299.0830734 2043862.8591877 6415067.8630973 2044199.1791186
 6414857.6631404  2044756.209016 6414794.6031771 2045039.9789459
  6414258.593299 2045807.2088001 6413522.8934265   2047940.73835
#Sta/Elev= 30
       0    82.8  104.68   81.84  205.51   75.84  407.57   73.84  436.54   67.84
  630.47   66.35  1026.1   65.84 1031.08   63.84 1038.18   43.84 1051.62   42.71
 1124.73   33.04 1172.84      32 1194.97      32 1226.01   43.84 1235.14    45.4
 1261.36   51.84 1289.37   53.84 1388.34   53.84 1475.88   57.83 1549.58   55.84
 1929.04   55.84 2024.06   53.84 2101.65   61.84 2368.46   65.84 2519.88   71.84
 2528.36   73.84 3498.69   67.84 4057.72   67.84 4131.58   73.84 4486.93   79.74
#Mann= 3 ,-1 , 0
       0     .06       0  630.47    .035       0 2368.46     .06       0
Levee=0,,,-1,2598.81,73.87553,,	380
Bank Sta=1051.62,1235.14
Exp/Cntr=0.3,0.1

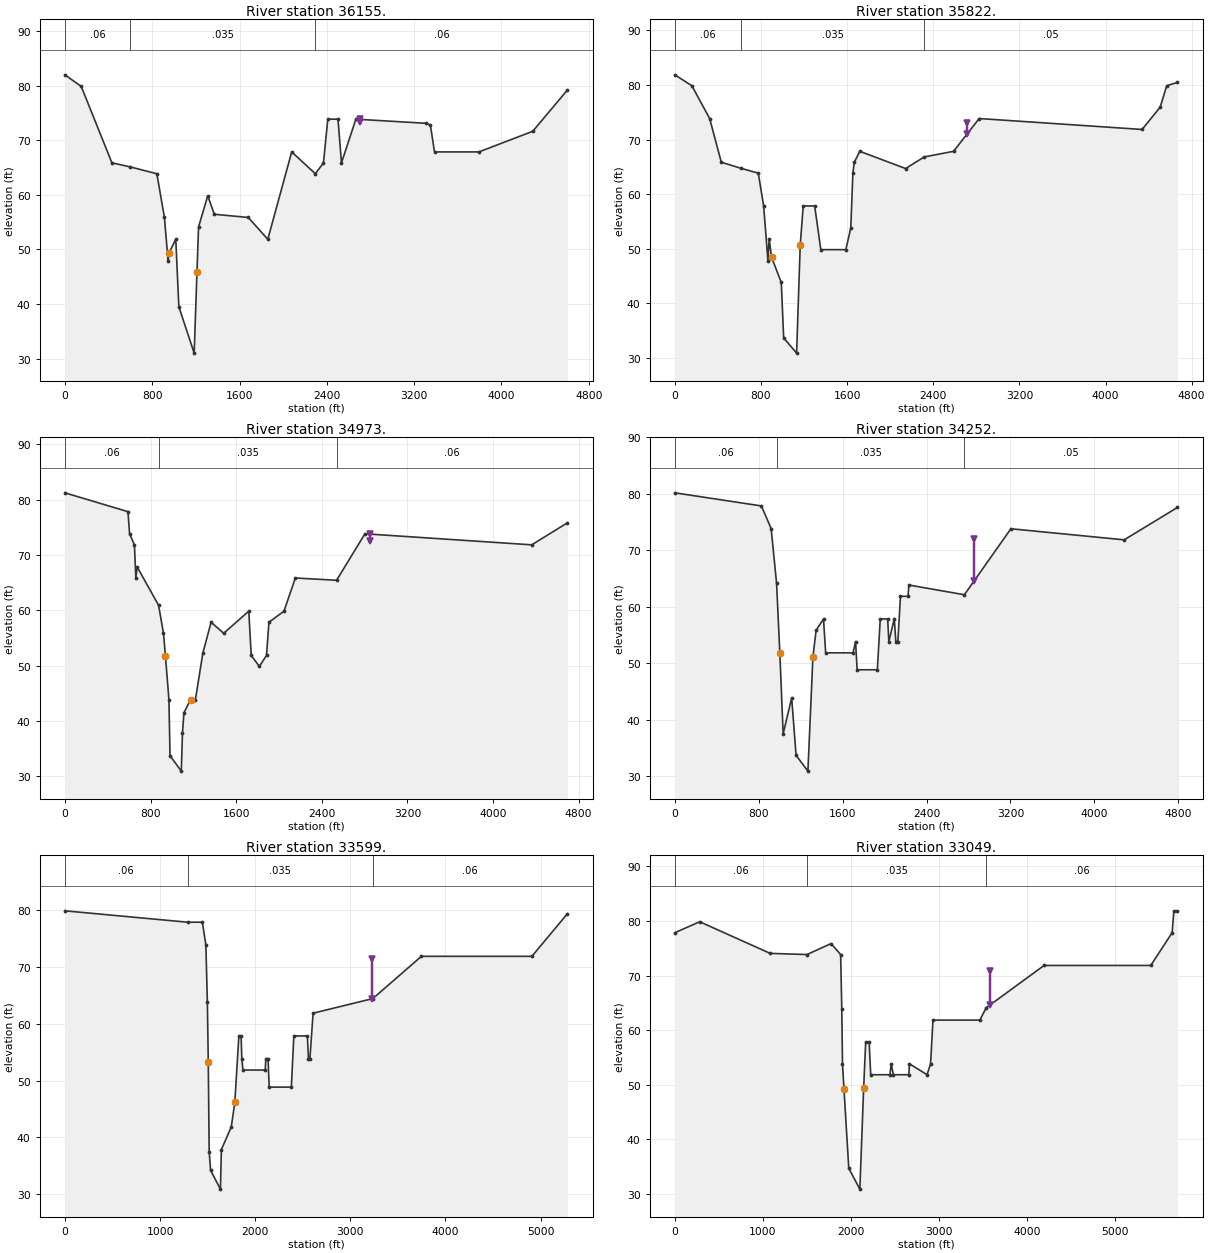
Type RM Length L Ch R = 1 ,36155.  ,323.19,333.66,348.72
XS GIS Cut Line= 5
 6414763.0731954 2043715.7192416 6414321.6532624 2044524.9890398
 6414132.4733249 2044819.2689794 6413838.1933854 2045491.9088412
 6412965.8635764   2047940.73835
#Sta/Elev= 30
       0   81.96  149.37   79.84  430.49   65.84  593.77   65.12  842.64   63.84
  911.84   55.84  945.72   47.84  953.66   49.33 1015.97   51.84 1043.98    39.5
 1184.61   30.99 1210.23   45.88 1224.79    54.1  1308.7    59.8 1369.41   56.42
 1679.83   55.84 1859.29   51.84 2078.25   67.84  2295.5   63.84 2369.36   65.84
 2409.21   73.84 2502.62   73.84 2534.49   65.84 2666.57   73.84 3310.38   73.08
 3349.24   72.76 3387.07   67.84 3793.69   67.84 4287.41   71.62 4605.43   79.19
#Mann= 3 ,-1 , 0
       0     .06       0  593.77    .035       0  2295.5     .06       0
Levee=0,,,-1,2706.82,73.369,,	380
Bank Sta=953.66,1210.23
Exp/Cntr=0.3,0.1

Type RM Length L Ch R = 1 ,35822.  ,862.61,848.98,790.43
XS GIS Cut Line= 5
 6414437.2632268 2043579.0892578 6414069.4133142 2044325.2990927
 6413827.6833757 2044661.6190236 6413470.3434728 2045365.7888671
 6412619.0336358 2047856.6583672
#Sta/Elev= 30
       0   81.84  157.88   79.84     323   73.84  431.11   65.84  616.74   64.72
  774.58   63.84  824.42   57.84  864.26   47.84  875.96   51.84  897.52   48.47
  988.21   43.84 1010.49    33.7 1130.63    30.9 1164.22   50.66 1192.04   57.84
 1298.37   57.84 1355.48   49.84 1587.98   49.84 1634.07   53.84 1653.19   63.84
 1666.69   65.84 1717.37   67.84 2142.85   64.69 2317.24   66.82 2588.33   67.84
 2826.78   73.84 4339.45   71.84 4507.73   75.91 4568.38   79.84 4668.11   80.45
#Mann= 3 ,-1 , 0
       0     .06       0  616.74    .035       0 2317.24     .05       0
Levee=0,,,-1,2711.38,73.00101,,	380
Bank Sta=897.52,1164.22
Exp/Cntr=0.3,0.1

Type RM Length L Ch R = 1 ,34973.  ,757.28,720.97,618.53
XS GIS Cut Line= 5
 6413638.5034382 2043035.1968962 6413362.6159919  2043810.309234
 6413139.2784994 2044230.7091476 6412823.9785878 2045465.6338643
 6412358.1305197 2047536.1201125
#Sta/Elev= 30
       0   81.25  589.19   77.84  604.08   73.84  649.58   71.84  662.62   65.84
   675.1   67.84  875.31    60.9     921   55.84  939.35   51.73  971.76   43.84
  981.99    33.7  1087.4    30.9 1098.45   37.84 1112.18   41.47 1174.44   43.84
 1219.33   43.84  1288.5   52.22 1365.81   57.84 1483.54   55.84 1717.92   59.84
 1740.77   51.84 1816.64   49.84 1883.64   51.84 1906.33   57.84 2046.95   59.84
 2153.04   65.84 2538.29   65.43 2803.38   73.84 4361.75   71.84 4695.57   75.83
#Mann= 3 ,-1 , 0
       0     .06       0  875.31    .035       0 2538.29     .06       0
Levee=0,,,-1,2849.06,72.47288,,	380
Bank Sta=939.35,1174.44
Exp/Cntr=0.3,0.1

Type RM Length L Ch R = 1 ,34252.  ,678.44,652.64,592.59
XS GIS Cut Line= 6
  6412787.195968 2042663.4884821 6412627.4375539 2043633.4502685
 6412547.5583468 2043964.3783985 6412406.3630187 2045005.7454192
 6412270.9692171 2046061.8170245 6412056.8718027 2047399.1843019
#Sta/Elev= 30
       0   80.16     825   77.84  918.14   73.84     970   64.14 1001.12   51.77
  1032.6    37.5  1113.9   43.84 1156.11    33.7 1268.72    30.9 1316.59   51.12
 1347.24   55.84 1417.61   57.84 1437.97   51.84 1699.35   51.84 1723.34   53.84
  1738.2   48.84 1931.03   48.84 1958.92   57.84 2029.53   57.84  2040.8   53.84
 2092.51   57.84 2107.49   53.84 2126.81   53.84 2151.74   61.84 2223.73   61.84
 2231.78   63.84 2761.17   62.12 3204.93    73.8 4285.47   71.84 4793.47   77.57
#Mann= 3 ,-1 , 0
       0     .06       0     970    .035       0 2761.17     .05       0
Levee=0,,,-1,2852,72.00802,,	380
Bank Sta=1001.12,1316.59
Exp/Cntr=0.3,0.1

Type RM Length L Ch R = 1 ,33599.  ,554.07,550.5,509.63
XS GIS Cut Line= 5
  6412273.686773 2042149.9792871 6411958.2476987 2043560.6967645
 6411931.9726745 2043928.5466771 6411945.1102102 2044729.9340391
 6411746.4840064   2047390.05527
#Sta/Elev= 30
       0   79.84 1289.28   77.84 1444.77   77.84 1481.87   73.84  1497.6   63.84
 1506.98    53.3 1516.71    37.5 1531.67    34.2 1634.94    30.9 1644.72   37.84
 1748.91   41.84 1786.01   46.14 1828.86   57.84 1852.36   57.84 1859.64   53.84
 1871.85   51.84 2105.99   51.84 2112.11   53.84 2135.39   53.84 2147.47   48.84
 2380.46   48.84  2406.7   57.84 2549.17   57.84 2560.39   53.84  2575.8   53.84
 2609.01   61.84 3237.19   64.41 3748.04   71.84 4909.13   71.84 5283.36   79.34
#Mann= 3 ,-1 , 0
       0     .06       0 1289.28    .035       0 3237.19     .06       0
Levee=0,,,-1,3232.02,71.39307,,	380
Bank Sta=1506.98,1786.01
Exp/Cntr=0.3,0.1

Type RM Length L Ch R = 1 ,33049.  ,693.51,721.15,745.3
XS GIS Cut Line= 6
 6411878.0788058 2041852.8221331 6411510.2288458 2042772.4469383
 6411405.1288911 2043665.7967666 6411418.2663795 2043954.8217013
 6411470.8163806 2044716.7965034 6411381.3219238 2047481.3457788
#Sta/Elev= 30
       0   77.84  281.95   79.84 1082.55   74.05 1500.95   73.84 1773.92   75.84
 1882.94   73.84 1896.07   63.84 1904.07   53.84 1920.95   49.21  1975.5    34.7
 2101.17    30.9 2144.39   49.42 2167.68   57.84 2206.58   57.84 2224.57   51.84
 2443.89   51.84 2456.81   53.84 2482.42   51.84 2657.89   51.84 2664.79   53.84
 2864.66   51.84 2904.43   53.84 2932.01   61.84 3464.45   61.84 3537.27   64.11
 4194.16   71.84 5406.33   71.84 5648.91   77.84 5668.59   81.84 5709.08   81.84
#Mann= 3 ,-1 , 0
       0     .06       0 1500.95    .035       0 3537.27     .06       0
Levee=0,,,-1,3576.91,70.8285,,	380
Bank Sta=1920.95,2144.39
Exp/Cntr=0.3,0.1

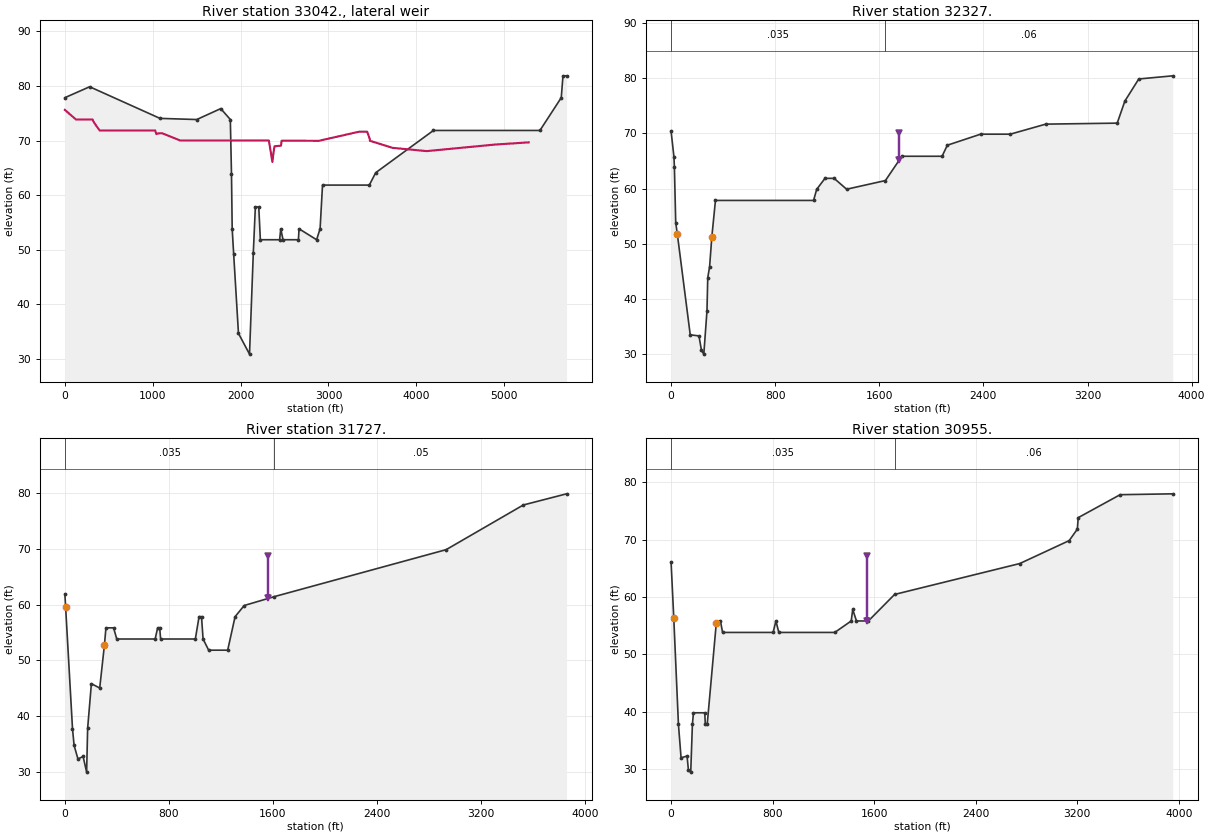
Type RM Length L Ch R = 6 ,33042.  ,,,
Node Name=South LS
Lateral Weir Pos= 0
Lateral Weir Distance=0
Lateral Weir WD=20
Lateral Weir Coef=2
Lateral Weir Is Ogee= 0
Lateral Weir WSCriteria=-1
Lateral Weir Flap Gates= 0
Lateral Weir SS=0.05,0.05,
Lateral Weir Type= 0
Lateral Weir Connection Pos and Dist= 0 ,
Lateral Weir SE= 27
       0   75.61  126.44   73.84  316.56   73.84  322.16   73.56  353.48   72.78
  395.98   71.84 1027.15   71.84 1041.47   71.16 1055.95   71.29 1105.99   71.34
 1311.88      70 2321.67      70 2361.29   66.08  2380.2   68.45  2385.2   68.94
 2459.27   69.06 2466.56   69.96 2892.25   69.95 3350.42   71.62 3440.53    71.6
 3468.49   70.35  3471.7   69.97 3473.22   69.94 3728.17   68.66 4117.38   68.06
 4895.43   69.26 5278.64   69.66
LW Div RC= 0 ,False,

Type RM Length L Ch R = 1 ,32327.  ,1839.94,600.26,528.79
XS GIS Cut Line= 5
 6410715.5872346  2043613.931172 6410674.3556182  2043963.853698
 6410715.4102991 2044743.8925881 6410879.6290227 2045955.0056514
 6410838.5743418 2047453.5014338
#Sta/Elev= 30
       0   70.38   21.98   65.76   25.61   63.84   35.66   53.84   48.49   51.67
  147.23    33.5  214.25    33.3  233.46    30.7  251.54      30  275.87   37.84
  281.86   43.84   296.1   45.84  313.23   51.26  341.05   57.84 1095.01   57.84
 1118.71   59.84 1182.55   61.84 1252.75   61.84    1349   59.87 1646.88   61.44
 1773.32   65.84  2082.3   65.84 2122.68   67.84  2378.3   69.84 2606.35   69.84
 2878.88   71.66 3428.02   71.84 3486.96   75.84 3593.66   79.84 3854.72   80.41
#Mann= 2 ,-1 , 0
       0    .035       0 1646.88     .06       0
Levee=0,,,-1,1752.85,70.00698,,	380
Bank Sta=48.49,313.23
Exp/Cntr=0.3,0.1

Type RM Length L Ch R = 1 ,31727.  ,0,772,797.79
XS GIS Cut Line= 4
 6410079.4474069 2043606.5299361 6410140.6447663 2044004.9083789
 6410284.5265989 2045466.3726105 6410284.3361731 2047453.5014338
#Sta/Elev= 30
       0   61.91    5.71   59.58   58.62    37.8   70.86    34.8  100.53   32.36
  140.15    32.8  167.32      30   175.1   37.84  203.94   45.84     268   45.06
  304.05   52.73  315.91   55.84  374.66   55.84  399.03   53.84  694.39   53.84
  713.58   55.84  729.16   55.84  736.66   53.84 1003.57   53.84 1032.07   57.84
 1050.96   57.84  1063.1   53.84 1105.93   51.84 1252.33   51.84 1309.18   57.84
 1379.44   59.84 1610.92   61.43 2932.65   69.84 3526.04   77.84 3858.71   79.84
#Mann= 2 ,-1 , 0
       0    .035       0 1610.92     .05       0
Levee=0,,,-1,1564.59,68.7301,,	380
Bank Sta=5.71,304.05
Exp/Cntr=0.3,0.1

Type RM Length L Ch R = 1 ,30955.  ,0,410.31,257.47
XS GIS Cut Line= 4
  6409322.941892 2043613.9722108 6409340.0785594 2044128.0724217
 6409565.8792808  2045236.548759  6409639.359792  2047542.883945
#Sta/Elev= 30
       0   66.13   21.18   56.38   58.08    37.8   78.76      32  126.07    32.3
  136.95    29.8  154.91    29.5  168.14   37.84  176.39   39.84  265.37   39.84
  269.93   37.84  284.83   37.84   356.1    55.4     389   55.84  405.97   53.84
  804.13   53.84  825.96   55.84   849.2   53.84    1290   53.84 1419.67   55.84
 1431.34   57.84    1461   55.84 1554.73   55.84 1761.45   60.46 2747.52   65.84
 3137.14   69.84 3201.46   71.84 3208.22   73.84 3538.71   77.84 3953.13   77.99
#Mann= 2 ,-1 , 0
       0    .035       0 1761.45     .06       0
Levee=0,,,-1,1546.26,67.12914,,	380
Bank Sta=21.18,356.1
Exp/Cntr=0.3,0.1