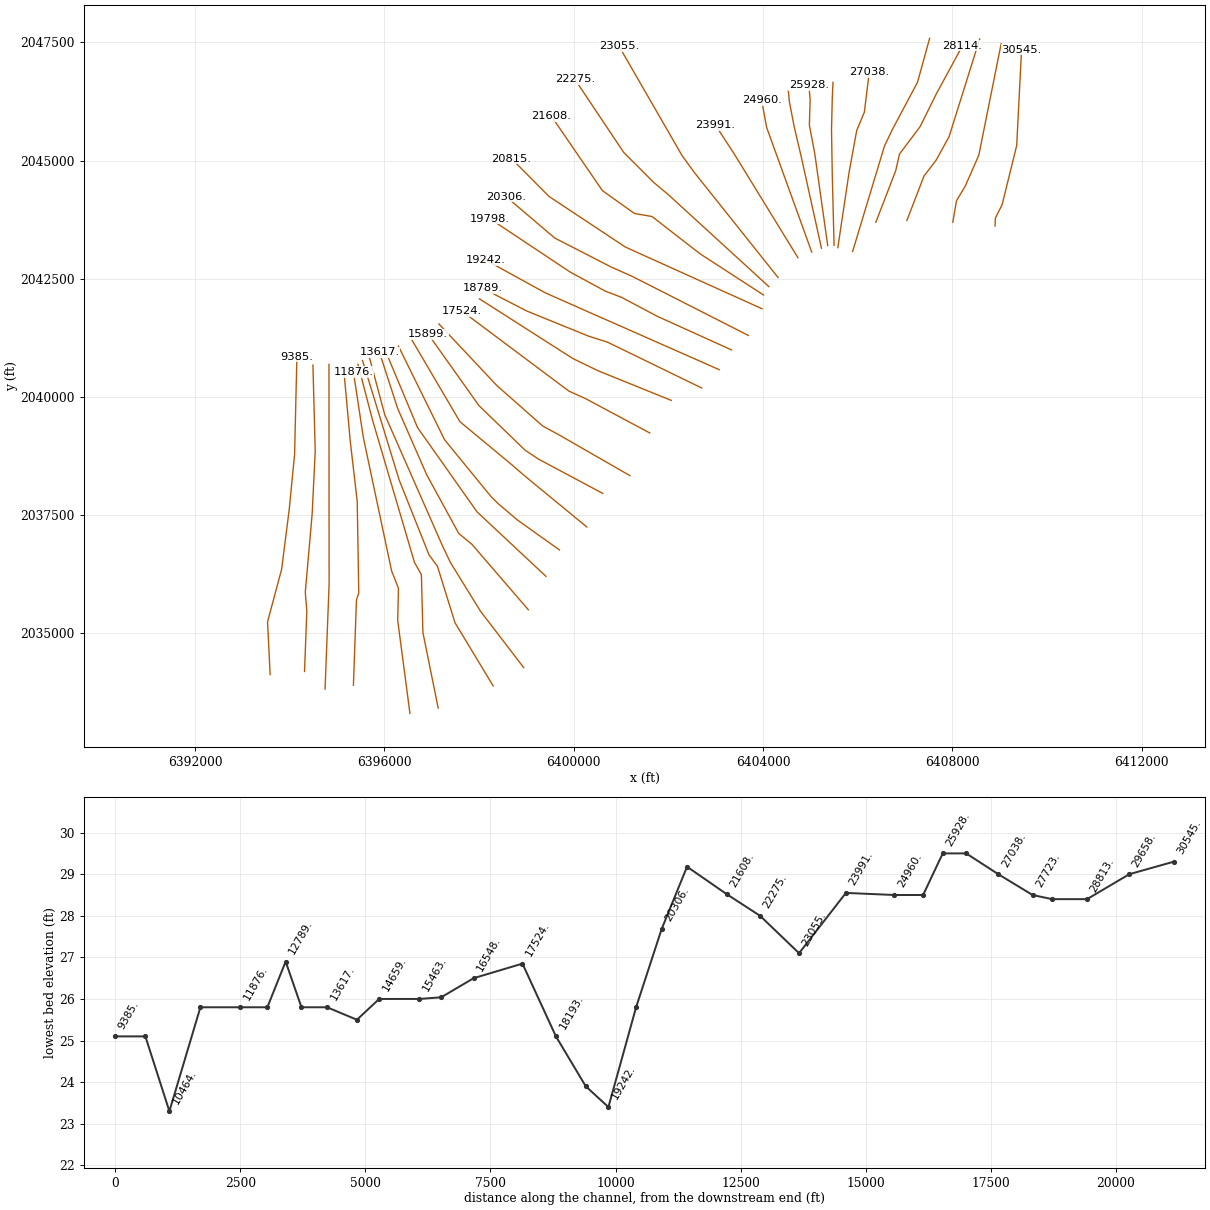
HEC-RAS study Baxter.prj: Baxter River GIS Example

--- Baxter.g01 (geometry) --- (continued)

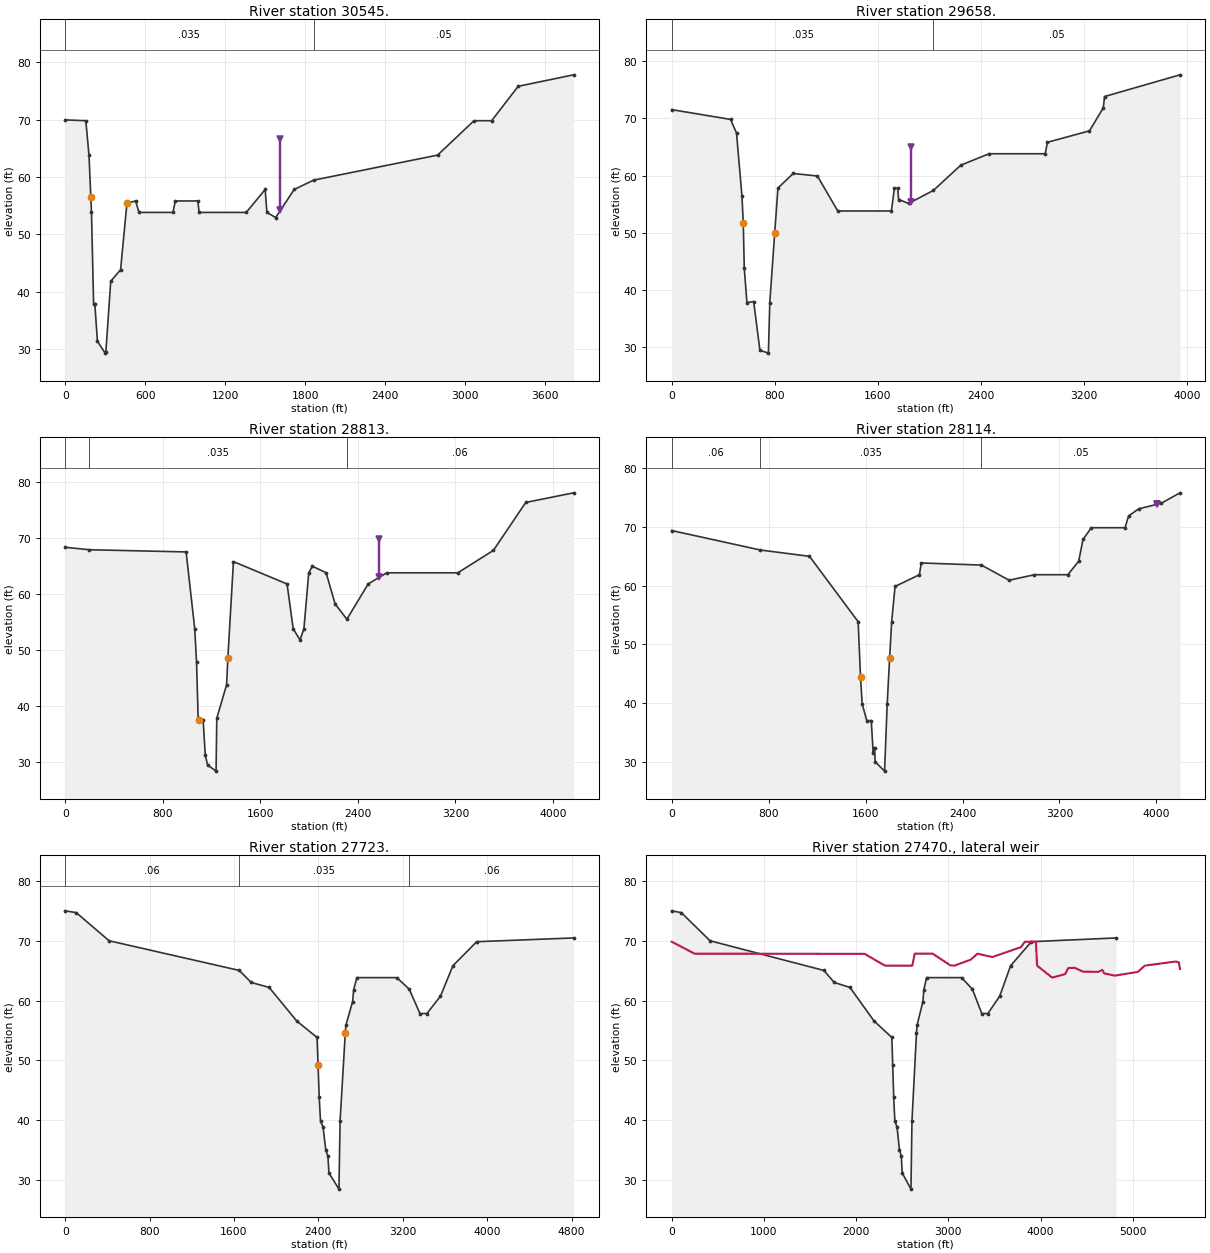
Type RM Length L Ch R = 1 ,30545.  ,902.81,887.34,816.68
XS GIS Cut Line= 5
 6408902.9193746  2043613.931172 6408909.0044335 2043779.1076575
  6409052.695793  2044066.490424 6409360.6058762 2045318.6581209
 6409463.2426022 2047350.8647078
#Sta/Elev= 30
       0   69.98  154.46   69.84  178.25   63.84  192.02   56.49  196.98   53.84
  213.06   37.84  222.41    37.8  241.47   31.36  299.68    29.3  304.49   29.41
   341.4   41.84  415.07   43.84  462.86   55.45  527.81   55.84  553.38   53.84
  808.31   53.84  824.76   55.84  994.53   55.84 1003.71   53.84  1357.1   53.84
 1499.17   57.84 1512.08   53.84 1577.72   52.95 1716.44   57.84 1862.44   59.47
  2791.9   63.84 3064.89   69.84 3197.12   69.84 3396.05   75.84 3810.86   77.84
#Mann= 2 ,-1 , 0
       0    .035       0 1862.44     .05       0
Levee=0,,,-1,1613.59,66.62889,,	380
Bank Sta=192.02,462.86
Exp/Cntr=0.3,0.1

Type RM Length L Ch R = 1 ,29658.  ,857.08,844.81,775.99
XS GIS Cut Line= 5
 6408009.7468605 2043692.6432103 6408087.9108625 2044148.5997858
 6408272.6569029  2044456.509869 6408560.0396694 2045113.3847163
 6409032.1684762 2047474.0287506
#Sta/Elev= 30
       0   71.55  456.95   69.84  503.24   67.47  545.73    56.4  555.68   51.78
  563.54   43.84  584.14   37.84  636.55   38.01  684.92    29.5  750.91      29
  761.66   37.84  799.77   49.98  824.81   57.84  943.13   60.39 1131.47   59.95
  1289.3   53.84 1705.87   53.84 1729.09   57.84 1754.09   57.84 1761.82   55.84
 1839.33   55.16 2032.09   57.44 2244.32   61.84 2463.75   63.84 2899.89   63.84
  2916.6   65.84 3243.16   67.84 3350.31   71.84  3360.7   73.84 3946.07   77.63
#Mann= 2 ,-1 , 0
       0    .035       0 2032.09     .05       0
Levee=0,,,-1,1860.77,65.0979,,	380
Bank Sta=555.68,799.77
Exp/Cntr=0.3,0.1

Type RM Length L Ch R = 1 ,28813.  ,668.58,698.93,673.99
XS GIS Cut Line= 5
 6407039.1905082 2043728.8185786 6407400.1680035 2044669.5066666
 6407658.4019393 2045008.4386926 6407932.7754932 2045508.7669463
 6408578.3603092 2047574.6383858
#Sta/Elev= 30
       0    68.4  197.36   67.96  991.55   67.57 1062.14   53.84 1077.04   47.91
 1090.21   37.84 1097.92   37.57 1131.31    37.5 1148.43   31.34  1167.2    29.5
 1237.24    28.4 1243.06   37.84 1323.58   43.84 1334.11   48.68 1379.66   65.84
 1819.57   61.84 1869.55   53.84 1925.69   51.84 1957.69   53.84 1997.19   63.84
 2026.94   65.02 2139.74   63.84 2213.66   58.26 2310.07   55.55  2484.5   61.84
 2636.54   63.84 3219.63   63.84 3511.44   67.84 3776.76   76.41 4168.68   78.13
#Mann= 3 ,-1 , 0
       0     .06       0  197.36    .035       0 2310.07     .06       0
Levee=0,,,-1,2575.23,69.91955,,	380
Bank Sta=1097.92,1334.11
Exp/Cntr=0.3,0.1

Type RM Length L Ch R = 1 ,28114.  ,360.35,390.56,451.68
XS GIS Cut Line= 6
 6406383.6799769 2043692.2465963 6406803.0020416 2044782.4839928
 6406883.7001317 2045137.5556842 6407319.4699133 2045718.5819807
 6407665.1485421 2046418.4992649 6408216.2795937 2047433.7407431
#Sta/Elev= 30
       0   69.36  732.83   66.04 1137.09   64.97 1538.58   53.84 1558.21    44.4
 1571.87   39.84 1609.75      37 1646.74      37 1662.86    31.5 1673.88   32.42
 1678.95      30 1756.66    28.4 1778.32   39.84 1798.21   47.61 1815.18   53.84
 1843.18   59.84 2044.01   61.84 2059.64   63.84 2555.43   63.48 2784.66    60.9
 2993.52   61.84  3268.8   61.84 3358.53   64.14 3393.88   67.84 3462.99   69.84
 3740.63   69.84 3770.26   71.84 3853.73   73.06 4039.32      74 4194.32   75.78
#Mann= 3 ,-1 , 0
       0     .06       0  732.83    .035       0 2555.43     .05       0
Levee=0,,,-1,4002.5,73.93548,,	380
Bank Sta=1558.21,1798.21
Exp/Cntr=0.3,0.1

Type RM Length L Ch R = 1 ,27723.  ,624.48,685.03,705.83
XS GIS Cut Line= 5
 6405892.9099351 2043073.4349505  6406566.613635 2045308.1594714
 6406730.9316186  2045653.227204 6407263.6861287 2046656.2023339
 6407520.7882071 2047588.1972914
#Sta/Elev= 30
       0      75  104.87    74.7  415.72      70 1650.48   65.04 1763.01   63.03
 1933.44    62.2 2194.36    56.6 2387.62   53.84 2396.83   49.29 2407.87   43.84
 2420.33   39.84 2444.04   38.88  2469.9   35.07 2490.44      34 2500.08    31.2
 2595.07    28.5 2605.65   39.84 2654.85   54.53 2660.38   55.84 2724.49   59.84
 2734.86   61.84 2764.91   63.84 3143.26   63.84 3260.81   61.92 3362.84   57.84
 3428.83   57.84 3557.37   60.74 3675.82   65.84 3900.81   69.84 4818.76   70.47
#Mann= 3 ,-1 , 0
       0     .06       0 1650.48    .035       0 3260.81     .06       0
Bank Sta=2396.83,2654.85
Exp/Cntr=0.3,0.1

Type RM Length L Ch R = 6 ,27470.  ,,,
Node Name=North LS
Lateral Weir Pos= 3
Lateral Weir Distance=0
Lateral Weir WD=20
Lateral Weir Coef=2
Lateral Weir Is Ogee= 0
Lateral Weir WSCriteria=-1
Lateral Weir Flap Gates= 0
Lateral Weir SS=0.05,0.05,
Lateral Weir Type= 0
Lateral Weir Connection Pos and Dist= 0 ,
Lateral Weir SE= 30
       0   69.84   248.5   67.84 2091.82   67.81 2313.68   65.84 2609.55   65.84
 2635.68   67.84 2831.04   67.84 3021.44   65.89 3066.15   65.84 3242.95   66.84
 3316.39   67.84 3476.85   67.28  3786.3   68.92 3830.66   69.84 3949.75   69.84
 3962.76   65.84 4126.04   63.84 4267.12   64.43 4300.91   65.45 4371.78   65.47
 4461.03   64.84 4626.77   64.81 4670.04   65.14 4689.74   64.55    4804   64.17
  5054.3   64.79 5130.79   65.84 5467.54   66.53 5499.43   66.38 5512.54   65.28
LW Div RC= 0 ,False,

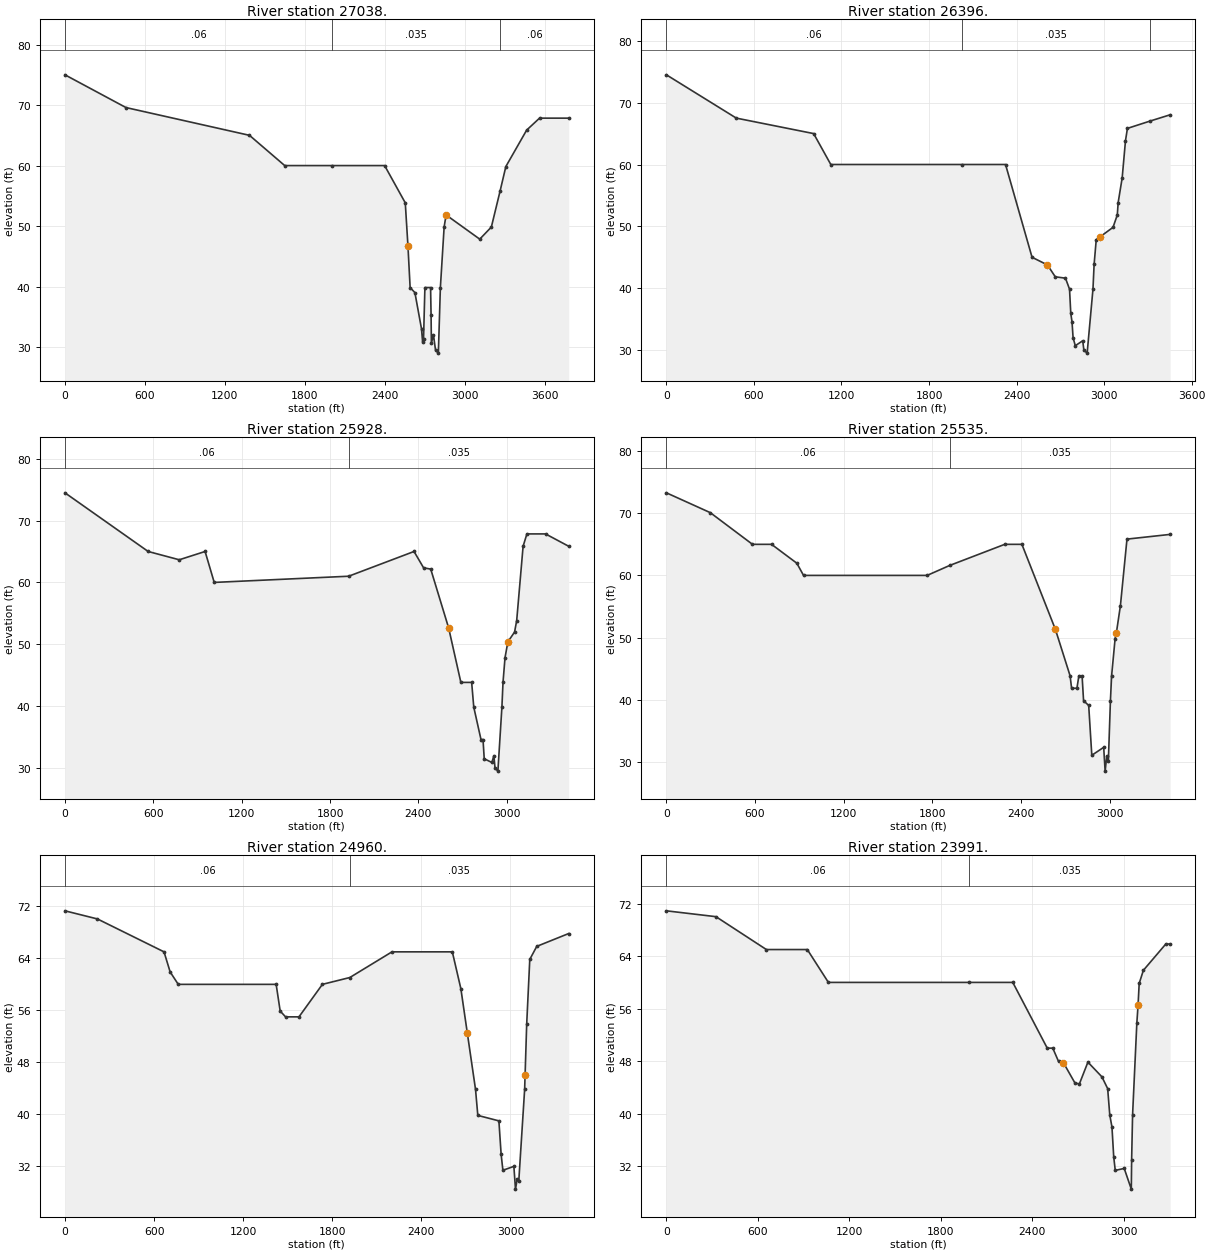
Type RM Length L Ch R = 1 ,27038.  ,481.08,641.78,711.72
XS GIS Cut Line= 5
 6405580.7057804  2043155.593966 6405818.4851523 2044750.2047568
 6405979.8813799 2045637.8838906 6406141.2776076  2046025.234818
 6406243.6811175 2046864.6507802
#Sta/Elev= 30
       0      75  457.66   69.59 1384.39      65 1648.72      60 2002.94      60
 2398.35      60 2553.29   53.84 2573.53   46.64 2589.69   39.84 2625.55      39
 2675.15      33 2683.12    30.9 2690.27    31.3 2700.57   39.84 2743.13   39.84
 2746.91   35.24 2749.25   30.66 2764.97      32 2780.18    29.5 2801.52      29
 2816.67   39.84 2844.85   49.84 2859.58   51.84 3112.11   47.84 3199.21   49.84
 3264.02   55.73 3307.93   59.84    3464   65.86 3560.66   67.84 3779.74   67.84
#Mann= 3 ,-1 , 0
       0     .06       0 2002.94    .035       0 3264.02     .06       0
Bank Sta=2573.53,2859.58
Exp/Cntr=0.3,0.1

Type RM Length L Ch R = 1 ,26396.  ,407.87,468.66,469.88
XS GIS Cut Line= 5
 6405501.4660595 2043204.3421721 6405463.4135082 2044685.6462847
 6405447.2738902 2045654.0235086 6405463.4135082  2046331.887608
 6405478.1409552 2046655.8671125
#Sta/Elev= 30
       0    74.5   479.1    67.5 1009.06      65 1126.68      60 2025.07      60
 2324.36      60 2506.02      45 2611.51   43.76 2665.22   41.84 2735.19   41.62
 2762.94   39.84 2771.45   35.91 2779.85    34.6 2787.26      32 2802.36    30.7
 2853.41    31.5 2861.18   29.99 2883.69    29.5 2923.54   39.84 2931.39   43.84
 2945.98   47.84 2969.72   48.26 3060.94   49.84  3090.4   51.84 3096.23   53.84
  3123.8   57.84 3146.39   63.84 3159.68   65.84 3317.04   67.04 3452.68   68.04
#Mann= 3 ,-1 , 0
       0     .06       0 2025.07    .035       0 3317.04     .06       0
Bank Sta=2611.51,2969.72
Exp/Cntr=0.3,0.1

Type RM Length L Ch R = 1 ,25928.  ,309.94,393.16,426.71
XS GIS Cut Line= 5
    6405366.5758  2043200.801189 6405092.2022461 2045153.6953023
 6404979.2249199 2045750.8612641 6404995.3645379 2046283.4687066
 6404970.1599786 2046590.9640941
#Sta/Elev= 30
       0   74.48     565      65  775.98   63.66   951.6      65 1013.53      60
 1926.51      61 2370.61      65 2435.44   62.36 2483.98   62.15 2605.76   52.63
 2688.69   43.84 2761.89   43.84 2776.31   39.84 2825.38    34.6 2839.11    34.6
  2847.3    31.5 2899.18    30.9 2912.97      32 2920.64      30 2940.12    29.5
 2967.36   39.84 2974.86   43.84 2988.52   47.84 3007.99    50.4 3053.41   51.98
  3067.8   53.84 3111.33   65.84 3137.12   67.84 3263.63   67.84 3421.21   65.84
#Mann= 2 ,-1 , 0
       0     .06       0 1926.51    .035       0
Bank Sta=2605.76,3007.99
Exp/Cntr=0.3,0.1

Type RM Length L Ch R = 1 ,25535.  ,528.69,574.56,573.7
XS GIS Cut Line= 5
 6405234.6106572  2043142.760127 6404801.6890742 2045105.2764008
 6404659.8451718 2045708.6775659 6404557.2084458 2046242.3883705
 6404534.7479969 2046478.0143164
#Sta/Elev= 30
       0   73.29   296.9    70.1  582.54      65  711.74      65  882.82   61.96
  928.12      60 1764.85      60 1917.22    61.6 2289.96      65 2406.11      65
 2632.93   51.31 2732.39   43.84 2742.47   41.84 2778.67   41.84 2791.75   43.84
 2813.51   43.84 2823.54   39.84 2858.28   39.07 2879.28   31.05 2959.81   32.33
 2969.54    28.5 2980.57    30.9 2991.32   30.07 3005.36   39.84 3013.31   43.84
 3037.12   49.84 3045.09   50.67 3072.86   55.11 3117.39   65.84 3409.73    66.6
#Mann= 2 ,-1 , 0
       0     .06       0 1917.22    .035       0
Bank Sta=2632.93,3045.09
Exp/Cntr=0.3,0.1

Type RM Length L Ch R = 1 ,24960.  ,805.36,968.87,1020.34
XS GIS Cut Line= 3
 6405029.3372527 2043060.6507652  6404077.196256 2045698.4146412
 6403970.2587844 2046276.9633666
#Sta/Elev= 30
       0   71.31  218.66   70.06  667.05      65  708.26   61.91  762.84      60
 1422.24      60 1449.38   55.89 1485.69      55 1575.91      55 1733.75      60
 1918.32   61.05 2202.31      65 2608.68      65 2666.27   59.33 2709.43   52.55
 2764.96   43.84 2780.37   39.84 2922.33      39 2937.25    33.9 2949.26    31.4
 3023.23      32 3034.08    28.5 3045.44      30  3056.2    29.7 3095.74   43.84
 3098.83   46.05 3109.52   53.84 3130.38   63.84 3177.27   65.84  3392.7   67.82
#Mann= 2 ,-1 , 0
       0     .06       0 1918.32    .035       0
Bank Sta=2709.43,3098.83
Exp/Cntr=0.3,0.1

Type RM Length L Ch R = 1 ,23991.  ,907.59,936.63,941.61
XS GIS Cut Line= 3
 6404737.1306021 2042942.5672531 6403387.8487647 2045145.1390625
 6402994.0515705 2045750.8612641
#Sta/Elev= 30
       0   70.89  325.12      70  655.92      65   924.5      65 1062.91      60
 1985.67      60 2272.76      60 2498.92      50 2535.22      50 2573.07   47.97
 2604.67    47.8 2681.01   44.68    2710   44.57 2765.75   47.87 2857.77   45.63
 2895.35   43.84 2909.12   39.84 2923.53      38  2935.1   33.45 2945.14    31.4
 3003.97    31.7 3050.45   28.55 3052.61   33.01 3058.84   39.84 3086.83   53.84
 3094.85   56.54 3102.19   59.84 3129.67   61.84 3276.78   65.84 3305.48   65.84
#Mann= 2 ,-1 , 0
       0     .06       0 1985.67    .035       0
Bank Sta=2604.67,3094.85
Exp/Cntr=0.3,0.1

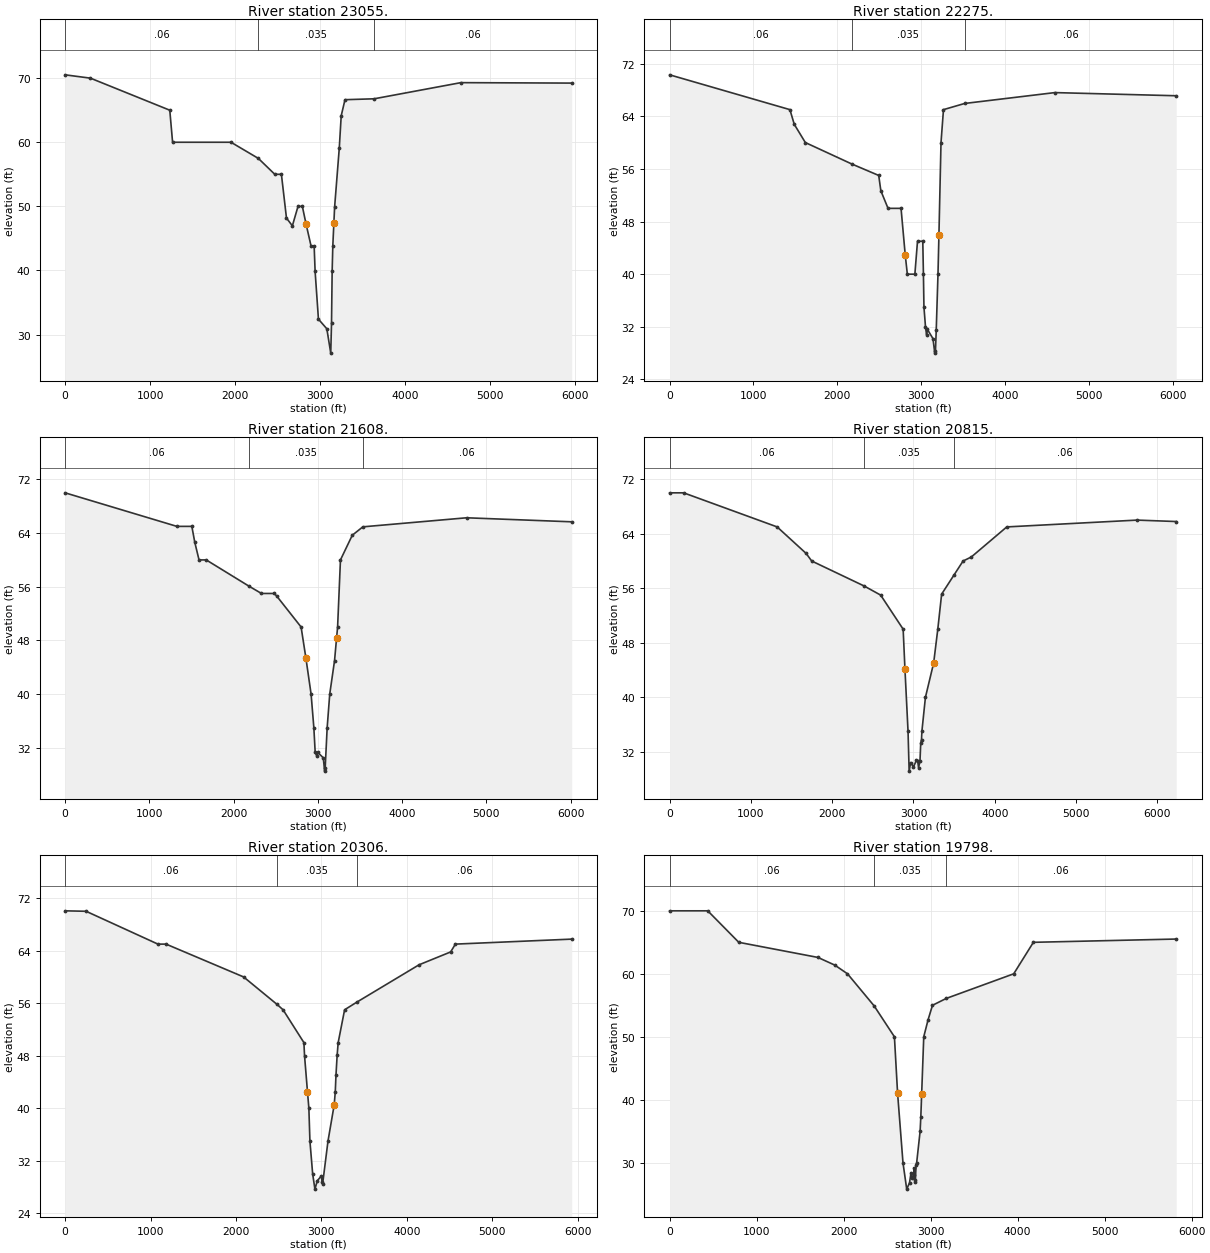
Type RM Length L Ch R = 1 ,23055.  ,687.29,779.99,813.91
XS GIS Cut Line= 4
 6404317.5004385 2042522.9371369  6402558.281789 2044734.0651387
 6402290.2382489 2045102.7620037 6400955.1547086 2047423.7533985
#Sta/Elev= 30
       0   70.52  297.99      70 1231.18      65 1264.22      60 1951.35      60
 2273.15   57.48 2466.47      55 2544.28      55 2603.91   48.17 2673.32   46.96
 2739.61      50 2790.72      50 2834.76   47.21 2892.67   43.84 2929.42   43.84
 2940.84   39.84 2979.94    32.4 3078.66    30.9 3124.79    27.1 3133.85    31.8
 3141.17   39.84 3149.06   43.84 3161.69   47.44    3170   49.84 3225.09   59.09
 3247.75   64.13 3292.27   66.64 3634.96   66.78 4655.11    69.3    5959   69.23
#Mann= 3 ,-1 , 0
       0     .06       0 2273.15    .035       0 3634.96     .06       0
Bank Sta=2834.76,3161.69
Exp/Cntr=0.3,0.1

Type RM Length L Ch R = 1 ,22275.  ,540.42,666.98,765.75
XS GIS Cut Line= 5
 6404123.8250222 2042329.2616732 6401993.3951105 2044282.1557865
 6401686.0510507 2044539.6482308 6401057.2970753 2045169.8349203
 6400024.3613792 2046719.2384881
#Sta/Elev= 30
       0   70.29 1434.72      65 1486.63   62.77 1618.66      60 2174.78   56.73
 2494.18      55 2519.58   52.67  2605.4      50 2760.56      50 2810.42   42.93
 2835.56      40 2925.45      40 2956.97      45 3019.96      45 3027.55      40
 3033.68      35 3052.23      32 3064.92    30.8 3075.36    31.6 3141.45    30.2
 3162.92      28 3171.09   28.28  3180.4   31.51 3201.29      40 3212.47   45.92
 3237.34      60 3266.72      65 3519.95   65.94 4595.42   67.59 6043.38   67.11
#Mann= 3 ,-1 , 0
       0     .06       0 2174.78    .035       0 3519.95     .06       0
Bank Sta=2810.42,3212.47
Exp/Cntr=0.3,0.1

Type RM Length L Ch R = 1 ,21608.  ,772.86,793.04,708.77
XS GIS Cut Line= 6
 6404010.8476486 2042151.7258275 6402671.2591626 2043023.2653433
 6401654.4630372 2043814.1067689 6401283.2517751  2043878.665241
  6400605.387723 2044362.8538767 6399524.0331255 2045944.5366805
#Sta/Elev= 30
       0      70 1326.65      65 1504.31      65 1539.29   62.62 1589.63      60
 1675.29      60 2187.53   56.05    2331      55 2483.47      55 2513.16   54.59
 2801.25      50  2858.2   45.38  2919.9      40 2952.62      35 2968.57    31.3
 2986.48    30.8 3000.21    31.3 3064.78    30.5  3080.5   28.52  3087.2      29
 3110.76      35 3141.22      40 3198.47      45 3222.54   48.37 3234.62      50
 3268.53      60 3408.93   63.68 3534.18   64.93 4765.41   66.28  6013.4   65.68
#Mann= 3 ,-1 , 0
       0     .06       0 2187.53    .035       0 3534.18     .06       0
Bank Sta=2858.2,3222.54
Exp/Cntr=0.3,0.1

Type RM Length L Ch R = 1 ,20815.  ,515.87,508.38,529.25
XS GIS Cut Line= 5
 6403978.5684125 2041861.2127029 6401444.6480027 2043007.1257253
 6401089.5763587 2043168.5219529  6399476.292903 2044240.0926013
 6398684.7728458 2045040.7179287
#Sta/Elev= 30
       0      70  172.01      70 1322.82      65 1679.62   61.11 1747.99      60
 2392.47   56.34 2596.48      55 2873.32      50 2895.63   44.11 2933.57      35
 2947.11   29.18 2965.24   30.44 3000.53    29.8 3037.56    30.8 3053.61    30.6
 3062.64    29.7 3080.25    30.6 3089.84    33.3  3099.2    33.8 3103.83      35
 3147.38      40 3248.65   45.04 3299.67      50 3346.84   55.14 3496.56    57.9
 3610.83      60 3712.17   60.59 4148.53      65 5751.53      66 6233.59   65.79
#Mann= 3 ,-1 , 0
       0     .06       0 2392.47    .035       0 3496.56     .06       0
Bank Sta=2895.63,3248.65
Exp/Cntr=0.3,0.1

Type RM Length L Ch R = 1 ,20306.  ,505.86,507.88,506.93
XS GIS Cut Line= 5
 6403688.0552406 2041296.3259771  6401250.972539  2042539.076755
 6400782.9235687 2042748.8917894 6399598.7290392 2043358.3597896
 6398571.7955196 2044233.7368851
#Sta/Elev= 30
       0   70.07  245.73      70 1086.39      65 1181.74      65 2089.43      60
 2481.47   55.81 2551.14      55 2795.21      50 2802.66   47.99 2837.13    42.5
 2853.33      40  2865.6      35 2897.68      30 2924.11   27.68 2952.17   28.96
 3000.83    29.7 3007.72    28.7 3014.53    28.5 3077.17      35 3149.84   40.52
 3162.53   42.52 3170.46      45 3184.33   48.08 3196.36      50 3271.65      55
 3418.37   56.19  4143.1   61.85 4513.19   63.81 4568.34      65 5929.81   65.76
#Mann= 3 ,-1 , 0
       0     .06       0 2481.47    .035       0 3418.37     .06       0
Bank Sta=2837.13,3149.84
Exp/Cntr=0.3,0.1

Type RM Length L Ch R = 1 ,19798.  ,548,555.95,564.77
XS GIS Cut Line= 6
 6403332.9835966 2040989.6731872 6401767.4404107 2041699.8164753
 6401008.8782212 2042103.3069734 6400669.9461952  2042232.423965
  6399927.523671 2042635.9144632 6398232.8634936 2043765.6879148
#Sta/Elev= 30
       0      70   437.9      70  794.64      65  1704.5    62.6 1898.37   61.38
 2044.25      60 2350.21   54.91 2583.57      50 2619.83   41.07 2681.97      30
 2724.78   25.81 2757.06   26.81 2774.74   28.42 2784.53    27.6 2803.16      28
 2811.08    29.2  2817.5   27.32 2823.87      27 2832.76    29.7 2839.32      30
 2878.97      35 2887.13    37.3 2896.69   40.91 2920.78      50 2970.48    52.7
 3021.12      55 3179.44   56.09 3954.96      60 4180.77      65 5822.68   65.52
#Mann= 3 ,-1 , 0
       0     .06       0 2350.21    .035       0 3179.44     .06       0
Bank Sta=2619.83,2896.69
Exp/Cntr=0.3,0.1

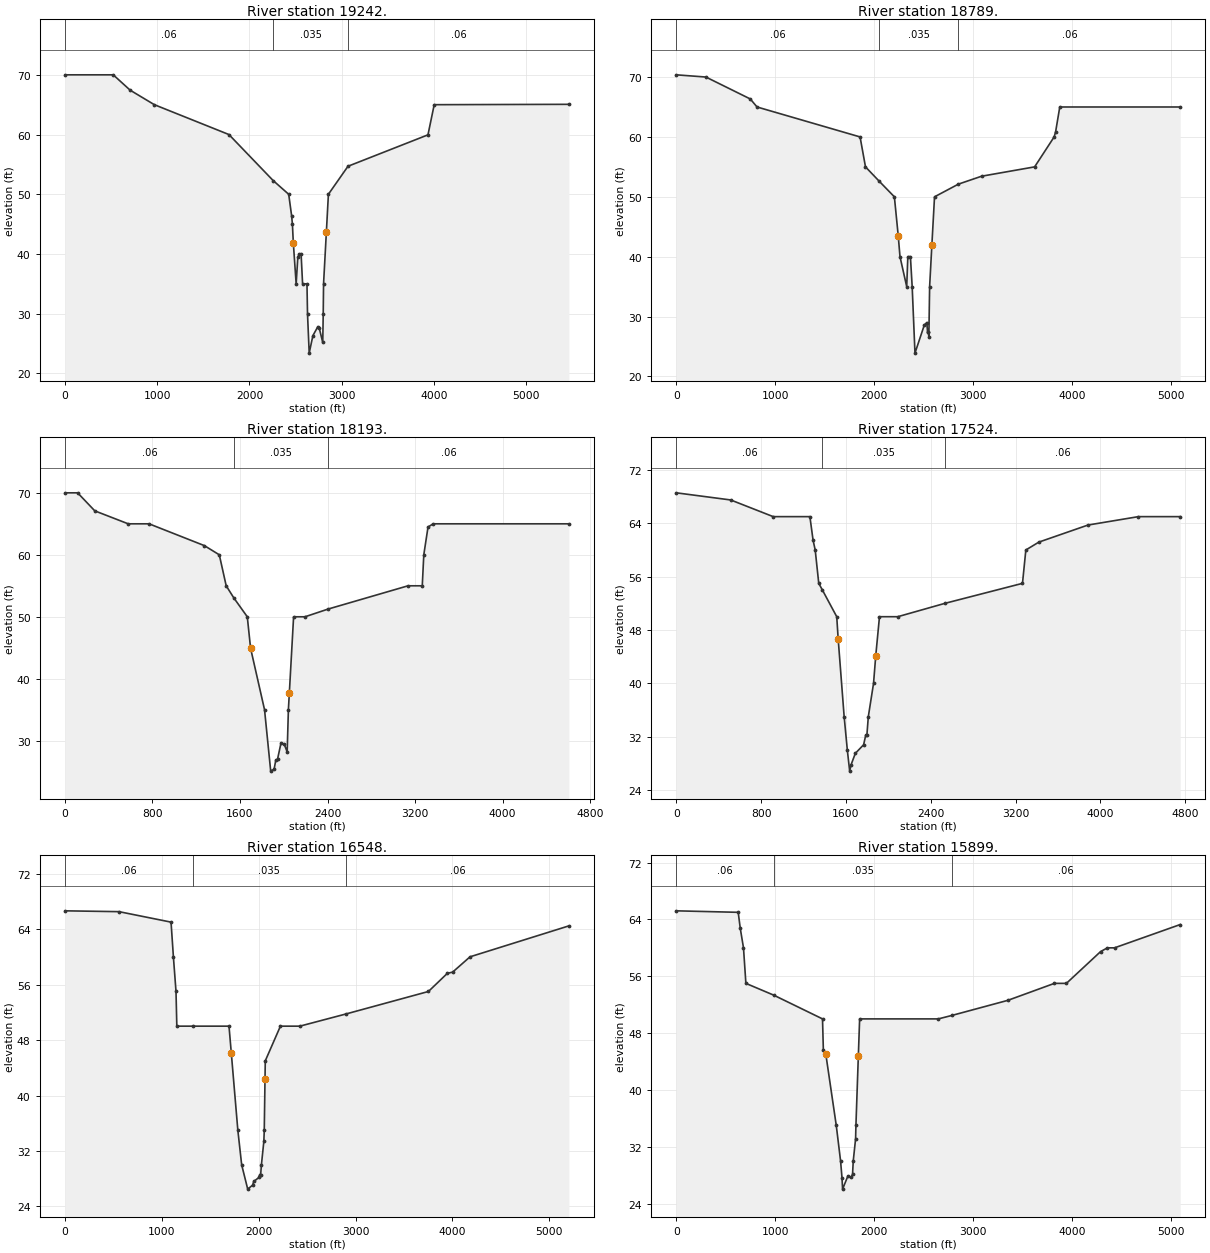
Type RM Length L Ch R = 1 ,19242.  ,430.4,453.3,476.43
XS GIS Cut Line= 5
 6403074.7496607 2040570.0430237 6400815.2028048  2041570.699531
 6400411.7122593 2041748.2353294 6399394.9161813  2042200.144729
 6398136.0257854  2042894.148399
#Sta/Elev= 30
       0      70  523.12      70  706.21   67.43  968.76      65 1777.18      60
 2256.17    52.3 2424.99      50 2456.65    46.4  2465.2      45 2474.83   41.92
 2505.85      35 2524.03    39.5 2541.65      40 2559.38      40 2575.52      35
 2623.14      35 2628.85      30 2647.18    23.4 2687.22   26.33 2741.37   27.84
 2755.03   27.66 2794.08   25.18 2799.25      30  2802.8      35 2833.61   43.76
 2855.36      50 3067.75   54.69 3934.67   59.95 4002.28      65 5462.24   65.06
#Mann= 3 ,-1 , 0
       0     .06       0 2256.17    .035       0 3067.75     .06       0
Bank Sta=2474.83,2833.61
Exp/Cntr=0.3,0.1

Type RM Length L Ch R = 1 ,18789.  ,623.5,596.19,531.54
XS GIS Cut Line= 5
 6402703.5383986 2040182.6921435 6400718.3650493 2041151.0693675
 6400314.8745511 2041280.1863591 6399007.5653011 2041812.7938015
 6398071.4672659 2042296.9824371
#Sta/Elev= 30
       0   70.37  299.41      70  748.31   66.34  816.75      65  1859.1      60
 1913.91      55 2054.61   52.57 2206.13      50 2244.91   43.53 2263.01      40
 2330.98      35 2342.16      40 2368.44      40 2386.19      35 2414.54    23.9
 2509.13    28.6 2534.07      29  2541.6    27.5 2549.49    27.4 2554.96   26.67
 2562.76      35 2585.27    41.9 2612.31      50 2854.14   52.12 3088.46   53.44
 3625.02      55 3822.41      60 3837.41   60.86 3879.46      65 5097.96      65
#Mann= 3 ,-1 , 0
       0     .06       0 2054.61    .035       0 2854.14     .06       0
Bank Sta=2244.91,2585.27
Exp/Cntr=0.3,0.1

Type RM Length L Ch R = 1 ,18193.  ,662.6,669.15,596.36
XS GIS Cut Line= 4
 6402061.1237963 2039919.7493458 6400516.6632057 2040546.2758171
 6399977.5589909 2040808.5427286 6398006.9087938 2042071.0277374
#Sta/Elev= 30
       0      70  115.56      70  272.58   67.09  577.87      65  768.67      65
 1274.53   61.48 1410.67      60  1473.7      55  1543.3   53.05 1666.59      50
 1696.53   44.94  1824.3      35 1880.57    25.1  1911.5    25.4 1927.41   26.89
 1942.73      27 1974.35    29.6 2002.86    29.5 2031.18    28.2  2042.3      35
 2050.73   37.64  2089.9      50 2193.67      50 2407.78   51.26 3136.13      55
 3266.11      55 3280.11      60 3318.84   64.49 3366.01      65 4606.59      65
#Mann= 3 ,-1 , 0
       0     .06       0  1543.3    .035       0 2407.78     .06       0
Bank Sta=1696.53,2050.73
Exp/Cntr=0.3,0.1

Type RM Length L Ch R = 1 ,17524.  ,950.83,975.5,889.35
XS GIS Cut Line= 4
 6401606.0441831 2039230.4545376  6400250.316079 2039956.7374437
 6399895.2444349 2040118.1336714 6397635.6975317 2041812.7938015
#Sta/Elev= 30
       0   68.57  513.16    67.5  913.85      65 1259.85      65 1289.96   61.46
 1309.96      60 1343.42      55 1377.86      54 1513.05      50 1526.27   46.73
 1583.02      35    1613      30 1635.05   26.85 1647.66   27.78 1688.61   29.52
  1766.4    30.8  1786.1    32.2 1797.21    32.2 1810.71      35 1860.08      40
 1880.89   44.14 1916.14      50 2088.66      50 2532.78      52 3264.89      55
 3296.46      60 3418.94   61.18 3882.45   63.74 4357.87      65 4752.48      65
#Mann= 3 ,-1 , 0
       0     .06       0 1377.86    .035       0 2532.78     .06       0
Bank Sta=1526.27,1880.89
Exp/Cntr=0.3,0.1

Type RM Length L Ch R = 1 ,16548.  ,652.68,649.31,606.17
XS GIS Cut Line= 5
 6401186.4140669 2038326.6357858 6399701.5689712 2039182.0356362
 6399346.4973272 2039375.7110999 6398378.1200559 2040231.1109976
  6397151.508896 2041538.4202476
#Sta/Elev= 30
       0   66.63     558   66.51 1095.03      65 1119.33      60 1146.28      55
 1154.71      50 1317.94      50 1693.45      50 1717.38   46.09 1784.64      35
 1824.22      30 1886.68    26.5  1937.3   27.08 1948.86    27.6 2003.93    28.2
 2011.37    28.6 2019.95   28.53 2028.06      30 2053.32    33.4 2057.53      35
 2065.16   42.34    2068      45 2224.35      50 2425.23      50 2899.41   51.75
 3752.46      55 3948.25   57.62 4002.36   57.79 4182.09      60 5202.81   64.46
#Mann= 3 ,-1 , 0
       0     .06       0 1317.94    .035       0 2899.41     .06       0
Bank Sta=1717.38,2065.16
Exp/Cntr=0.3,0.1

Type RM Length L Ch R = 1 ,15899.  ,521.59,436.41,469.59
XS GIS Cut Line= 5
 6400612.4488148 2037950.1286694 6399256.9728605 2038675.1506849
 6398973.2685832 2038864.2868855 6397996.0649827 2039809.9677937
 6396924.2933056 2041323.0572091
#Sta/Elev= 30
       0   65.21  625.47      65  646.48   62.73  678.92      60  703.05      55
  984.83   53.34  1477.5      50 1485.86   45.69 1510.92   45.03 1616.49      35
 1660.05      30 1674.32   27.64 1680.34   26.04 1734.32    27.9 1765.04    27.7
 1780.89    28.1 1788.01      30 1811.85   33.14 1815.09      35 1839.35   44.74
 1852.63      50 2647.71      50 2785.75   50.49 3350.05   52.61 3820.85      55
 3942.09      55 4287.43   59.47 4356.47      60 4428.29      60 5092.25   63.28
#Mann= 3 ,-1 , 0
       0     .06       0  984.83    .035       0 2785.75     .06       0
Bank Sta=1510.92,1839.35
Exp/Cntr=0.3,0.1

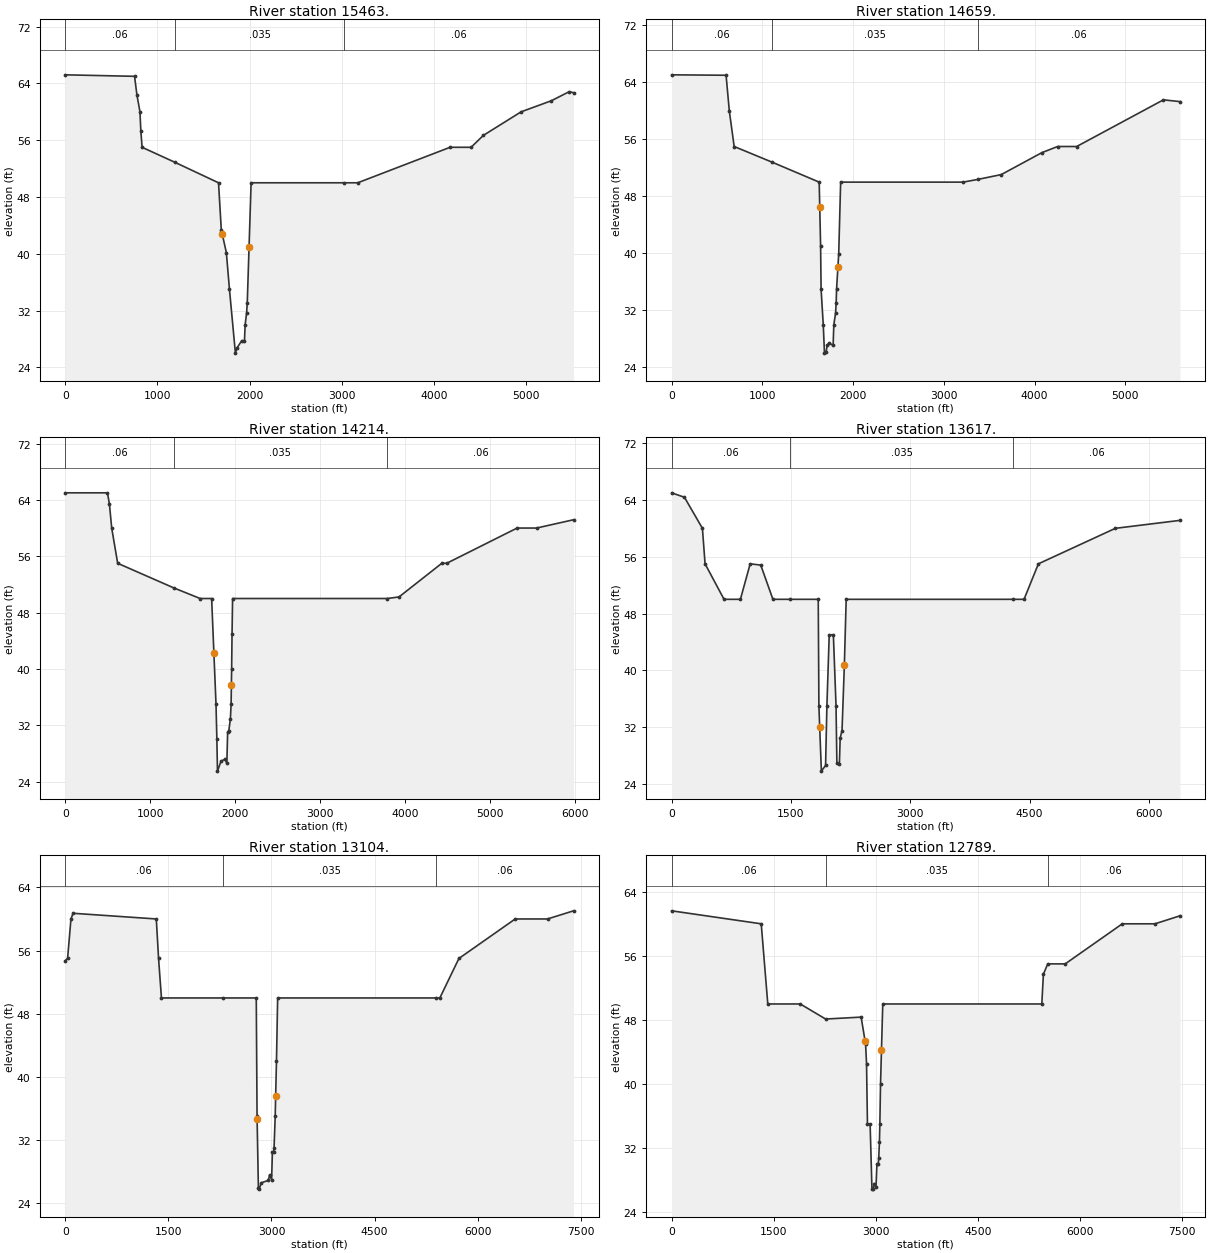
Type RM Length L Ch R = 1 ,15463.  ,822.58,803.89,638.48
XS GIS Cut Line= 5
 6400276.2518584 2037238.7988528 6398975.2860177 2038310.4961677
 6398689.4715781 2038558.2411577 6397595.3013653 2039468.0674821
 6396570.4825522 2041215.6278396
#Sta/Elev= 30
       0   65.21     752      65  777.54    62.4  810.56      60  820.24   57.31
  833.69      55 1194.09   52.86 1662.64      50 1692.75   43.37 1702.71   42.79
 1747.59   40.16  1781.2      35 1845.71      26 1861.72    26.7 1915.11   27.77
 1943.76   27.65 1951.36      30 1967.21   31.65 1974.39    33.1 1993.85   40.96
 2016.11      50 3027.89      50 3172.72      50 4173.69      55 4401.99      55
 4535.02   56.68 4944.79      60 5272.77   61.56 5464.79   62.83 5512.69   62.69
#Mann= 3 ,-1 , 0
       0     .06       0 1194.09    .035       0 3027.89     .06       0
Bank Sta=1702.71,1993.85
Exp/Cntr=0.3,0.1

Type RM Length L Ch R = 1 ,14659.  ,456.86,444.9,367.41
XS GIS Cut Line= 6
 6399698.2905987 2036752.2662234 6398815.6551222 2037382.7201623
 6398405.8600288 2037729.4698239 6398248.2465677  2037887.083285
 6397271.0429672 2039084.9457309 6396293.8393667 2041070.8756241
#Sta/Elev= 30
       0   65.06  599.79      65  635.33      60  688.88      55 1111.16   52.78
 1626.21      50  1632.2   46.55 1641.72   41.08 1647.01      35 1670.95      30
 1684.51      26  1702.5    26.2 1714.56    27.1 1733.14    27.4 1779.79    27.1
 1787.49      30 1806.81    31.6 1813.32    33.1 1817.87      35 1832.39   38.04
 1841.49   39.94 1862.76      50 3213.07      50 3378.54   50.39 3633.49   51.06
 4081.24   54.14 4254.78      55  4464.8      55 5420.95   61.55 5603.62    61.3
#Mann= 3 ,-1 , 0
       0     .06       0 1111.16    .035       0 3378.54     .06       0
Bank Sta=1632.2,1832.39
Exp/Cntr=0.3,0.1

Type RM Length L Ch R = 1 ,14214.  ,628.52,596.48,457.36
XS GIS Cut Line= 5
 6399412.9566494 2036193.3738639 6398168.7542238  2037359.813635
 6397955.9183627 2037559.3472844 6396699.5995438 2039343.4318638
 6396005.5958264 2041005.8128052
#Sta/Elev= 30
       0      65  497.25      65  520.49   63.37  546.99      60  617.24      55
 1274.99   51.52 1587.58      50 1722.89      50  1749.4   42.23 1774.27      35
 1784.36      30 1791.48    25.5 1832.98    26.9  1880.3    27.2 1901.66    26.6
 1911.22    31.1 1924.38    31.2  1943.6    32.9 1951.82      35 1955.27   37.74
 1958.12      40  1962.9      45 1969.38      50 3788.15      50 3927.32   50.22
    4431      55  4488.8      55 5316.66      60  5545.3      60 5980.68   61.18
#Mann= 3 ,-1 , 0
       0     .06       0 1274.99    .035       0 3788.15     .06       0
Bank Sta=1749.4,1955.27
Exp/Cntr=0.3,0.1

Type RM Length L Ch R = 1 ,13617.  ,639.51,512.79,334.05
XS GIS Cut Line= 6
 6399039.8445372 2035486.0625387 6397845.5126134 2036874.0699262
 6397571.1390596 2037100.0245786 6396893.2749602 2038342.7754038
 6396279.9693803  2039746.922362 6395892.6185002 2040941.2542857
#Sta/Elev= 30
       0      65  160.69   64.37   386.5      60  419.85      55  658.37      50
  864.13      50  986.89      55  1119.9   54.82 1272.82      50 1492.23      50
 1842.72      50 1850.94      35 1861.09   31.95 1882.02    25.8 1934.86    26.6
 1951.55      35 1980.72      45 2032.79      45 2066.36      35 2076.96    26.9
 2108.41    26.8 2118.65    30.5 2141.59    31.5 2171.01   40.75 2193.95      50
 4296.12      50 4429.85      50 4610.56      55  5578.1      60 6390.69   61.12
#Mann= 3 ,-1 , 0
       0     .06       0 1492.23    .035       0 4296.12     .06       0
Bank Sta=1861.09,2171.01
Exp/Cntr=0.3,0.1

Type RM Length L Ch R = 1 ,13104.  ,377.94,315.9,299.35
XS GIS Cut Line= 6
 6398943.0067817 2034259.4513789 6398027.5979465 2035457.2601951
 6397393.6032139 2036486.7189987 6397232.2070335 2036825.6510721
 6396005.5958264 2039617.8054177 6395682.8034184 2040828.2769595
#Sta/Elev= 30
       0   54.71    34.6      55   83.72      60  113.95   60.72 1325.17      60
 1358.04      55 1399.93      50 2301.33      50 2779.28      50 2790.86      35
  2791.6   34.65 2810.16   25.97 2822.64    25.8  2851.1    26.6 2953.87    26.9
 2973.57    27.6 3002.41      27 3014.09    30.5 3032.06    30.5 3037.93      31
 3054.74      35 3061.28   37.59 3073.31   42.02 3090.42      50 5393.12      50
 5449.59      50 5727.11      55 6546.17      60 7016.01      60 7394.45   61.03
#Mann= 3 ,-1 , 0
       0     .06       0 2301.33    .035       0 5393.12     .06       0
Bank Sta=2791.6,3061.28
Exp/Cntr=0.3,0.1

Type RM Length L Ch R = 1 ,12789.  ,486.66,365.94,230.91
XS GIS Cut Line= 6
 6398297.4219657 2033872.1004988 6397490.4409221 2035211.6889848
   6397119.22966 2036406.0209086 6396941.6938616 2036648.1152264
 6396312.2486163 2038229.7980302 6395537.5468561 2040763.7184874
#Sta/Elev= 30
       0   61.62 1315.67      60 1412.04      50 1889.16      50 2261.79   48.12
 2783.37   48.36 2842.44   45.32 2848.75      45 2862.72   42.55 2876.09      35
  2915.3      35 2942.17    26.9 2959.38    26.9 2978.33    27.6 3001.87    27.2
 3015.24      30 3034.85      30 3041.95   30.84 3052.17    32.8 3058.31      35
 3068.22      40 3081.89   44.21 3101.15      50 5437.61      50 5460.72   53.71
 5524.51      55 5781.22      55 6619.73      60 7099.99      60  7467.6      61
#Mann= 3 ,-1 , 0
       0     .06       0 2261.79    .035       0 5524.51     .06       0
Bank Sta=2842.44,3081.89
Exp/Cntr=0.3,0.1

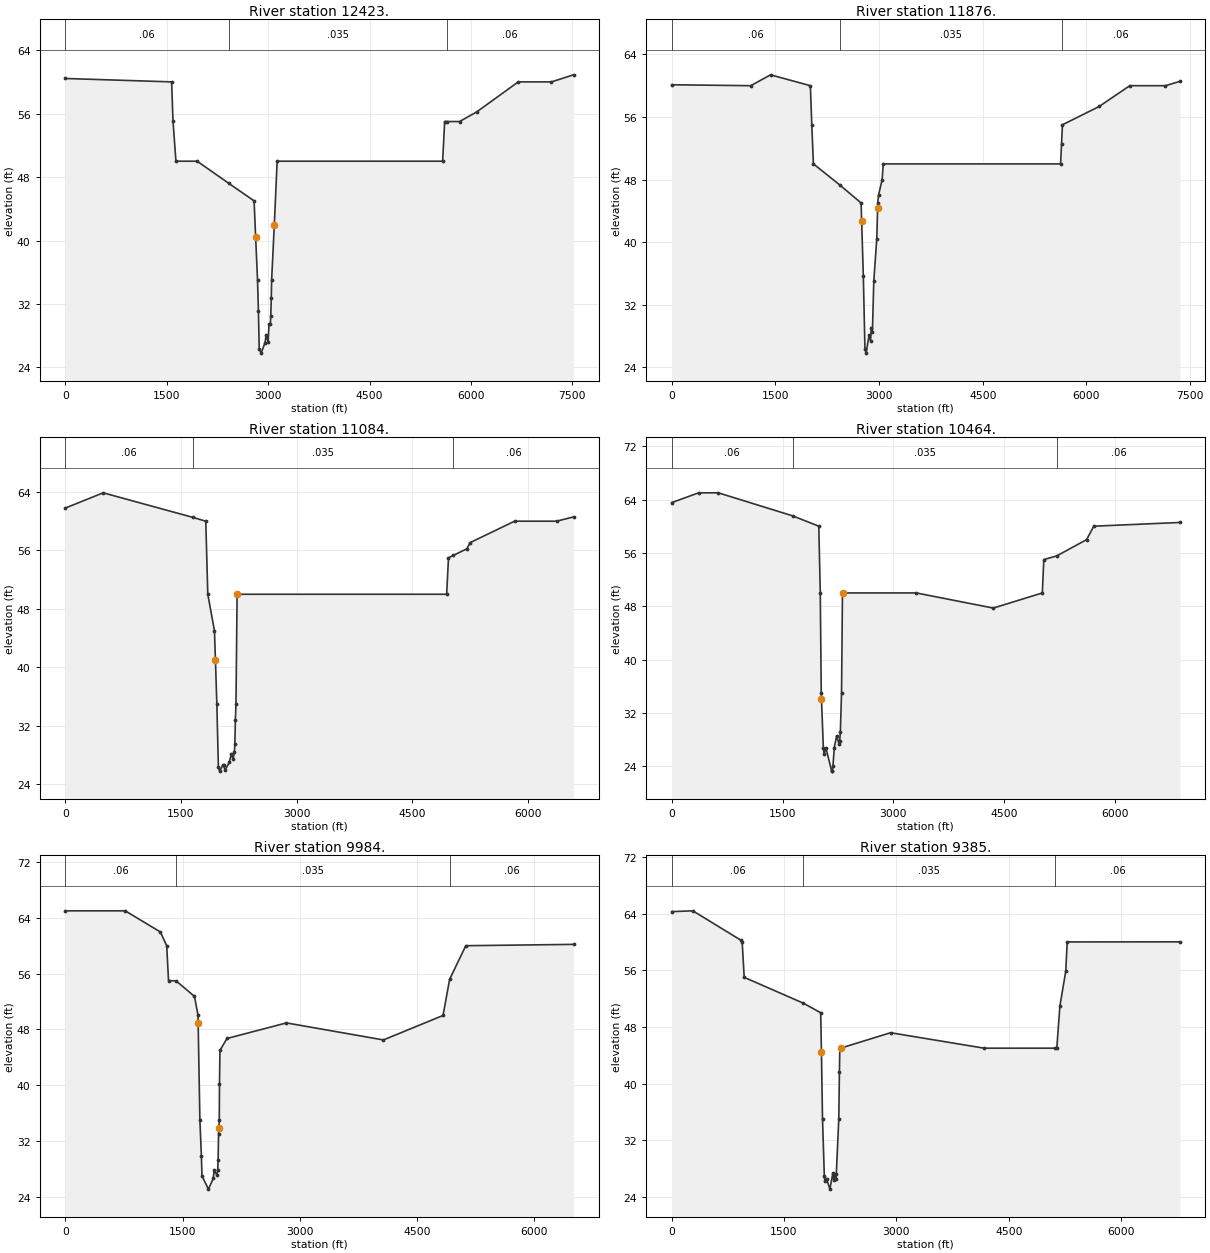
Type RM Length L Ch R = 1 ,12423.  ,497.6,546.79,400.06
XS GIS Cut Line= 6
  6397135.369278 2033404.0514811   6396812.57687  2035001.873903
  6396780.297634 2036228.4851102 6396635.0410717 2036486.7189987
 6395747.3619379 2039504.8280915 6395440.7091479 2040683.0203972
#Sta/Elev= 30
       0   60.43 1573.55      60 1593.84   55.11 1637.39      50 1951.29      50
 2419.92    47.2 2793.14      45 2815.81   40.47 2844.01      35 2857.14   31.11
 2869.17    26.3 2898.11    25.8 2955.33   27.13 2971.13    28.1  3000.8    27.2
 3014.15    29.5 3033.89    29.5  3040.4    30.5 3047.39    32.8 3052.51      35
 3091.85   41.94 3133.97      50  5581.4      50 5611.22      55 5644.38      55
 5831.99      55 6086.21   56.22 6699.45      60 7190.97      60  7516.9   60.89
#Mann= 3 ,-1 , 0
       0     .06       0 2419.92    .035       0 5644.38     .06       0
Bank Sta=2815.81,3091.85
Exp/Cntr=0.3,0.1

Type RM Length L Ch R = 1 ,11876.  ,850.19,791.78,549.41
XS GIS Cut Line= 6
 6396538.2033161 2033291.0741549 6396279.9693803 2035260.1078389
 6396296.1089983 2035937.9719383  6396150.852436 2036309.1832004
 6395553.6864741 2039133.6167821 6395343.8713924 2040521.6241696
#Sta/Elev= 30
       0   60.12 1144.74      60 1430.18   61.39  2006.7      60 2027.15      55
 2050.84      50 2428.87   47.33 2740.68      45 2748.76   42.66 2772.97   35.65
 2796.43    26.3  2813.1    25.8 2855.73    28.1  2876.7   27.39 2888.52   29.03
 2904.19    28.5 2924.08      35 2967.58   40.45 2979.65   44.38 2981.56      45
 2992.82   45.99 3044.71   47.97 3061.27      50 5626.85      50 5640.65   52.56
 5653.62      55 6184.33   57.34 6627.63      60 7143.63      60 7354.42   60.56
#Mann= 3 ,-1 , 0
       0     .06       0 2428.87    .035       0 5640.65     .06       0
Bank Sta=2748.76,2979.65
Exp/Cntr=0.3,0.1

Type RM Length L Ch R = 1 ,11084.  ,622.05,620.21,601.77
XS GIS Cut Line= 6
 6395343.8713924 2033888.2401168 6395408.4298645 2035695.8776205
 6395456.8487659 2035841.1341827 6395424.5694825  2037777.888678
 6395279.3129203 2039036.7790739  6395150.195976 2040457.0656974
#Sta/Elev= 30
       0   61.79  492.53   63.88 1659.17   60.51 1823.03      60 1849.26      50
 1935.73      45 1948.41   41.01 1966.55      35 1986.71    26.3 2002.74    25.8
 2043.66    26.6 2058.13    26.6 2071.11    25.9 2127.45      27 2153.67    28.1
 2176.64    27.5 2194.75   28.38 2200.24    29.5 2207.13    32.8 2214.78      35
 2229.29      50 2231.21      50 4947.16      50 4970.96      55 5033.96   55.32
 5208.78   56.22 5252.07   57.07  5828.6      60 6372.11      60  6592.6   60.58
#Mann= 3 ,-1 , 0
       0     .06       0 1659.17    .035       0 5033.96     .06       0
Bank Sta=1948.41,2231.21
Exp/Cntr=0.3,0.1

Type RM Length L Ch R = 1 ,10464.  ,490.64,480.23,374.72
XS GIS Cut Line= 3
 6394744.7424778 2033805.1969916 6394830.1158225 2036024.9038116
 6394827.4035207 2040683.0203972
#Sta/Elev= 30
       0   63.53  364.48      65  630.82      65 1637.29   61.55 1991.14      60
 2011.05      50 2024.32      35 2027.62   34.07  2052.8    26.8 2062.41    25.9
 2088.93    26.7 2165.78    23.3 2174.79    23.3  2182.8    24.1 2200.51    26.8
 2232.53    28.6 2264.73    27.4 2273.93    27.8 2282.68    29.1 2298.87      35
  2311.5      50 2316.69      50 3310.61      50  4352.9   47.73 5016.22      50
 5036.29      55 5210.15   55.54  5615.5   57.99  5712.6      60 6879.47   60.56
#Mann= 3 ,-1 , 0
       0     .06       0 1637.29    .035       0 5210.15     .06       0
Bank Sta=2027.62,2316.69
Exp/Cntr=0.3,0.1

Type RM Length L Ch R = 1 ,9984.   ,658.33,599.07,507.23
XS GIS Cut Line= 6
 6394310.9356963 2034178.7532887 6394359.3545504 2035453.7833026
 6394327.0753143 2035857.2738008 6394472.3318766 2037519.6547421
 6394536.8903488 2038843.1036102 6394488.4714947 2040666.8807318
#Sta/Elev= 30
       0      65  767.32      65 1216.67   61.97 1298.04      60 1321.04      55
 1418.12   54.96 1653.19   52.73  1698.4      50 1700.15   48.89 1722.11      35
 1741.73    29.8 1748.72      27 1831.46    25.1 1894.19   26.66 1903.36    27.8
 1940.18    27.1 1949.41    27.8 1955.43    29.3 1960.99      33 1964.79   33.83
 1970.12      35 1972.82   40.19 1978.74      45 2069.37    46.7 2828.95   48.93
 4068.81   46.49 4831.48      50  4915.6   55.18 5122.48      60 6499.97   60.19
#Mann= 3 ,-1 , 0
       0     .06       0 1418.12    .035       0  4915.6     .06       0
Bank Sta=1700.15,1964.79
Exp/Cntr=0.3,0.1

Type RM Length L Ch R = 1 ,9385.   ,405.59,380.73,232.99
XS GIS Cut Line= 6
 6393584.6527428 2034114.1947693 6393528.9674135 2035227.7589741
 6393826.7470606 2036341.4624364 6393988.1432883 2037616.4924503
 6394101.1206145  2038778.545138 6394149.5394686 2040844.4165775
#Sta/Elev= 30
       0   64.28  282.71   64.39  927.89   60.22  941.39      60  968.53      55
 1758.16   51.35 1990.03      50 1999.75   44.42 2014.11      35  2038.2      27
 2045.26    26.2 2067.54    26.6 2112.46    25.1 2151.93   27.38  2162.8   26.44
 2179.59    27.1 2188.95    26.6 2198.55    27.3 2231.36      35  2239.8   41.59
 2245.14      45 2255.06      45 2922.32   47.18 4171.57      45  5123.4      45
 5142.31      45 5183.92   50.95 5261.98   55.87 5281.35      60  6787.4   60.01
#Mann= 3 ,-1 , 0
       0     .06       0 1758.16    .035       0  5123.4     .06       0
Bank Sta=1999.75,2255.06
Exp/Cntr=0.3,0.1