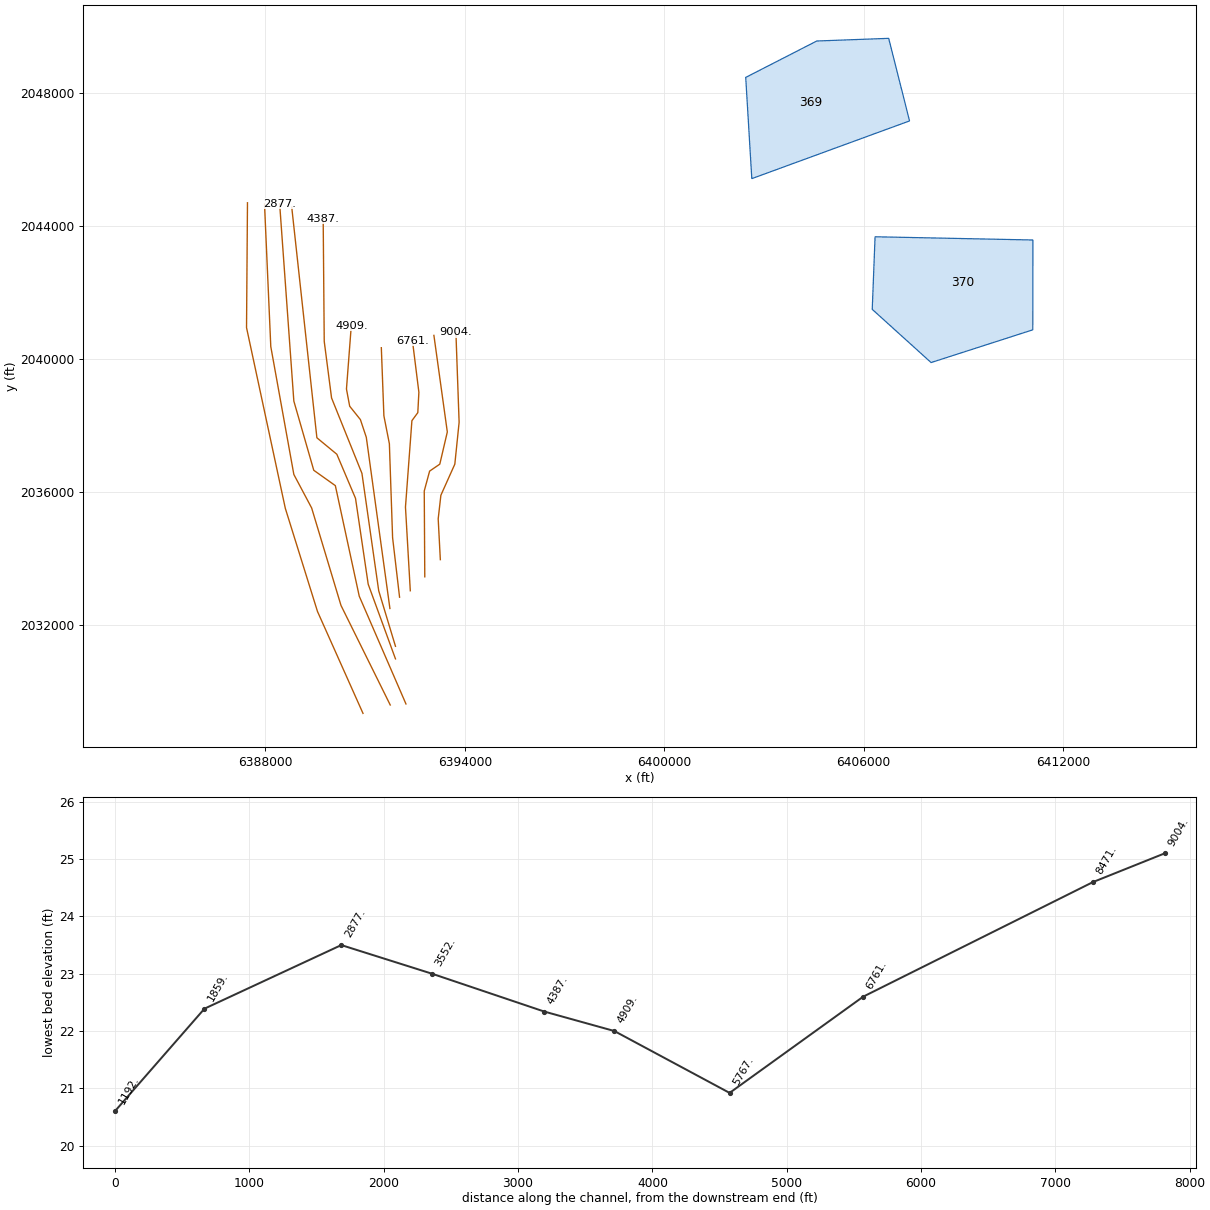
HEC-RAS study Baxter.prj: Baxter River GIS Example

--- Baxter.g01 (geometry) --- (continued)

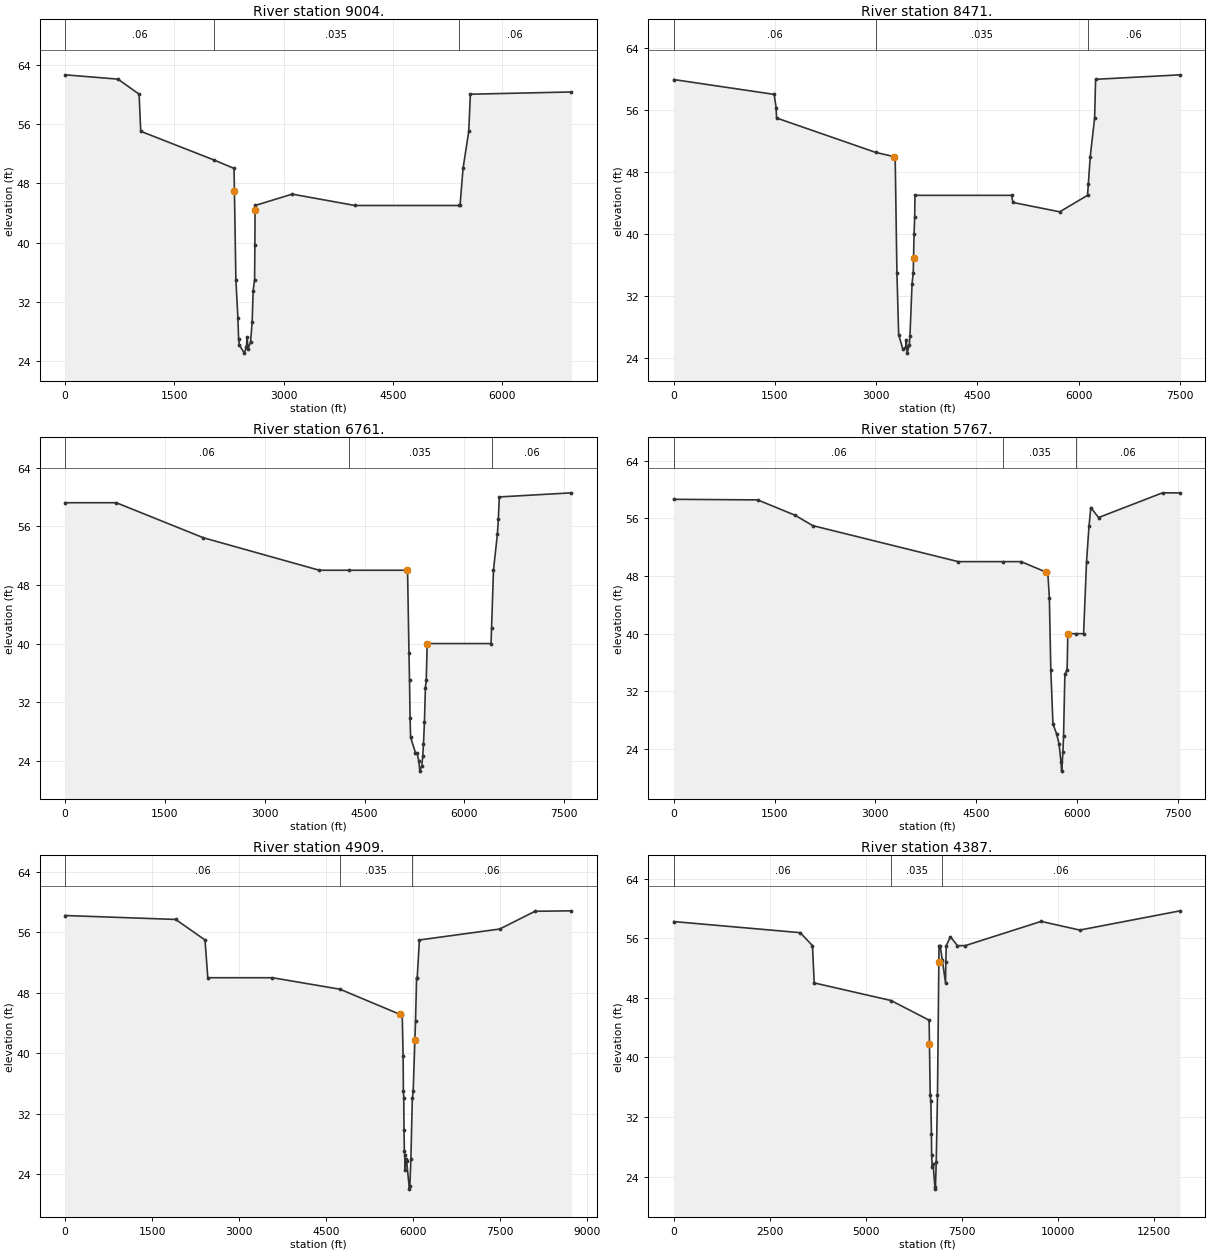
Type RM Length L Ch R = 1 ,9004.   ,528.36,532.4,500.39
XS GIS Cut Line= 6
 6393261.8603348  2033968.938207 6393197.3018627 2035195.5493668
 6393277.9999529 2035905.6926549 6393697.6301164 2036841.7906901
 6393826.7470606  2038100.681086 6393729.9093525 2040812.1373415
#Sta/Elev= 30
       0   62.61  726.03   62.03 1015.79      60 1038.14      55 2039.49   51.15
 2319.11      50 2324.46   46.94 2344.45      35  2372.6    29.8 2381.94      27
 2391.73    26.2 2460.26    25.1 2488.47    25.9  2498.6    27.3 2511.37   25.71
  2545.2   26.54 2568.05    29.3 2581.37    33.5 2601.51      35  2605.3   39.74
 2607.87   44.41 2608.19      45 3118.74   46.53 3978.05      45 5401.86      45
 5421.84      45 5463.09      50 5541.68      55 5563.21      60 6951.94    60.3
#Mann= 3 ,-1 , 0
       0     .06       0 2039.49    .035       0 5401.86     .06       0
Bank Sta=2324.46,2607.87
Exp/Cntr=0.3,0.1

Type RM Length L Ch R = 1 ,8471.   ,852.08,1710.17,1356.54
XS GIS Cut Line= 6
 6392793.8113646 2033452.4703352 6392777.6717465 2036034.8096465
 6392939.0679268 2036631.9756083 6393245.7207168 2036841.7906901
 6393471.6754166 2037810.1679141 6393068.1849184 2040715.2996333
#Sta/Elev= 30
       0   59.97 1489.05   58.05 1517.45   56.35 1523.75      55 2990.61   50.56
 3265.26      50 3282.05      50  3307.9      35 3333.97      27    3396    25.1
 3438.45    25.4  3446.8   26.35  3458.8    24.6 3490.39    25.6 3501.15    26.8
 3531.78    33.5 3549.88      35 3554.44   36.92 3561.92      40 3571.12   42.14
  3575.6      45 5006.69      45 5027.38   44.08 5720.59   42.87 6132.83      45
  6145.3   46.51 6172.67      50 6237.98      55 6252.48      60 7504.74   60.58
#Mann= 3 ,-1 , 0
       0     .06       0 2990.61    .035       0  6145.3     .06       0
Bank Sta=3265.26,3554.44
Exp/Cntr=0.3,0.1

Type RM Length L Ch R = 1 ,6761.   ,738.01,994.4,1068.16
XS GIS Cut Line= 6
  6392358.041583 2033032.8402191 6392212.7850207 2035550.6210108
 6392406.4604371 2038149.0999401 6392583.9962828 2038391.1942579
 6392616.2755189 2039004.4998378 6392422.6000551 2040553.9034056
#Sta/Elev= 30
       0   59.21  769.07   59.21 2078.12   54.43 3820.01      50  4261.4      50
  5137.7      50 5145.84      50 5167.22   38.74 5175.43      35 5183.83    29.8
 5191.82    27.2 5265.15    25.1 5288.15    25.1 5315.65   23.96 5329.75    22.6
 5360.25   23.35 5373.85    24.6  5385.3    26.3 5399.76    29.3 5414.34      34
 5426.43      35    5441      40 5443.98      40  6400.6      40 6408.59   42.19
 6437.11      50 6496.63      55 6510.45   57.03 6524.82      60 7609.41   60.56
#Mann= 3 ,-1 , 0
       0     .06       0  4261.4    .035       0 6408.59     .06       0
Bank Sta=5137.7,5443.98
Exp/Cntr=0.3,0.1

Type RM Length L Ch R = 1 ,5767.   ,658.88,857.88,979.21
XS GIS Cut Line= 6
  6392035.249175 2032839.1647553 6391825.4340933  2034630.662641
 6391728.5963851   2037455.09627 6391563.7590497 2038294.8352413
 6391549.1995447 2038681.0287982 6391486.5020672 2040344.0883239
#Sta/Elev= 30
       0   58.65 1249.04   58.57 1806.44   56.44 2068.19      55 4234.26      50
 4903.98      50 5170.13      50 5537.01   48.56    5567   48.53 5590.45      45
 5612.28      35 5644.22   27.47 5697.76   26.12 5734.21   24.73  5763.6    22.2
 5773.41   20.92 5792.76   23.63 5802.02   25.82  5821.4   34.37 5854.97      35
 5865.19      40 5867.41      40 5989.48      40 6100.16      40 6143.84      50
 6181.49      55 6207.41   57.51 6322.58   56.12 7274.77   59.55 7536.31   59.54
#Mann= 3 ,-1 , 0
       0     .06       0 4903.98    .035       0 5989.48     .06       0
Bank Sta=5537.01,5867.41
Exp/Cntr=0.3,0.1

Type RM Length L Ch R = 1 ,4909.   ,422.9,521.88,490.47
XS GIS Cut Line= 6
 6391744.7360031 2032500.2327293  6391034.592715 2037648.7716864
 6390857.0568693 2038181.3791762 6390534.2644613 2038584.8696743
 6390437.4267531  2039101.337546 6390582.6833154 2041005.8128052
#Sta/Elev= 30
       0   58.24 1905.18   57.72 2410.89      55 2458.73      50 3572.53      50
 4735.78   48.48 5775.72   45.13 5809.41      45 5824.71   39.66 5829.36      35
 5835.56    34.1 5840.39    29.8 5846.63      27 5853.18   26.56 5859.59    24.5
 5867.81      26  5885.5    25.7 5932.99      22 5940.96    22.4 5958.59      26
 5983.23   34.02 5997.92      35 6027.37   41.72  6038.6   44.28 6056.79      50
 6067.72      50 6105.13      55 7489.78   56.45  8097.1    58.8 8726.16   58.86
#Mann= 3 ,-1 , 0
       0     .06       0 4735.78    .035       0 5983.23     .06       0
Bank Sta=5775.72,6027.37
Exp/Cntr=0.3,0.1

Type RM Length L Ch R = 1 ,4387.   ,633.03,834.67,932.95
XS GIS Cut Line= 6
 6391912.1845816 2031361.8850982 6391407.8214116  2033032.588022
 6390903.4582889 2036563.1300228 6389989.3000728 2038832.7641932
 6389768.6412273 2040534.9898092 6389737.1185351 2044223.1452711
#Sta/Elev= 30
       0   58.23 3294.75   56.74 3614.14      55 3659.08      50 5659.94   47.64
 6652.36      45 6661.23   41.78 6679.72      35  6697.7    34.1 6711.62    29.8
 6717.75    26.9 6732.44   25.34 6755.92    25.7 6806.79   22.34 6816.96   22.62
 6837.28      26 6870.18      35 6905.38   52.82 6909.83      55 6939.23      55
 6996.93   53.02 7079.63      50 7087.13    52.8 7097.67      55 7207.94   56.19
 7390.23      55 7591.86      55 9568.98   58.2510576.64   57.0913188.66   59.67
#Mann= 3 ,-1 , 0
       0     .06       0 5659.94    .035       0 6996.93     .06       0
Bank Sta=6661.23,6905.38
Exp/Cntr=0.3,0.1

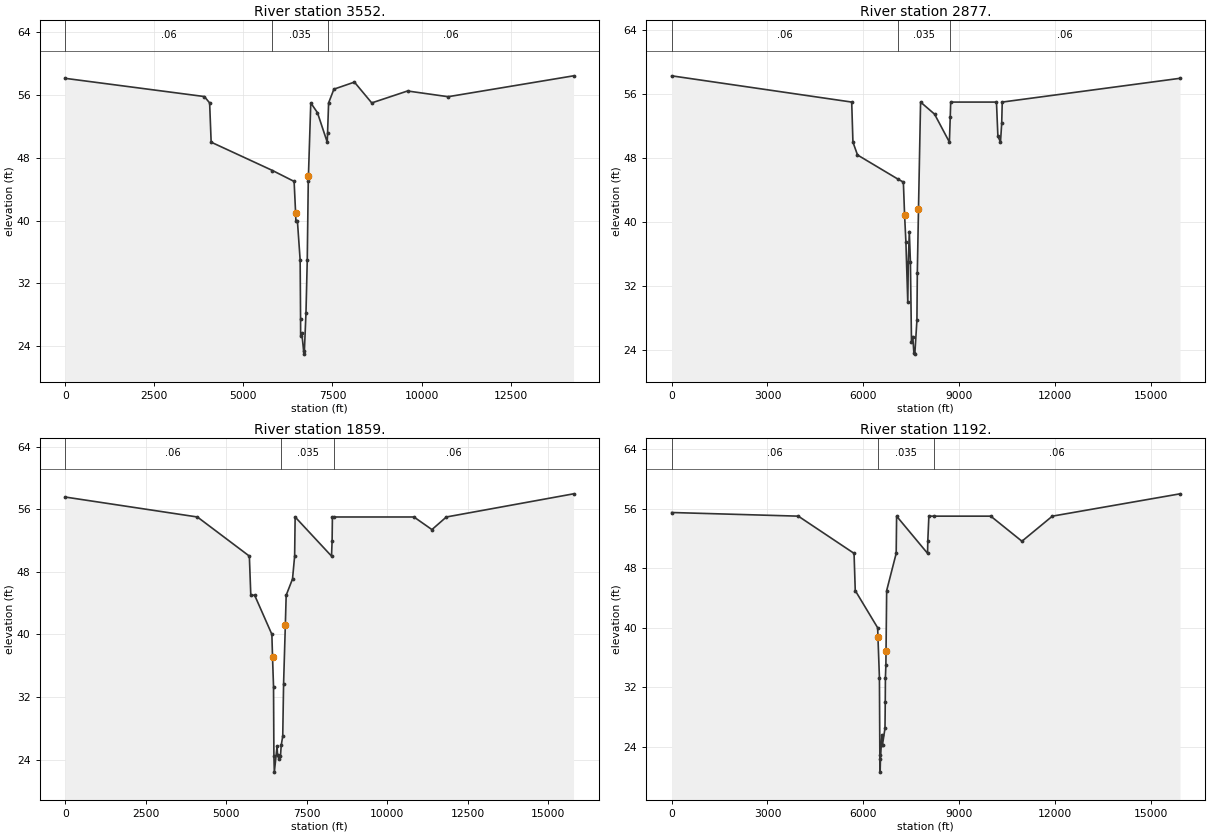
Type RM Length L Ch R = 1 ,3552.   ,465.62,675.44,690.81
XS GIS Cut Line= 6
 6391912.1845816 2030983.6127444 6391091.5627914 2033229.9774283
 6390709.6223619 2035813.6922738 6390147.9452319 2037139.2503102
 6389547.9823345 2037634.9016999 6388791.4376268 2044569.8949327
#Sta/Elev= 30
       0   58.13 3905.95   55.81 4053.15      55 4095.89      50 5817.47   46.39
 6424.13      45 6466.13      41 6474.25      40  6516.1      40 6593.24      35
 6605.44   27.46 6607.25    25.3 6639.63    25.7 6700.09      23 6712.44    23.4
 6757.31   28.28 6793.15      35 6821.33      45 6826.03    45.7 6891.83      55
 7078.77   53.76 7353.64      50  7362.7   51.12 7392.02      55 7541.02   56.75
 8116.67   57.65 8602.93      55 9607.99   56.5210746.82   55.7914265.92   58.45
#Mann= 3 ,-1 , 0
       0     .06       0 5817.47    .035       0  7362.7     .06       0
Bank Sta=6466.13,6826.03
Exp/Cntr=0.3,0.1

Type RM Length L Ch R = 1 ,2877.   ,960.3,1018.4,882.92
XS GIS Cut Line= 6
  6392227.411551   2029628.13679  6390821.957788 2032870.5040745
 6390103.0110331 2036195.6327033 6389453.4142579 2036657.6981468
 6388854.4830113 2038738.1960693 6388427.1154437 2044676.0688077
#Sta/Elev= 30
       0   58.28 5637.07      55 5675.48      50 5818.29   48.39 7085.32   45.37
 7254.74      45 7293.46   40.85 7333.74   37.55 7392.96      30 7409.58      35
 7440.84   38.82 7475.36      35 7509.16      25 7549.43    25.7 7584.71    23.6
  7613.1    23.5 7679.27   27.75 7691.63    33.7  7728.5   41.66 7793.47      55
 8231.84   53.49 8695.87      50 8723.16   53.18 8736.27      5510169.84      55
 10214.5   50.7210295.96      5010333.79   52.3410350.68      5515916.51   57.97
#Mann= 3 ,-1 , 0
       0     .06       0 7085.32    .035       0 8723.16     .06       0
Bank Sta=7293.46,7728.5
Exp/Cntr=0.3,0.1

Type RM Length L Ch R = 1 ,1859.   ,768.48,666.49,517.54
XS GIS Cut Line= 6
 6391754.5710732 2029596.6140978   6390273.00435 2032591.2702837
 6389390.3688735 2035522.8810379 6388854.4830113 2036531.6073306
  6388160.983688 2040377.3763008 6387971.8474874 2044664.4630567
#Sta/Elev= 30
       0   57.55  4104.4      55  5718.1      50 5762.94      45 5882.41      45
 6417.44      40 6437.31   37.15 6468.82    33.3 6480.22    24.5 6493.78   22.39
 6578.82    25.7 6594.67   24.53 6634.01    24.1 6683.61    24.4 6707.58   25.81
 6754.89      27 6781.14    33.7  6835.8   41.24 6861.63      45 7058.32   47.08
 7124.25      50 7139.72      55 8269.56      50 8287.52   51.91 8297.07      55
 8356.42      5510828.92      5511387.47   53.3911835.24      5515784.43   57.96
#Mann= 3 ,-1 , 0
       0     .06       0 6707.58    .035       0 8356.42     .06       0
Bank Sta=6437.31,6835.8
Exp/Cntr=0.3,0.1

Type RM Length L Ch R = 1 ,1192.   ,2489.97,1192.08,2184.36
XS GIS Cut Line= 5
 6390934.9809811 2029344.4325601 6389565.4266274 2032410.7657738
 6388597.8620858 2035512.6637908 6387431.0931521 2040948.0996752
 6387459.5509021 2044704.5265577
#Sta/Elev= 30
       0   55.49  3966.7      55 5713.05      50 5750.66      45 6452.26      40
 6461.74   38.77 6461.98   38.74 6507.84    33.3 6520.93    22.9 6530.59    20.6
 6539.36    22.3 6583.55    25.6 6593.32    24.2 6604.62    24.3 6682.31    26.5
  6690.5      30  6695.5    33.3 6710.22      35 6714.83   36.85 6734.74      45
 7032.99      50 7045.87      55 8016.13      50 8022.67    51.6 8057.12      55
  8204.2      55 9995.32      5510972.02   51.6311924.81      5515923.37      58
#Mann= 3 ,-1 , 0
       0     .06       0 6461.98    .035       0  8204.2     .06       0
Bank Sta=6461.74,6714.83
Exp/Cntr=0.3,0.1

Storage Area=369             ,6404656.4810927,2047345.1453131
Storage Area Surface Line= 6
 6402631.9698137 2045430.5195887
 6402449.2270548 2048475.6202047
 6404586.5230883 2049570.9844248
 6406750.5353489 2049651.1330113
 6407378.3660691 2047166.5263576
 6402631.9698137 2045430.5195887
Storage Area Type= 1
Storage Area Vol Elev= 11
   63.34       0   64.59    6.26   65.84   48.26   67.09  259.54   68.34  514.59
   69.59  804.83   70.84  1129.8   72.09 1487.12   73.34 1858.41   74.59 2234.75
   75.84 2622.24

Storage Area=370             ,6408721.1859302,2042034.6452537
Storage Area Surface Line= 6
  6411089.902679 2043584.9518455
 6411085.7799576 2040882.1641541
 6408026.0069917 2039897.6286624
 6406255.6685722 2041498.3538592
 6406340.4752308 2043682.1245858
  6411089.902679 2043584.9518455
Storage Area Type= 1
Storage Area Vol Elev= 11
68.08583       069.21468    6.7370.34351  122.4371.47236  433.41 72.6012  776.84
73.73004 1135.4774.85889 1504.1375.98772 1879.4377.11657 2257.8278.24541 2641.06
79.37425 3031.72

Chan Stop Cuts=-1
Use User Specified Reach Order=0
User Specified Reach Order=Tule Creek      ,Tributary
User Specified Reach Order=Baxter River    ,Lower Reach
User Specified Reach Order=Baxter River    ,Upper Reach